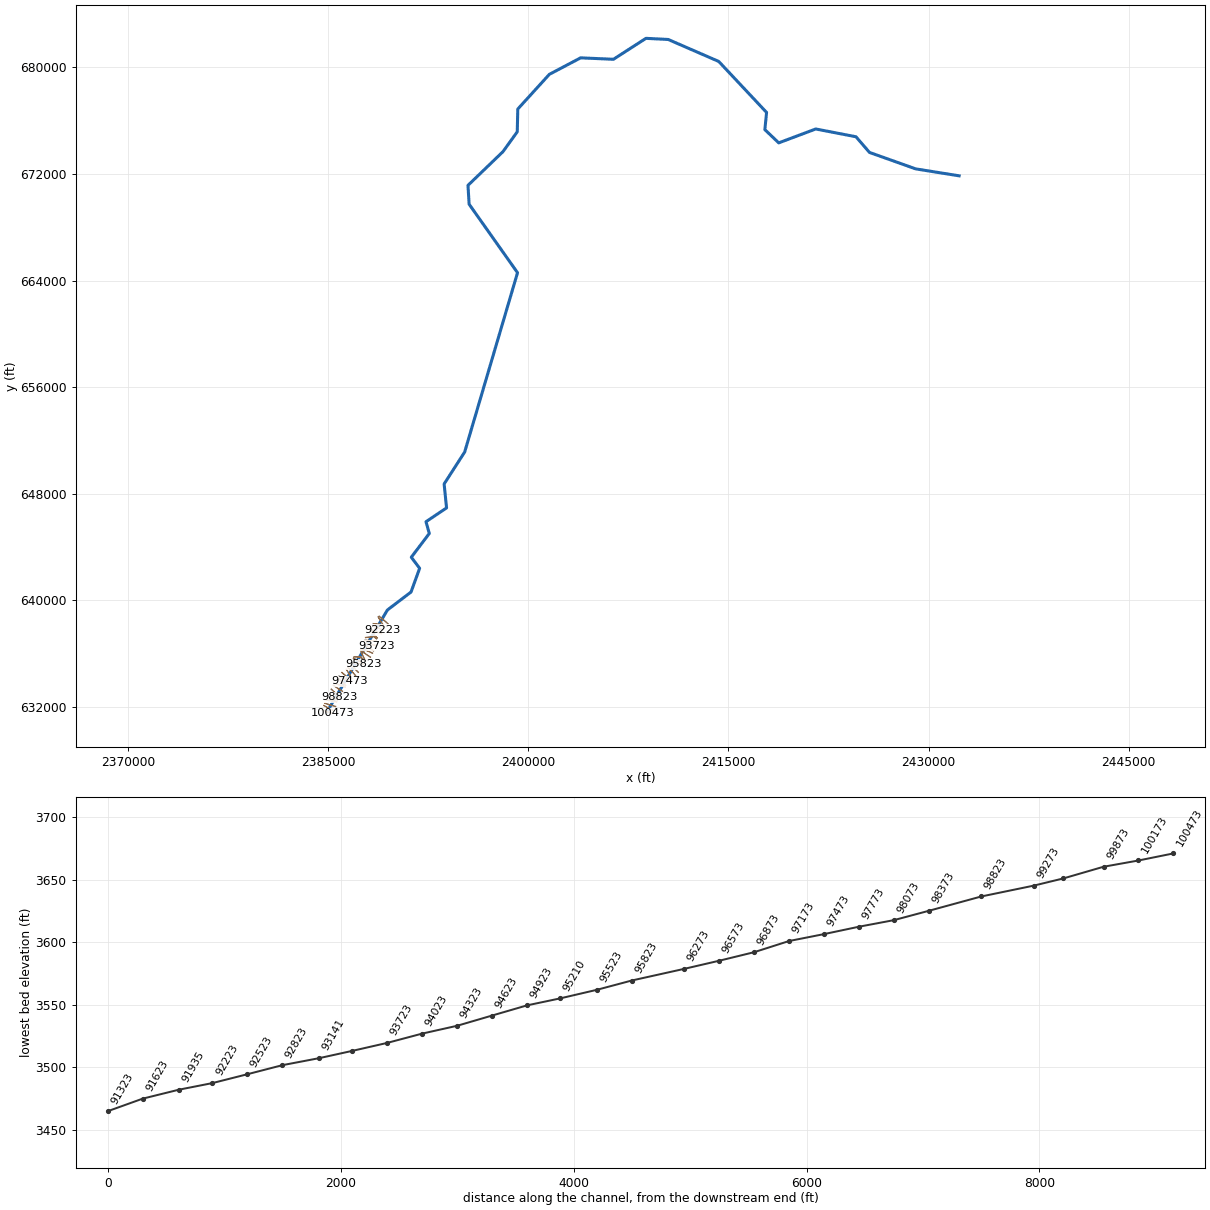
--- SENECACK.prj (project) ---

Proj Title=SENECACK
Current Plan=p01
Default Exp/Contr=0,0
English Units
Geom File=g03
Flow File=f01
Plan File=p01
BEGIN DESCRIPTION:
Stream Name: Seneca Creek
Flood Zone: Approximate
Pendleton County, West Virginia
HEC-RAS Version: 5.0.7
Hydrology Method:
Regression equation
END DESCRIPTION:
DSS File=dss
DSS Export Rating Curves= 0
DSS Export Rating Curve Sorted= 0
DSS Export Volume Flow Curves= 0
DXF OffsetX= 0
DXF OffsetY= 0
DXF ScaleX= 0
DXF ScaleY= 0

--- SENECACK.p01 (plan) ---

Plan Title=Floodplain
Program Version=5.07
Short Identifier=Floodplain
Geom File=g03
Flow File=f01
Subcritical Flow
K Sum by GR= 0
Std Step Tol= 0.01
Critical Tol= 0.01
Num of Std Step Trials= 20
Max Error Tol= 0.3
Flow Tol Ratio= 0.001
Split Flow NTrial= 30
Split Flow Tol= 0.02
Split Flow Ratio= 0.02
Log Output Level= 0
Friction Slope Method= 1
Unsteady Friction Slope Method= 2
Unsteady Bridges Friction Slope Method= 1
Parabolic Critical Depth
Global Vel Dist= 0 , 0 , 0
Global Log Level= 0
CheckData=True
Encroach Param=-1 ,0,0, 0
Computation Interval=0.1SEC
Output Interval=1MIN
Instantaneous Interval=Max Profile
Mapping Interval=1HOUR
Computation Time Step Use Courant=        0
Computation Time Step Use Time Series=    0
Computation Time Step Count To Double=0
Computation Time Step Max Doubling=0
Computation Time Step Max Halving=0
Computation Time Step Residence Courant=0
Run HTab= 0
Run UNet= 0
Run Sediment= 0
Run PostProcess= 0
Run WQNet= 0
Run RASMapper= 0
UNET Theta= 0
UNET Theta Warmup= 0
UNET ZTol= 0
UNET ZSATol= 0
UNET MxIter= 0
UNET Max Iter WO Improvement= 0
UNET MaxInSteps= 0
UNET DtIC= 0
UNET DtMin= 0
UNET MaxCRTS= 0
UNET WFStab= 0
UNET SFStab= 0
UNET WFX= 1
UNET SFX= 1
UNET 1D Methodology=Finite Difference
UNET DSS MLevel= 1
UNET Pardiso=0
UNET DZMax Abort= 0
UNET Use Existing IB Tables= 0
UNET Froude Reduction=False
UNET Froude Limit= 0
UNET Froude Power= 0
UNET D1 Cores= 0
UNET D2 Coriolis=0
UNET D2 Cores= 0
UNET D2 Theta= 1
UNET D2 Theta Warmup= 1
UNET D2 Z Tol= 0.01
UNET D2 Volume Tol= 0.01
UNET D2 Max Iterations= 20
UNET D2 Equation= 0
UNET D2 RampUpFraction=0.1
UNET D2 TimeSlices= 1
UNET D2 BCVolumeCheck=0
UNET D1D2 MaxIter= 0
UNET D1D2 ZTol=0.01
UNET D1D2 QTol=0.1
UNET D1D2 MinQTol=1
DSS File=dss
Write IC File= 0
Write IC File at Fixed DateTime=0
Write IC File at Sim End=0
Echo Input=False
Echo Parameters=False
Echo Output=False
Write Detailed= 0
HDF Write Warmup=0
HDF Write Time Slices=0
HDF Flush=0
HDF Face Node Velocities=0
HDF Compression= 1
HDF Chunk Size= 1
HDF Spatial Parts= 1
HDF Use Max Rows=0
HDF Fixed Rows= 1
Calibration Method= 0
Calibration Iterations= 20
Calibration Max Change=0.05
Calibration Tolerance=0.2
Calibration Maximum=1.5
Calibration Minimum=0.5
Calibration Optimization Method= 1
WQ AD Non Conservative
WQ ULTIMATE=-1
WQ Max Comp Step=1HOUR
WQ Output Interval=15MIN
WQ Output Selected Increments= 0
WQ Output face flow=0
WQ Output face velocity=0
WQ Output face area=0
WQ Output face dispersion=0
WQ Output cell volume=0
WQ Output cell surface area=0
WQ Output cell continuity=0
WQ Output cumulative cell continuity=0
WQ Output face conc=0
WQ Output face dconc_dx=0
WQ Output face courant=0
WQ Output face peclet=0
WQ Output face adv mass=0
WQ Output face disp mass=0
WQ Output cell mass=0
WQ Output cell source sink temp=0
WQ Output nsm pathways=0
WQ Output nsm derived pathways=0
WQ Output MaxMinRange=-1
WQ Daily Max Min Mean=-1
WQ Daily Range=0
WQ Daily Time=0
WQ Create Restart=0
WQ Fixed Restart=0
WQ System Summary=0
WQ Write To DSS=0
WQ Use Fixed Temperature=0
Sorting and Armoring Iterations= 10
XS Update Threshold= 0.02
Bed Roughness Predictor= 0
Hydraulics Update Threshold= 0.02
Energy Slope Method= 1
Volume Change Method= 1
Sediment Retention Method= 0
XS Weighting Method= 0
Number of US Weighted Cross Sections= 1
Number of DS Weighted Cross Sections= 1
Upstream XS Weight=0
Main XS Weight=1
Downstream XS Weight=0
Number of DS XS's Weighted with US Boundary= 1
Upstream Boundary Weight= 1
Weight of XSs Associated with US Boundary= 0
Number of US XS's Weighted with DS Boundary= 1
Downstream Boundary Weight= 0.5
Weight of XSs Associated with DS Boundary= 0.5
Percentile Method= 0
Sediment Output Level= 3
Mass or Volume Output= 0
Output Increment Type= 1
Profile and TS Output Increment= 1
XS Output Flag= 0
XS Output Increment= 10
Write Gradation File= 0
Read Gradation Hotstart= 0
Write HDF5 File= 1
Write Binary Output= 1
Write DSS Sediment File= 0
SV Curve= 0
Specific Gage Flag= 0

--- SENECACK.f01 (steady flow) ---

Flow Title=Flows
Program Version=5.07
Number of Profiles= 6
Profile Names=P100yr,P10yr,P25yr,P50yr,P500yr,P101yr
River Rch & RM=SENECACK,Main            ,100473
     591     277     391     488     867     720
River Rch & RM=SENECACK,Main            ,97773
     693     323     457     571    1017     843
River Rch & RM=SENECACK,Main            ,95210
     911     423     600     751    1341    1108
River Rch & RM=SENECACK,Main            ,94923
    1039     482     684     856    1533    1265
River Rch & RM=SENECACK,Main            ,93141
    1171     542     770     964    1729    1425
River Rch & RM=SENECACK,Main            ,90123
    1304     603     856    1074    1928    1587
River Rch & RM=SENECACK,Main            ,87723
    1486     685     975    1223    2200    1808
River Rch & RM=SENECACK,Main            ,85023
    1651     760    1082    1358    2447    2009
River Rch & RM=SENECACK,Main            ,79488
    1869     859    1224    1536    2773    2274
River Rch & RM=SENECACK,Main            ,74673
    2098     962    1372    1724    3117    2553
River Rch & RM=SENECACK,Main            ,70024
    2377    1088    1553    1953    3537    2893
River Rch & RM=SENECACK,Main            ,64023
    2718    1242    1774    2231    4049    3307
River Rch & RM=SENECACK,Main            ,57871
    3062    1396    1996    2513    4567    3726
River Rch & RM=SENECACK,Main            ,53973
    3403    1550    2217    2792    5082    4142
River Rch & RM=SENECACK,Main            ,41239
    4715    2136    3064    3864    7066    5739
River Rch & RM=SENECACK,Main            ,34387
    5317    2405    3451    4355    7977    6470
River Rch & RM=SENECACK,Main            ,29673
    7078    3187    4584    5792   10651    8613
River Rch & RM=SENECACK,Main            ,17974
    9340    4188    6035    7635   14096   11366
River Rch & RM=SENECACK,Main            ,13923
   11351    5075    7323    9273   17167   13814
Boundary for River Rch & Prof#=SENECACK,Main            , 1
Up Type= 0
Dn Type= 3
Dn Slope=0.03753
Boundary for River Rch & Prof#=SENECACK,Main            , 2
Up Type= 0
Dn Type= 3
Dn Slope=0.03753
Boundary for River Rch & Prof#=SENECACK,Main            , 3
Up Type= 0
Dn Type= 3
Dn Slope=0.03753
Boundary for River Rch & Prof#=SENECACK,Main            , 4
Up Type= 0
Dn Type= 3
Dn Slope=0.03753
Boundary for River Rch & Prof#=SENECACK,Main            , 5
Up Type= 0
Dn Type= 3
Dn Slope=0.03753
Boundary for River Rch & Prof#=SENECACK,Main            , 6
Up Type= 0
Dn Type= 3
Dn Slope=0.03753
DSS Import GetInterval= 0
DSS Import GetPeak= 0
DSS Import FillOption= 0

--- SENECACK.g03 (geometry) ---

Geom Title=Geometry
Program Version=5.07

River Reach=SENECACK        ,Main
Reach XY= 30
     2384913.755      631646.453     2389441.725      639284.689
     2391213.565      640635.058     2391858.601      642415.338
     2391233.173      643244.014     2392583.068      645027.482
     2392333.758      645908.459     2393876.329      646943.688
      2393693.18      648738.786     2395232.216      651132.548
     2399194.896      664585.772     2395566.322      669723.645
     2395482.642      671139.077     2398104.257       673666.21
     2399174.938      675154.039     2399213.583      676861.725
     2401579.386      679464.172     2403924.173      680701.871
      2406382.75      680594.053     2408818.683      682165.372
     2410484.111       682080.65     2414273.284       680431.67
     2417857.632      676607.039     2417729.521       675316.91
     2418769.946      674324.953     2421543.298      675366.376
     2424558.195      674783.075     2425572.074      673606.637
     2429031.508      672374.194     2432289.056      671852.612

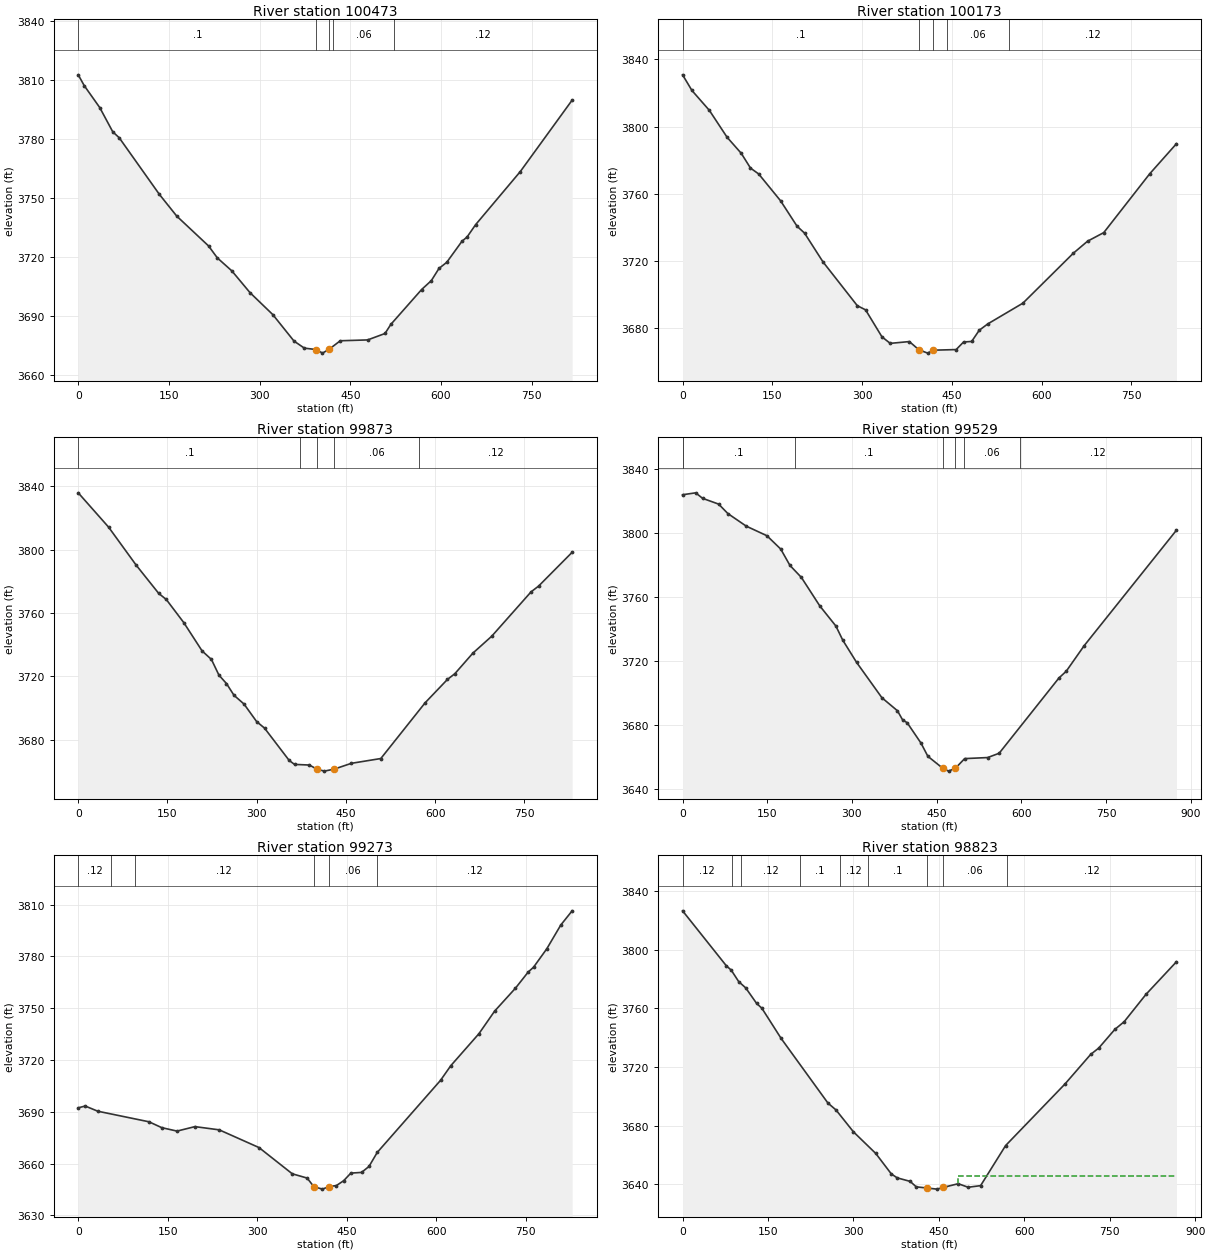
Type RM Length L Ch R = 1 ,100473  ,301.3,300,298.1
XS GIS Cut Line= 3
     2384537.468      631801.205     2384916.823      631655.916
2385308.55745838631532.516736325
#Sta/Elev= 30
       0 3812.64     9.9 3807.15    35.6 3795.97    57.1 3783.65    67.8 3780.61
   134.2  3751.8     163 3740.72   215.5 3725.58   230.1 3719.46   254.1 3712.86
   284.1 3701.79   321.8 3690.62   356.9 3677.14     374 3673.55   393.9 3672.82
     404 3671.01     415 3672.99   433.4  3677.3   478.7 3677.73   507.4    3681
     517 3685.62     568 3703.39     584  3707.9   596.7 3714.12   609.5 3717.22
   634.7 3727.94   643.1  3730.1   657.3  3736.4   731.2 3763.42   816.9 3799.76
#Mann= 5 ,-1 , 0
       0      .1       0   393.9    .045       0     415      .1       0
  421.59     .06       0  521.95     .12       0
Bank Sta=393.9,415
XS Rating Curve= 0 ,0
Exp/Cntr=0.3,0.1

Type RM Length L Ch R = 1 ,100173  ,292.9,300,299.3
XS GIS Cut Line= 3
     2384687.604      632121.011     2385044.997      631922.031
2385414.61294316631730.475154579
#Sta/Elev= 30
       0 3830.77    15.6 3821.48    44.8 3809.63    74.4 3793.65      98 3784.15
   113.5 3775.34   127.2 3771.84   163.8 3755.89   191.3 3740.79   203.8  3736.7
   234.6  3719.6     292 3693.55   305.8 3691.07   333.2 3675.03     347 3671.15
     379 3672.22     395 3667.31   409.7 3665.35   418.6 3667.09   457.2 3667.46
   469.6 3671.97   483.1 3672.29   495.8 3678.95   510.1 3682.73   568.7 3695.04
     653 3724.73   676.8 3731.88   703.9 3736.99   780.6 3771.92   825.4 3789.84
#Mann= 5 ,-1 , 0
       0      .1       0     395    .045       0   418.6      .1       0
  441.26     .06       0   545.8     .12       0
Bank Sta=395,418.6
XS Rating Curve= 0 ,0
Exp/Cntr=0.3,0.1

Type RM Length L Ch R = 1 ,99873   ,340.7,344.3,340.5
XS GIS Cut Line= 3
     2384762.387      632289.931     2385155.781      632158.739
2385557.41566574632052.074562689
#Sta/Elev= 30
       0 3835.78      51 3814.17    97.5 3790.14   135.3 3772.37     148 3768.55
   177.5 3753.92   208.2 3736.12   223.9 3730.74   236.5 3720.87   249.2 3715.53
   261.8 3708.17   278.7 3702.62   299.9 3691.56   313.1 3687.48   354.6 3667.07
   363.6 3664.58   388.5 3664.18     401 3661.65   413.6 3660.34   430.2  3661.6
   459.1 3665.26   508.6 3668.28   583.3 3703.51   620.6 3718.15     633 3721.73
   663.4 3734.74     695 3745.37   761.3  3773.4   773.7 3776.94   830.2 3798.29
#Mann= 5 ,-1 , 0
       0      .1       0  373.29     .06       0     401    .045       0
   430.2     .06       0  573.23     .12       0
Bank Sta=401,430.2
XS Rating Curve= 0 ,0
Exp/Cntr=0.3,0.1

Type RM Length L Ch R = 1 ,99529   ,257,255.7,251.8
XS GIS Cut Line= 2
2384775.98678247632559.6155263192385635.16663602632394.693760641
#Sta/Elev= 30
       0 3824.14    23.2 3825.34    35.4  3821.9    63.9 3818.27    80.2 3812.36
   112.8 3804.47   149.4 3798.47   173.9  3790.1   190.2 3779.87   210.5 3772.33
   243.1 3754.49   271.6  3741.9   283.8 3733.03   308.3 3719.11   353.1 3696.99
   380.6 3688.85   389.7 3683.16   397.9 3681.32   422.3 3668.61   434.5 3660.31
   460.9 3652.83   471.2 3651.03   483.4  3652.9   499.7 3658.87   540.4 3659.53
   560.8 3662.23   666.7 3709.38   679.6 3713.58   711.5 3729.66   874.9 3801.95
#Mann= 7 ,-1 , 0
       0      .1       0     .92      .1       0  199.64      .1       0
   460.9    .045       0   483.4      .1       0  497.72     .06       0
  597.08     .12       0
Bank Sta=460.9,483.4
XS Rating Curve= 0 ,0
Exp/Cntr=0.3,0.1

Type RM Length L Ch R = 1 ,99273   ,451.5,450,445.4
XS GIS Cut Line= 3
     2384931.771      632854.334     2385313.214      632710.404
     2385697.649      632540.766
#Sta/Elev= 30
       0 3692.31    11.7 3693.34    32.9 3690.33   118.6 3684.22     140 3680.82
   165.6 3678.83   195.6 3681.42   236.4 3679.55     303  3669.3   358.8  3654.1
   383.7 3651.63     395 3646.64   409.4 3645.23   420.6 3646.74   432.8  3647.3
   444.9  3650.1     457 3654.51   474.9  3654.9   487.4 3658.36   501.2 3666.48
   607.3 3708.22   624.5  3716.7   671.7 3735.24   697.9 3748.26   732.9 3761.58
   754.3 3770.95   763.2 3773.71   785.4 3784.38   808.9 3798.16   827.9 3806.37
#Mann= 6 ,-1 , 0
       0     .12       0   55.74      .1       0   94.85     .12       0
     395    .045       0   420.6     .06       0  501.38     .12       0
Bank Sta=395,420.6
XS Rating Curve= 0 ,0
Exp/Cntr=0.3,0.1

Type RM Length L Ch R = 1 ,98823   ,445.7,450,446
XS GIS Cut Line= 3
     2385234.762      633347.631     2385559.883      633044.281
2385848.79829695632735.892894062
#Sta/Elev= 30
       0 3826.74    76.9 3789.15    85.4 3786.24    98.5 3778.39   110.9 3774.06
   130.1 3763.42   139.2  3760.2   173.1 3739.51   255.2 3695.39   269.4 3690.66
   300.1 3675.68   339.2 3660.95   366.5 3646.96   376.9 3644.26   399.6 3641.86
   410.3 3638.12   429.1 3637.33   446.6 3636.57   457.5 3637.73     484 3640.27
   501.4 3637.85   523.3 3638.96   567.2 3666.34   671.2 3708.31   716.5 3728.61
   730.7 3732.97   758.9 3745.68   775.4 3750.99   813.8 3769.73   867.2 3791.95
#Mann= 9 ,-1 , 0
       0     .12       0      86      .1       0   102.8     .12       0
  205.53      .1       0  276.41     .12       0  325.06      .1       0
   429.1    .045       0   457.5     .06       0  570.03     .12       0
#XS Ineff= 2 , 0
                          484.43         3645.46
Permanent Ineff=
       F       F
Bank Sta=429.1,457.5
XS Rating Curve= 0 ,0
Exp/Cntr=0.3,0.1

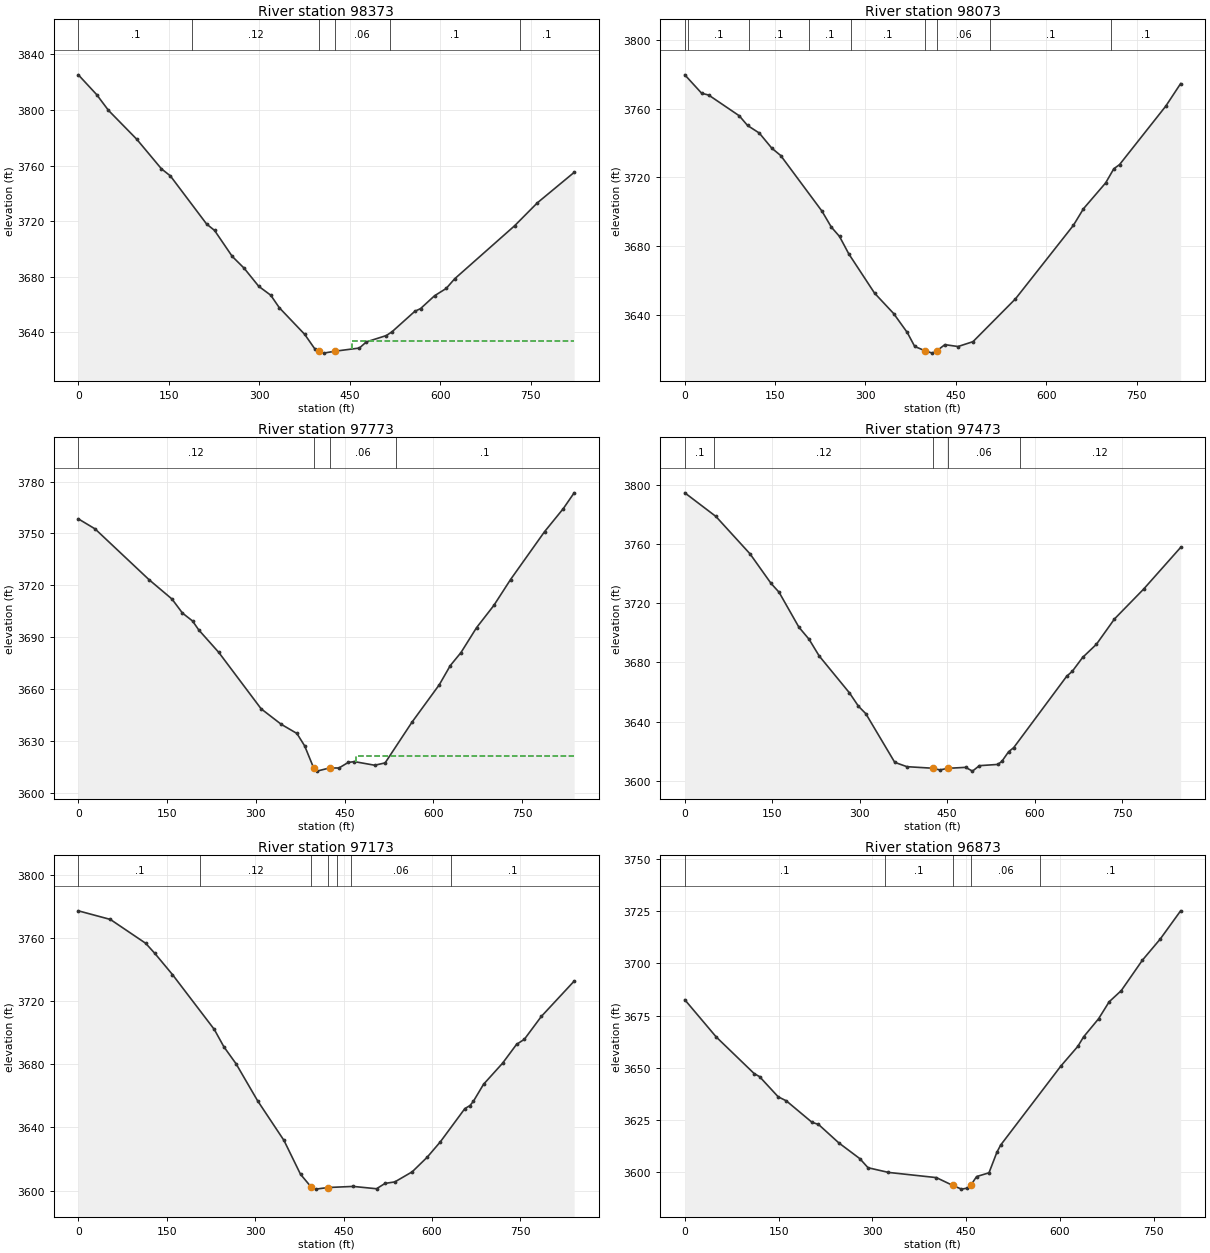
Type RM Length L Ch R = 1 ,98373   ,295.6,300,301.6
XS GIS Cut Line= 3
     2385385.862       633646.49     2385720.353      633411.709
     2386070.367      633191.288
#Sta/Elev= 30
       0 3825.34    30.4 3811.11    49.9 3799.81    96.8 3779.04   137.9 3757.68
   152.6 3752.64   212.8 3717.97   225.9 3713.41   255.2 3694.73   274.8 3686.29
   299.2 3673.19   319.1 3666.79   333.4 3657.74   375.3 3638.68     392 3628.29
   399.5 3626.42   406.7 3625.12   425.7  3626.5   466.1 3628.78   477.7 3633.19
   510.8 3637.77   520.2 3640.47     558 3655.18   567.5 3657.14   590.8  3666.4
     610 3671.62   624.2 3678.62   723.5 3716.73   761.3 3733.26   822.3 3755.17
#Mann= 6 ,-1 , 0
       0      .1       0  189.33     .12       0   399.5    .045       0
   425.7     .06       0  516.18      .1       0  731.96      .1       0
#XS Ineff= 2 , 0
                          454.45         3634.08
Permanent Ineff=
       F       F
Bank Sta=399.5,425.7
XS Rating Curve= 0 ,0
Exp/Cntr=0.3,0.1

Type RM Length L Ch R = 1 ,98073   ,304.2,300,292.3
XS GIS Cut Line= 3
     2385471.879      633780.965     2385867.088      633667.341
     2386260.927      633546.297
#Sta/Elev= 30
       0 3779.65      28 3768.91    39.6 3767.88    90.4 3755.81   104.2 3750.16
   123.7 3745.75   144.5 3736.93   159.2 3732.69   227.7 3700.32   243.2 3691.05
   256.9 3685.56   272.3  3675.4   315.1 3652.55   346.7 3640.71   369.3 3629.68
   381.7 3621.55   398.4 3619.09   410.9 3617.65   418.73619.073   431.8 3622.59
   453.6 3621.49   478.5 3624.33     549 3649.25   645.2 3692.06   661.9 3701.71
   698.7 3716.73   712.3 3724.98   721.8 3727.39   798.6 3761.46   823.2 3774.54
#Mann= 9 ,-1 , 0
       0      .1       0    6.13      .1       0  106.15      .1       0
  206.18      .1       0   276.7      .1       0   398.4    .045       0
   418.7     .06       0  506.49      .1       0  707.01      .1       0
Bank Sta=398.4,418.7
XS Rating Curve= 0 ,0
Exp/Cntr=0.3,0.1

Type RM Length L Ch R = 1 ,97773   ,296.4,300,302.8
XS GIS Cut Line= 3
2385710.70197872634219.814680844     2385997.822      633933.272
     2386307.898      633632.029
#Sta/Elev= 30
       0  3758.4    28.3 3752.59   119.5  3723.2   158.3 3711.99     176 3703.87
     193  3699.3   203.5 3694.13   237.4 3681.09     309 3648.44   342.9  3639.5
   369.4  3634.2   382.5 3627.01   397.93614.079   403.3 3612.39   424.9 3614.26
   440.4 3614.19   456.1 3617.42   466.5  3617.9   500.9  3615.8   518.5 3617.15
     564 3640.77     610 3662.36   628.6 3673.46   646.7 3681.02   673.1 3695.46
   702.2 3708.27   730.5 3723.29   787.9 3750.96   819.6 3764.32     838 3773.47
#Mann= 4 ,-1 , 0
       0     .12       0   397.9    .045       0   424.9     .06       0
  536.45      .1       0
#XS Ineff= 2 , 0
                          469.28         3621.09
Permanent Ineff=
       F       F
Bank Sta=397.9,424.9
XS Rating Curve= 0 ,0
Exp/Cntr=0.3,0.1

Type RM Length L Ch R = 1 ,97473   ,299.1,300,285.5
XS GIS Cut Line= 3
      2385819.44      634325.248     2386205.223      634124.463
       2386570.5      633926.916
#Sta/Elev= 30
       0 3794.58    53.3 3778.63   111.9 3753.31     148  3733.3   161.6 3727.41
   195.7 3703.74     213 3695.65   230.4 3684.35   282.4 3659.34   297.8 3650.33
   310.4 3645.31     360 3612.42   380.9 3609.49   425.4 3608.43   437.2  3607.3
   451.9 3608.39   481.5 3609.03   493.3 3606.48   505.1 3610.17   536.7 3611.01
   543.7 3613.11   555.2 3619.57     564 3622.36   654.9 3670.63   664.4 3673.93
   682.2 3683.33   705.8 3692.21   736.8 3709.34   786.8 3729.53   850.2 3757.67
#Mann= 5 ,-1 , 0
       0      .1       0   50.63     .12       0   425.4    .045       0
   451.9     .06       0  574.37     .12       0
Bank Sta=425.4,451.9
XS Rating Curve= 0 ,0
Exp/Cntr=0.3,0.1

Type RM Length L Ch R = 1 ,97173   ,300.5,300,294.4
XS GIS Cut Line= 3
     2386032.957      634593.933     2386344.106      634335.219
     2386658.254      634032.179
#Sta/Elev= 30
       0 3777.17    54.3 3771.72   114.2 3756.63   129.9 3750.17   159.7  3736.8
   230.7 3702.04   246.8 3691.14   267.6 3680.31     304 3656.96   348.9 3631.75
   376.9 3610.36   395.4 3602.08   402.9 3600.95   423.7 3601.97   466.2 3602.67
   505.8 3601.19   520.4 3604.59   536.9 3605.52   566.4 3611.93   591.7 3621.12
     614 3630.85   655.7 3651.95   664.4 3653.87   670.2  3656.6   687.4 3667.35
   719.6 3680.66   743.4 3692.62   756.6 3695.82   785.4 3710.29   841.1 3732.67
#Mann= 7 ,-1 , 0
       0      .1       0  206.97     .12       0   395.4    .045       0
   423.7     .12       0  439.17      .1       0  463.08     .06       0
  632.56      .1       0
Bank Sta=395.4,423.7
XS Rating Curve= 0 ,0
Exp/Cntr=0.3,0.1

Type RM Length L Ch R = 1 ,96873   ,297.6,300,302.7
XS GIS Cut Line= 3
     2386365.689      634841.881     2386593.184      634464.357
2386759.62362412634154.145640684
#Sta/Elev= 30
       0 3682.57    50.2 3664.79   110.9 3647.28   119.5 3645.82   149.3 3636.17
   162.3 3634.24   203.5 3623.94   213.6    3623   246.3 3614.12   279.8 3606.61
     293 3602.25   325.7 3600.01   402.2 3597.53   428.7 3593.76   442.4 3592.02
   451.9  3592.5   457.8 3594.12   466.6 3598.03   486.4 3599.83   499.1  3609.7
     505 3613.07   601.3 3650.87   628.5 3660.31   637.6 3664.81   661.6 3673.47
   678.5 3681.58   697.9 3686.95   731.7  3701.5   760.2  3711.6   792.8 3725.09
#Mann= 5 ,-1 , 0
       0      .1       0  319.38      .1       0   428.7    .045       0
   457.8     .06       0  568.51      .1       0
Bank Sta=428.7,457.8
XS Rating Curve= 0 ,0
Exp/Cntr=0.3,0.1

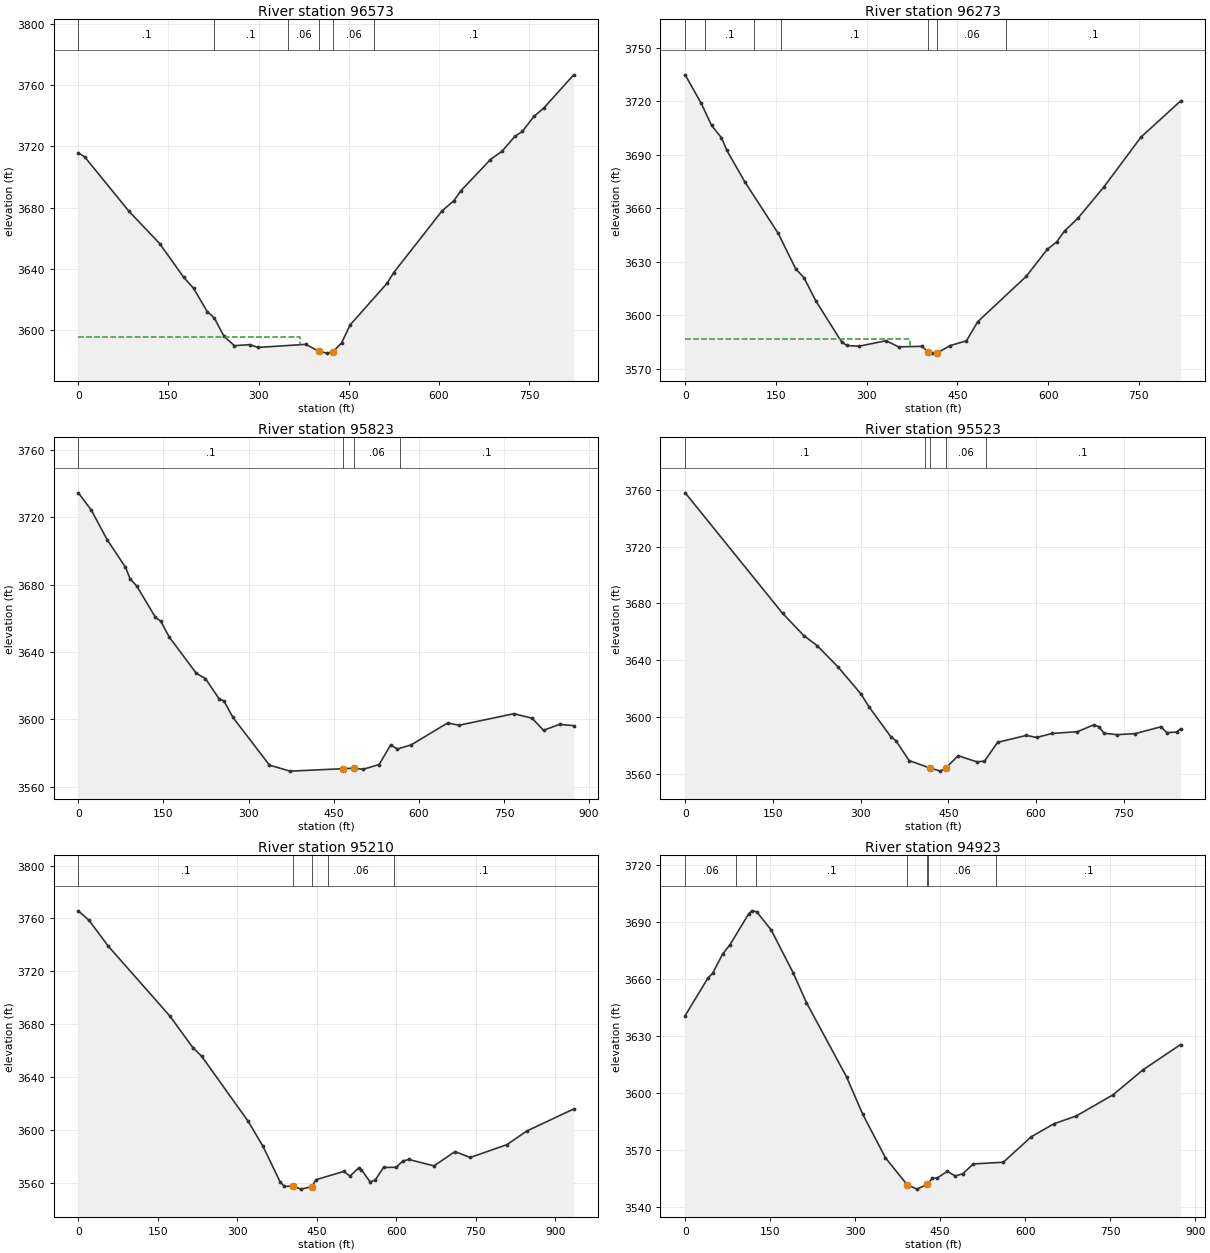
Type RM Length L Ch R = 1 ,96573   ,299.2,300,300.5
XS GIS Cut Line= 3
     2386491.024      634970.443     2386784.466      634678.062
     2387053.755      634369.211
#Sta/Elev= 30
       0 3715.87    10.7 3713.16    84.4 3677.64   135.4 3656.63     175 3634.81
   191.8 3627.44   214.4  3612.3   226.1 3608.19   242.4 3596.16   259.7 3590.05
   285.2 3590.72   298.9 3588.92   378.5 3590.91   400.5  3586.3   414.2 3585.19
   423.5 3586.12   437.9 3591.79   452.1 3603.55     514 3630.94   524.6  3637.7
   605.2 3678.02   624.7 3684.57     636 3690.91   685.5 3711.43     705 3716.91
   726.2 3726.55   738.5 3729.77   758.1 3739.64     774 3744.88     824 3766.69
#Mann= 6 ,-1 , 0
       0      .1       0   226.1      .1       0  348.38     .06       0
   400.5    .045       0   423.5     .06       0  491.74      .1       0
#XS Ineff= 2 , 0
          368.43 3595.52
Permanent Ineff=
       F       F
Bank Sta=400.5,423.5
XS Rating Curve= 0 ,0
Exp/Cntr=0.3,0.1

Type RM Length L Ch R = 1 ,96273   ,444.2,450,456.7
XS GIS Cut Line= 3
      2386688.64      635206.244     2386971.231      634909.882
     2387256.243      634615.821
#Sta/Elev= 30
       0 3734.79    26.5 3718.78    43.6 3706.38    59.9 3699.52    68.9 3692.35
    98.6 3674.74   153.8 3645.85   182.7 3625.97   196.2 3621.08   216.1 3607.92
   258.5 3585.07     267    3583   286.8 3582.54   332.1 3585.66   352.8 3582.23
   391.5  3582.5     4023579.187   408.4  3578.7     417 3578.83   437.5 3582.87
     465 3585.61   483.5 3596.28     564 3621.83   598.5 3636.85   614.2 3641.07
   627.2 3647.23   648.9 3654.23   692.2  3671.9   753.6 3699.88     819 3720.11
#Mann= 7 ,-1 , 0
       0      .1       0   33.02      .1       0  113.99      .1       0
  157.63      .1       0     402    .045       0     417     .06       0
  530.71      .1       0
#XS Ineff= 2 , 0
          371.41 3586.51
Permanent Ineff=
       F       F
Bank Sta=402,417
XS Rating Curve= 0 ,0
Exp/Cntr=0.3,0.1

Type RM Length L Ch R = 1 ,95823   ,300.1,300,292
XS GIS Cut Line= 3
     2386764.266      635321.753     2387234.584      635266.035
      2387631.52      635223.633
#Sta/Elev= 30
       0 3734.42    22.8 3724.23    50.8 3706.63    83.1 3690.31    91.1 3683.55
   103.2 3679.03   135.4 3660.86   145.3 3658.24   160.3 3648.87   207.9 3627.41
     224 3624.25   248.2 3612.22   256.3 3611.13   272.4 3601.26   336.8 3572.93
   373.1 3569.38   466.13570.813   485.8 3571.12   501.9 3570.46   530.1 3573.31
   550.2 3584.85   562.3 3582.53   586.4 3584.93   650.8 3597.95   670.9  3596.6
   767.5 3603.44   799.6 3600.74   819.7 3593.58   847.9 3597.11   872.8 3596.36
#Mann= 4 ,-1 , 0
       0      .1       0   466.1    .045       0   485.8     .06       0
  566.63      .1       0
Bank Sta=466.1,485.8
XS Rating Curve= 0 ,0
Exp/Cntr=0.3,0.1

Type RM Length L Ch R = 1 ,95523   ,304.8,313,316.5
XS GIS Cut Line= 3
2386897.85606408635670.066963799     2387282.865      635472.827
     2387656.788      635293.229
#Sta/Elev= 30
       0 3757.84   166.5 3673.05   203.2 3657.23   225.7  3650.3   261.6 3635.19
   300.2 3616.51   315.1 3606.83   351.6 3586.26   360.5 3583.33     383 3569.39
   418.6 3564.13   436.7 3561.94   446.3 3564.42   466.9 3572.77     499  3568.5
   511.9 3568.93   534.5 3582.23   583.8  3587.1   601.1 3585.62   627.7 3588.48
   670.8 3589.69   698.7 3594.49   707.6 3593.24   716.5  3588.6   738.6  3587.6
   769.7 3588.35   814.1 3593.17   823.6 3589.03   840.7 3589.44   847.4 3591.71
#Mann= 5 ,-1 , 0
       0      .1       0  410.53     .06       0   418.6    .045       0
   446.3     .06       0  514.26      .1       0
Bank Sta=418.6,446.3
XS Rating Curve= 0 ,0
Exp/Cntr=0.3,0.1

Type RM Length L Ch R = 1 ,95210   ,306.8,287,270.9
XS GIS Cut Line= 3
2386938.36019778 635770.147598892387460.11494147635756.059300832
     2387728.229      635442.571
#Sta/Elev= 30
       0 3765.77    20.4  3758.5    56.4 3739.08   172.4  3686.3   216.5 3662.02
   232.5 3655.82   320.5 3606.43   348.5 3587.41   380.5  3560.8   388.5 3557.19
   404.9 3557.42   420.5 3555.13   440.5 3557.05   448.5 3562.28   500.6 3568.52
   512.6 3565.01   528.7 3571.15     534 3569.92   550.6 3560.47   560.3 3562.19
   575.7 3571.51   599.8 3571.67   612.1 3576.39   623.5 3577.56   670.9 3572.73
   710.6 3583.54   739.3 3579.07   808.3 3588.77     846 3599.11   934.4 3615.81
#Mann= 5 ,-1 , 0
       0      .1       0   404.9    .045       0   440.5      .1       0
  470.18     .06       0  596.41      .1       0
Bank Sta=404.9,440.5
XS Rating Curve= 0 ,0
Exp/Cntr=0.3,0.1

Type RM Length L Ch R = 1 ,94923   ,291.6,300,303.7
XS GIS Cut Line= 3
     2387429.253      636284.298      2387578.43      635900.236
     2387787.112       635487.73
#Sta/Elev= 30
       0 3640.82    40.1 3660.53    48.7 3663.15    65.9 3673.12    78.8 3677.97
   112.1 3694.38   117.4  3695.9     126 3695.46   151.7 3685.85   190.3 3663.44
     214 3647.63   284.7 3608.55   313.5 3588.78   353.4    3566   391.7 3551.81
   409.2 3549.49     427 3551.98   435.9 3555.18   444.9 3555.39   462.8 3558.87
   476.3 3556.44   489.7 3557.52   508.5 3562.75   561.5 3563.64   610.8 3577.05
   651.1 3583.92   690.1 3587.95   755.6  3599.2     808 3612.26   874.3 3625.55
#Mann= 7 ,-1 , 0
       0     .06       0   90.19      .1       0  125.76      .1       0
   391.7    .045       0     427      .1       0  429.32     .06       0
  549.38      .1       0
Bank Sta=391.7,427
XS Rating Curve= 0 ,0
Exp/Cntr=0.3,0.1

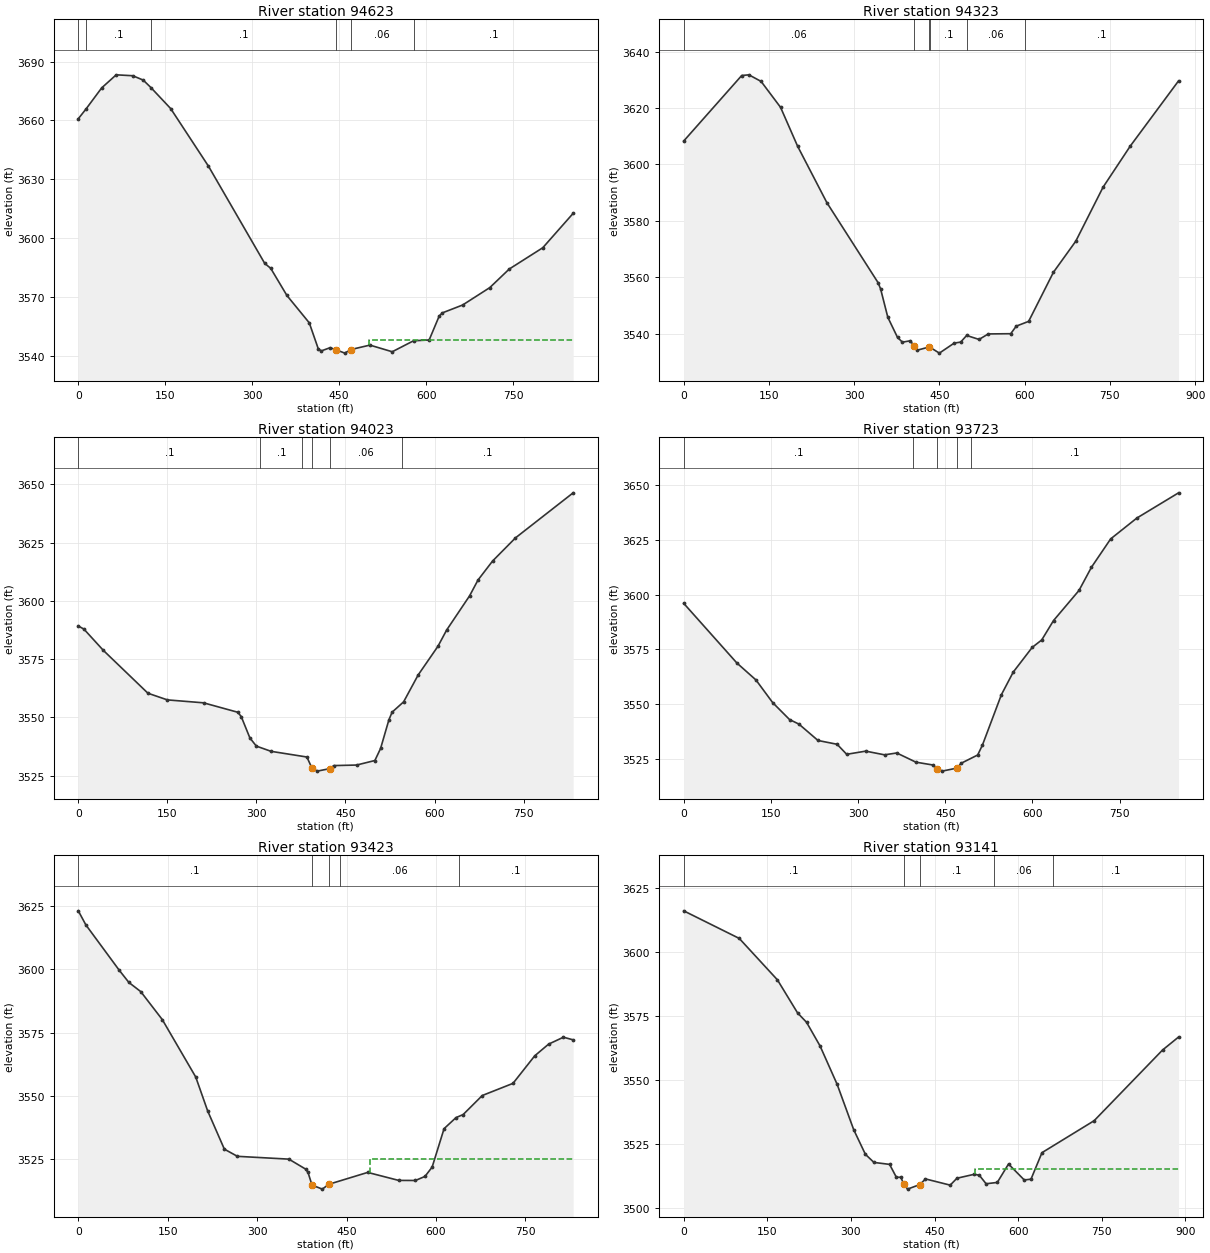
Type RM Length L Ch R = 1 ,94623   ,293.4,300,298.6
XS GIS Cut Line= 3
2387479.17620851636259.284636151     2387837.136      635973.776
     2388166.359      635754.039
#Sta/Elev= 30
       0 3660.87    13.5 3665.91    40.4 3676.62    65.4 3683.27    93.9 3682.81
     112 3680.59   125.2  3676.8   159.4 3666.06   224.6 3636.67   321.6 3587.13
     332 3584.59   359.9 3570.75   398.5 3556.79   413.9 3543.65     419 3542.46
   434.4 3544.12     444 3543.13   459.8 3541.35   469.8 3543.15   503.1 3545.44
   541.6 3542.05   578.4 3547.65   605.3 3548.05   622.6 3560.25   628.1 3561.88
     663 3565.88   709.9 3574.76   743.5 3584.24   801.3 3595.09   853.7 3612.63
#Mann= 6 ,-1 , 0
       0     .06       0    13.5      .1       0   125.2      .1       0
     444    .045       0   469.8     .06       0   578.4      .1       0
#XS Ineff= 2 , 0
                           501.5            3548
Permanent Ineff=
       F       F
Bank Sta=444,469.8
XS Rating Curve= 0 ,0
Exp/Cntr=0.3,0.1

Type RM Length L Ch R = 1 ,94323   ,300.6,300,292.4
XS GIS Cut Line= 3
2387519.70625193636383.913408687     2387905.247      636234.991
     2388324.537      636051.852
#Sta/Elev= 30
       0  3608.3   102.1 3631.52   114.7 3631.76   136.2 3629.43   170.5 3620.23
   200.5 3606.45     252 3586.46     342 3558.15   346.5 3555.91   359.2 3545.86
   376.3 3538.72   384.9 3537.05   399.1 3537.56   405.3 3535.59   411.4 3534.23
   432.4 3535.37   449.9 3533.17     476 3536.72   487.4 3537.08   497.9 3539.43
   519.7 3538.02     536 3539.97   575.5 3540.05   585.2 3542.73     607 3544.42
   650.6 3561.81   689.9 3572.81   737.9 3591.94     786 3606.57   870.8 3629.62
#Mann= 6 ,-1 , 0
       0     .06       0   405.3    .045       0   432.4     .06       0
  432.57      .1       0  498.53     .06       0  601.06      .1       0
Bank Sta=405.3,432.4
XS Rating Curve= 0 ,0
Exp/Cntr=0.3,0.1

Type RM Length L Ch R = 1 ,94023   ,295,300,307.7
XS GIS Cut Line= 3
     2387706.676      636675.977     2388054.178      636464.014
     2388407.096      636224.842
#Sta/Elev= 30
       0 3589.25     9.5  3587.9    42.2 3578.77   117.3 3560.37     150 3557.51
   210.9 3556.25   268.6  3552.2   274.4 3550.36     289 3541.17   299.9 3537.66
   324.7 3535.42     385 3532.98   393.4 3528.27   402.5 3526.92   423.3 3527.98
   430.4  3529.3   468.7 3529.53   499.5 3531.48   509.1 3536.65   523.1 3548.94
   528.5 3552.23   547.9 3556.67   572.4 3568.22   605.8 3580.56   620.3 3587.48
     659 3602.19   673.2 3608.99   697.7 3617.13   736.3 3627.08   833.4 3646.42
#Mann= 6 ,-1 , 0
       0      .1       0  306.61      .1       0  377.02     .06       0
   393.4    .045       0   423.3     .06       0   545.2      .1       0
Bank Sta=393.4,423.3
XS Rating Curve= 0 ,0
Exp/Cntr=0.3,0.1

Type RM Length L Ch R = 1 ,93723   ,297.8,300,304.9
XS GIS Cut Line= 3
     2387781.567      636800.232      2388218.89      636699.041
     2388613.675      636620.352
#Sta/Elev= 30
       0 3596.06    91.5 3568.83   124.4 3561.07   153.1 3550.75   182.1 3543.03
   198.3 3540.94   231.1 3533.47     264 3531.74   280.4 3527.17   313.2 3528.61
   345.5 3526.93   366.6 3527.77   399.5 3523.58   428.2 3522.31   435.5 3520.58
   444.6 3519.49   470.1 3520.87   477.3 3523.07   505.8 3526.85     514 3531.39
   546.6 3554.37     567 3564.69   599.6 3575.95     616 3579.35   636.3  3588.2
   680.1 3601.93   701.6 3612.55   734.6 3625.46   779.6 3634.96   851.4 3646.48
#Mann= 5 ,-1 , 0
       0      .1       0   395.3     .06       0   435.5    .045       0
   470.1     .06       0  494.77      .1       0
Bank Sta=435.5,470.1
XS Rating Curve= 0 ,0
Exp/Cntr=0.3,0.1

Type RM Length L Ch R = 1 ,93423   ,280.7,282.5,285.3
XS GIS Cut Line= 3
 2387774.1085383 637015.83796594     2388182.188      636992.624
      2388603.04      636973.915
#Sta/Elev= 30
       0 3623.16    12.7  3617.6    68.7 3599.66    84.9 3594.83   104.8 3591.21
   140.9 3580.15     197 3557.44     217 3544.03     245 3528.92   266.9 3526.08
   353.2 3524.97   381.3 3521.03   385.3 3519.71     392 3514.72   409.3 3513.11
   420.1 3515.02   485.4 3519.72   537.4 3516.56   565.5 3516.53   581.5 3518.14
   593.5 3521.83   613.5 3537.02   633.5 3541.39   645.5  3542.6   677.6 3550.13
   729.1 3554.93   765.6 3565.83   788.8 3570.44   813.7 3573.18     830 3572.14
#Mann= 5 ,-1 , 0
       0      .1       0     392    .045       0   420.1      .1       0
  438.71     .06       0  638.69      .1       0
#XS Ineff= 2 , 0
                          489.02         3524.92
Permanent Ineff=
       F       F
Bank Sta=392,420.1
XS Rating Curve= 0 ,0
Exp/Cntr=0.3,0.1

Type RM Length L Ch R = 1 ,93141   ,327.6,317.5,298.9
XS GIS Cut Line= 3
      2387807.68      637222.0232388430.54674049637291.219395747
     2388631.203      637124.533
#Sta/Elev= 30
       0 3616.19    99.7 3605.39   168.1 3589.19   204.3 3576.24   220.4 3572.58
   244.6 3563.32   275.2 3548.33   304.9 3530.59   325.9 3520.94   341.2 3517.77
   369.3    3517   381.4 3511.98   389.4 3511.95   394.8 3509.31   401.5 3507.32
   423.7 3509.12   433.7 3511.31     478 3508.88   490.1 3511.58   521.5 3513.14
   530.3 3512.73   542.4 3509.42   562.5 3509.94   582.6 3517.14   610.8 3510.91
   622.9  3511.2   642.6 3521.58   736.2 3534.09   858.8 3561.72   887.6 3566.82
#Mann= 5 ,-1 , 0
       0      .1       0   394.8    .045       0   423.7      .1       0
  555.82     .06       0  662.72      .1       0
#XS Ineff= 2 , 0
                          522.06         3515.19
Permanent Ineff=
       F       F
Bank Sta=394.8,423.7
XS Rating Curve= 0 ,0
Exp/Cntr=0.3,0.1

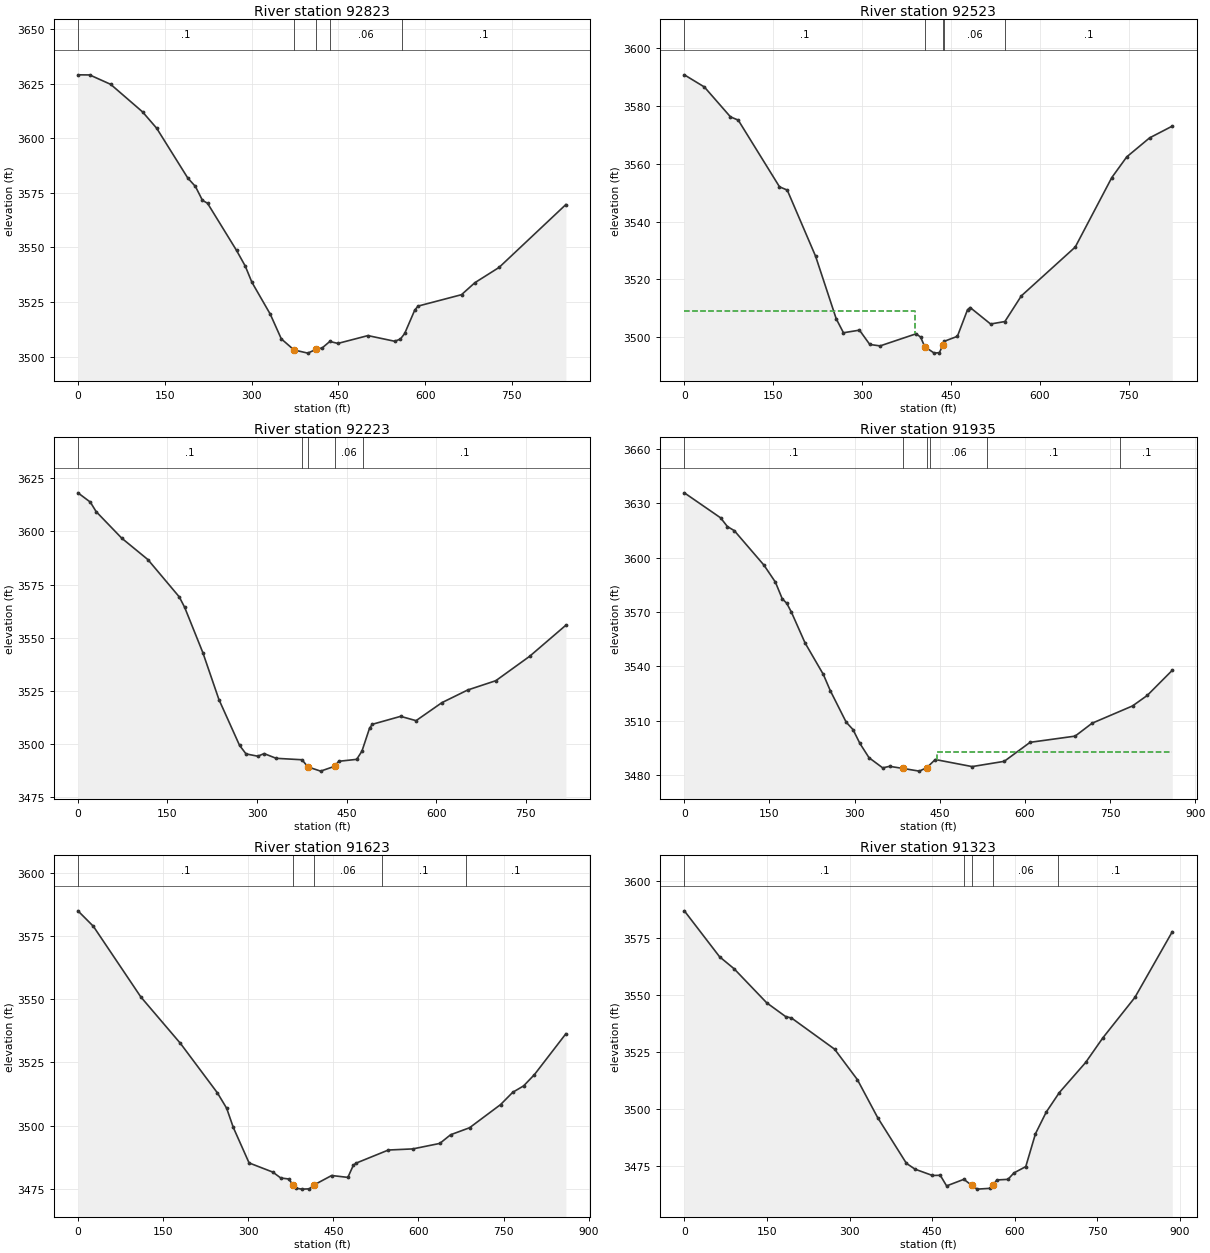
Type RM Length L Ch R = 1 ,92823   ,295,300,305.5
XS GIS Cut Line= 3
 2388105.4307787637813.551306362     2388359.835      637521.472
     2388675.785      637192.661
#Sta/Elev= 30
       0 3628.97    20.3 3628.92    56.6 3624.62   111.6 3612.04     136 3604.57
   189.9 3581.74     203 3577.93   215.2 3571.57     224 3570.22   274.1 3548.66
   289.2 3541.48   300.6 3534.12   332.4 3519.49   351.5 3508.19   373.5 3503.12
   397.3 3501.68     411 3503.35   422.3 3504.09   435.3 3507.02   449.3 3506.12
   501.2  3509.7   547.4 3507.11   557.3 3508.11   564.7 3510.66   582.1 3521.37
   587.8 3523.19   662.9 3528.41     686 3533.89   727.9 3540.89   843.3 3569.64
#Mann= 5 ,-1 , 0
       0      .1       0   373.5    .045       0     411      .1       0
  435.35     .06       0  559.59      .1       0
Bank Sta=373.5,411
XS Rating Curve= 0 ,0
Exp/Cntr=0.3,0.1

Type RM Length L Ch R = 1 ,92523   ,300.4,300,297.8
XS GIS Cut Line= 3
 2388219.1759638637831.638490287     2388602.751      637667.572
     2388978.195      637513.276
#Sta/Elev= 30
       0 3590.76    33.8 3586.55    77.8 3576.21    90.9 3575.09   160.5 3552.01
   173.6 3550.87   221.4 3527.98   256.2 3506.33   268.4  3501.5   295.4  3502.4
   312.8 3497.45   330.2 3496.95   391.1 3501.15   398.6 3499.97   405.5 3496.68
   421.5 3494.45   430.2 3494.63   436.1 3497.21   438.8 3498.57   460.6 3500.27
   477.7 3509.48   482.1 3510.24   516.6 3504.53   540.7 3505.38   568.5 3514.27
   659.4 3531.16   721.1 3555.22   746.3 3562.37   784.8 3568.94   823.1 3573.01
#Mann= 5 ,-1 , 0
       0      .1       0   405.5    .045       0   436.1      .1       0
   438.8     .06       0   540.7      .1       0
#XS Ineff= 2 , 0
          389.12  3509.1
Permanent Ineff=
       F       F
Bank Sta=405.5,436.1
XS Rating Curve= 0 ,0
Exp/Cntr=0.3,0.1

Type RM Length L Ch R = 1 ,92223   ,282,288.5,294.6
XS GIS Cut Line= 3
2388327.88373259 638112.39019778     2388697.865      637945.978
      2389079.03      637789.993
#Sta/Elev= 30
       0  3618.1    20.7 3613.75    30.5 3609.27    73.3 3596.82   117.2 3586.74
   169.8  3569.2   178.8 3564.31   209.3 3543.01   236.2 3521.01   270.7 3499.51
   281.6 3495.46   301.4 3494.38   311.9 3495.61   332.1 3493.39   375.4 3492.71
   385.3 3489.35   406.6 3487.37   430.2 3489.66   436.9 3491.99     467  3492.9
   475.8 3496.75   488.5 3507.49   493.1 3509.36   540.6  3513.1   566.5 3511.08
   609.8 3519.54     653 3525.48   700.1 3529.85   756.7 3541.29   817.5 3555.92
#Mann= 5 ,-1 , 0
       0      .1       0  375.95     .06       0   385.3    .045       0
   430.2     .06       0  478.15      .1       0
Bank Sta=385.3,430.2
XS Rating Curve= 0 ,0
Exp/Cntr=0.3,0.1

Type RM Length L Ch R = 1 ,91935   ,326.4,311.5,289.1
XS GIS Cut Line= 3
     2388383.303      638262.697 2388899.7239362638206.047746801
     2389155.488      637981.717
#Sta/Elev= 30
       0 3635.77    63.8 3621.98    75.9 3617.13      88 3614.89   140.3 3595.82
   160.4 3586.47   172.5 3577.25   180.4 3574.78   188.6 3569.89   212.7 3552.86
   244.9 3535.46   257.2 3526.48   285.1 3509.12   297.2    3505   309.3 3497.37
   325.4 3489.47   349.5 3483.87   361.6 3484.72   385.7 3483.53   413.9 3482.07
   427.2 3483.98   442.1 3488.48     507 3484.58   563.6 3487.48   609.2 3497.98
   688.5  3501.4   718.4 3508.53   789.6 3518.07   815.5 3523.85   859.7 3537.77
#Mann= 6 ,-1 , 0
       0      .1       0   385.7    .045       0   427.2      .1       0
  432.37     .06       0  534.01      .1       0  768.35      .1       0
#XS Ineff= 2 , 0
                          444.64         3492.54
Permanent Ineff=
       F       F
Bank Sta=385.7,427.2
XS Rating Curve= 0 ,0
Exp/Cntr=0.3,0.1

Type RM Length L Ch R = 1 ,91623   ,297.8,300,305.9
XS GIS Cut Line= 3
2388751.13063232638766.323465187      2388950.79       638429.46
     2389205.316      638036.374
#Sta/Elev= 30
       0  3584.9    27.2 3578.78   110.9 3550.84   180.7 3532.48   245.8 3512.93
   262.1 3506.86   273.7 3499.32   301.6 3485.25   343.4 3481.62   357.4  3479.3
   371.3  3478.9   378.8 3476.65   384.7 3475.24   394.6 3474.89   407.9    3475
   416.6 3476.61   447.1 3480.27   475.7 3479.53   485.2 3484.25     490 3485.15
   547.1 3490.35   590.2 3490.79   637.7 3492.96   656.7 3496.38   690.1 3499.15
   744.8 3508.31   766.3 3513.18   785.4  3515.7   804.5 3520.17   859.9 3536.31
#Mann= 5 ,-1 , 0
       0      .1       0   378.8    .045       0   416.6     .06       0
  536.11      .1       0  684.16      .1       0
Bank Sta=378.8,416.6
XS Rating Curve= 0 ,0
Exp/Cntr=0.3,0.1

Type RM Length L Ch R = 1 ,91323   ,295.9,300,313.5
XS GIS Cut Line= 3
     2388825.576      638820.476     2389232.047      638480.006
2389496.19537046638241.372607215
#Sta/Elev= 30
       0 3586.75    64.1  3566.6    90.2 3561.41   149.6 3546.46   184.1 3540.41
   194.6 3539.81   272.9 3526.15   314.3  3512.8   351.1 3496.18   403.3 3476.15
     419 3473.59   450.6 3470.83   464.8 3470.91   476.3 3466.26   507.7 3469.15
   521.6 3466.55   531.9 3464.85   555.8  3465.2   560.8 3466.77   567.7 3468.87
   587.8 3469.13   598.5 3471.93   620.1 3474.72   637.7 3489.11   657.2 3498.57
   681.1 3507.16   728.8 3520.32   760.3 3531.18   818.3 3548.83   886.2  3577.6
#Mann= 5 ,-1 , 0
       0      .1       0  508.44     .06       0   521.6    .045       0
   560.8     .06       0  679.52      .1       0
Bank Sta=521.6,560.8
XS Rating Curve= 0 ,0
Exp/Cntr=0.3,0.1