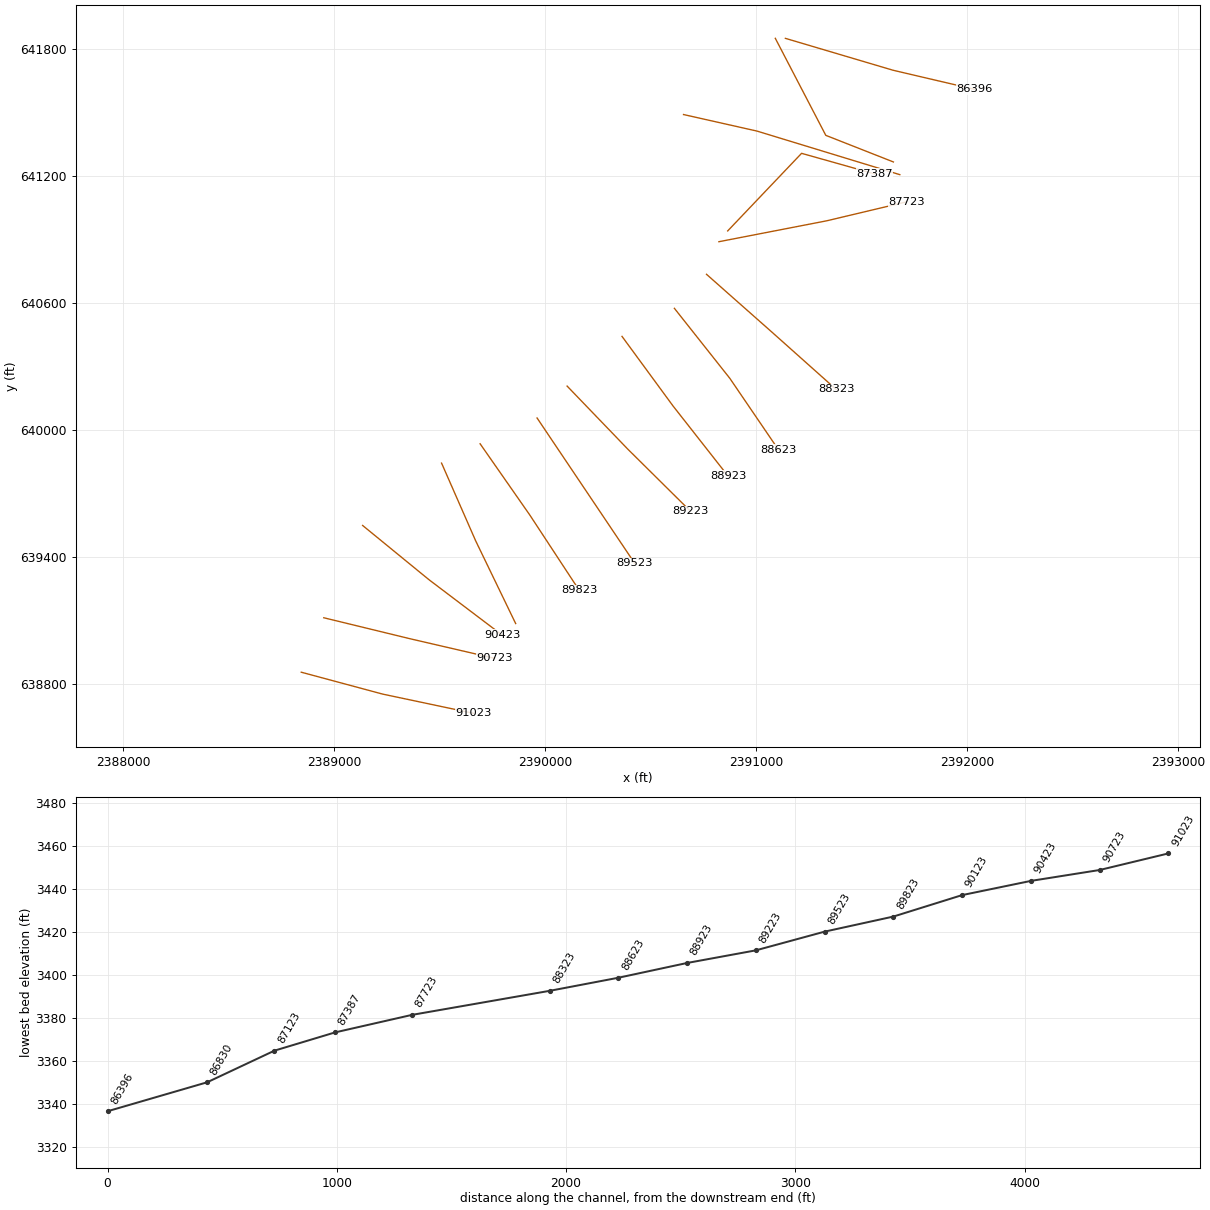
HEC-RAS study SENECACK.prj: SENECACK

--- SENECACK.g03 (geometry) --- (continued)

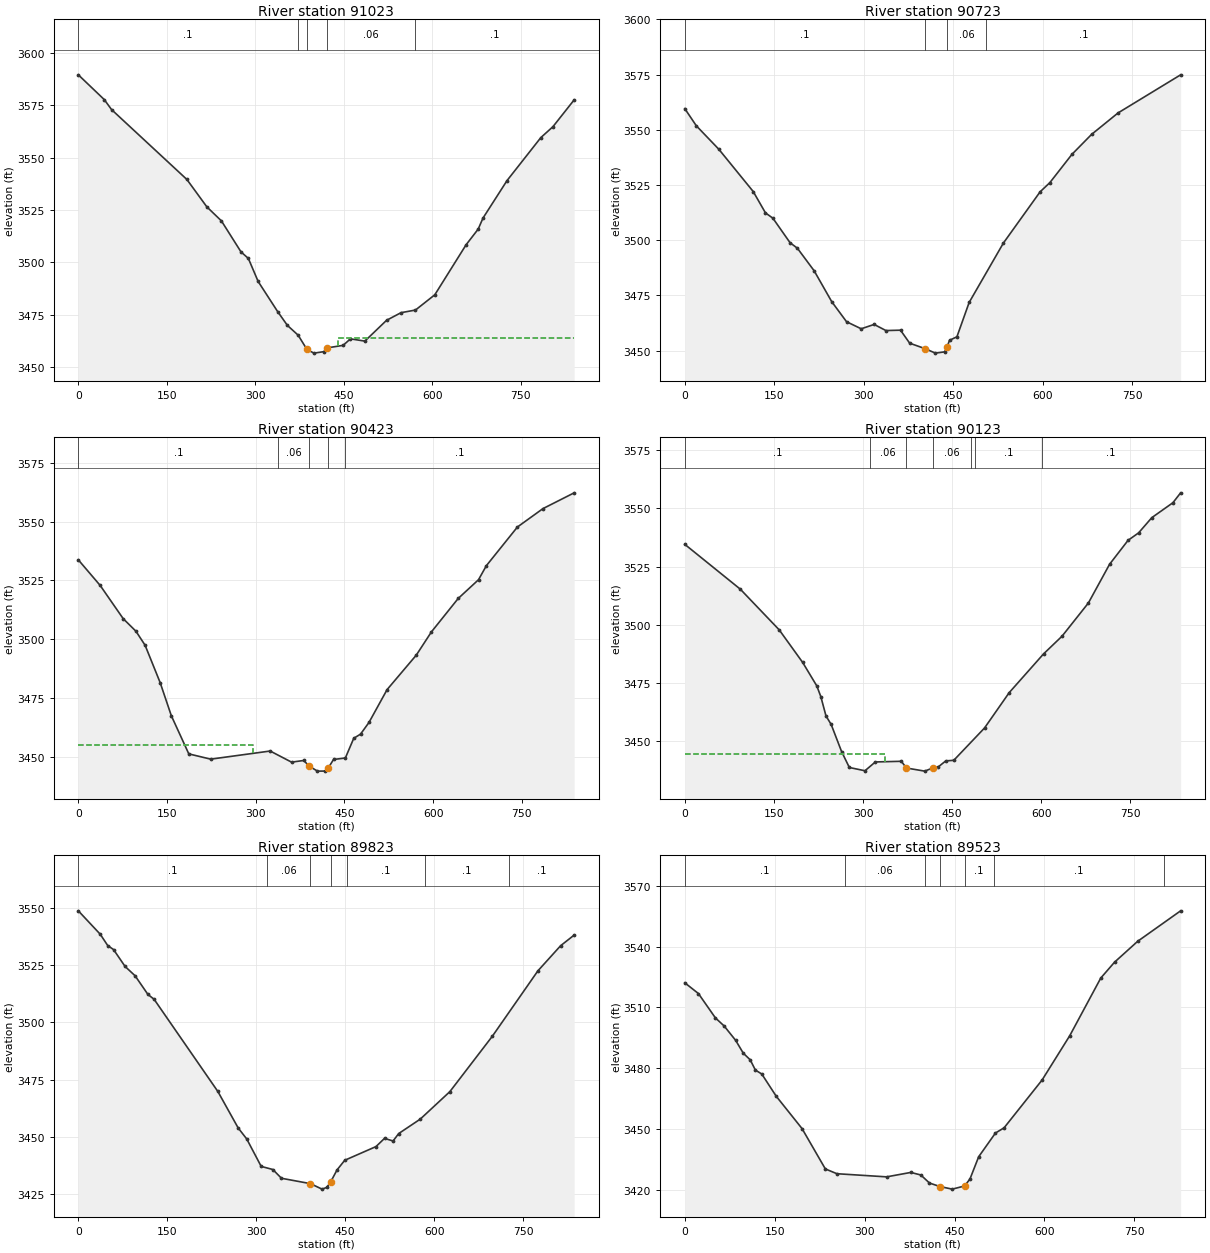
Type RM Length L Ch R = 1 ,91023   ,296.1,300,295.9
XS GIS Cut Line= 3
2388844.27893315638857.836030651     2389229.501       638754.63
     2389661.979      638663.511
#Sta/Elev= 30
       0  3589.5      44 3577.66    56.4 3572.88   184.1 3539.51   217.9 3526.44
   242.6 3519.74   275.9  3504.9   288.3 3501.81   304.9  3490.8     338  3476.4
   354.5 3469.81   372.7 3465.15   387.7 3458.31   399.6 3456.56   416.3 3457.26
   421.5 3459.04   449.1 3460.28   461.4 3463.38   485.9  3462.3   522.7 3472.24
   547.2 3475.88   571.7 3477.14   604.5 3484.43   657.6 3508.34   678.1 3515.82
   686.2 3521.07     727    3539   784.3 3559.52   804.8 3564.72   840.8 3577.54
#Mann= 5 ,-1 , 0
       0      .1       0   372.7     .06       0   387.7    .045       0
   421.5     .06       0   571.7      .1       0
#XS Ineff= 2 , 0
                             441            3464
Permanent Ineff=
       F       F
Bank Sta=387.7,421.5
XS Rating Curve= 0 ,0
Exp/Cntr=0.3,0.1

Type RM Length L Ch R = 1 ,90723   ,306.3,300,291.9
XS GIS Cut Line= 3
     2388951.234      639114.681     2389360.674      639015.466
2389760.25593315638923.342231206
#Sta/Elev= 30
       0 3559.62    19.3 3551.85    57.1  3541.2   114.7 3522.07   135.3 3512.37
   147.7 3509.98   176.5 3498.87   188.8 3496.37   216.9 3486.15   246.4 3472.15
   271.2 3463.08   295.8 3459.88   317.5 3461.85   337.3 3459.07   361.7 3459.25
   377.1 3453.35   402.8 3450.89   420.2 3448.85   435.7 3449.42   439.8  3451.7
   443.9 3454.67   456.3 3456.25   476.8 3471.81   534.2 3498.71   595.8 3521.93
   612.2 3526.11   649.2 3538.91     682 3547.92   726.5 3557.67   831.4 3574.93
#Mann= 4 ,-1 , 0
       0      .1       0   402.8    .045       0   439.8     .06       0
  505.58      .1       0
Bank Sta=402.8,439.8
XS Rating Curve= 0 ,0
Exp/Cntr=0.3,0.1

Type RM Length L Ch R = 1 ,90423   ,309.4,300,290.8
XS GIS Cut Line= 3
     2389135.188      639550.184      2389449.52      639294.263
     2389795.344      639033.579
#Sta/Elev= 30
       0 3533.75    36.9 3522.86    75.9 3508.69    97.4 3503.36   112.9 3497.38
   138.3 3481.51   157.3 3467.34   186.8 3451.12   223.8 3448.88   324.4 3452.34
   360.5 3447.61   381.1 3448.31   390.4 3445.91   404.3 3443.78   417.6  3443.8
   422.9 3445.23   431.5 3448.74   451.5 3449.37   465.7 3457.76   477.2 3459.54
   491.5 3464.52   522.1  3478.5   571.4 3493.16   597.1 3503.09   642.3  3517.3
   676.7  3525.3     690 3531.28   742.5 3547.74   785.6 3555.56   838.4 3562.29
#Mann= 5 ,-1 , 0
       0      .1       0  338.07     .06       0   390.4    .045       0
   422.9     .06       0  451.72      .1       0
#XS Ineff= 2 , 0
          295.63 3454.82
Permanent Ineff=
       F       F
Bank Sta=390.4,422.9
XS Rating Curve= 0 ,0
Exp/Cntr=0.3,0.1

Type RM Length L Ch R = 1 ,90123   ,294.6,300,300.6
XS GIS Cut Line= 3
2389509.15880721639844.424737863      2389670.47      639478.241
     2389860.217      639087.343
#Sta/Elev= 30
       0 3534.51    93.5 3515.26     159 3497.79   198.4 3483.84   222.2 3473.76
     229 3469.16   237.7 3460.86   246.4 3457.22   263.9  3445.6     277 3438.74
   303.3 3437.34   320.8 3441.12   364.5  3441.4   373.2 3438.51   403.9 3437.18
   417.8 3438.57   426.1 3438.87   439.4 3441.58   452.8 3441.82   504.6  3455.7
   546.1 3470.86   603.9 3487.48   635.1  3495.1   679.5 3509.37   715.1 3525.96
   746.2 3536.23     764 3539.44   786.2 3545.97   821.8 3552.39   834.7 3556.62
#Mann= 7 ,-1 , 0
       0      .1       0  311.41     .06       0   373.2    .045       0
   417.8     .06       0  481.83      .1       0  488.84      .1       0
   600.5      .1       0
#XS Ineff= 2 , 0
          337.14 3444.47
Permanent Ineff=
       F       F
Bank Sta=373.2,417.8
XS Rating Curve= 0 ,0
Exp/Cntr=0.3,0.1

Type RM Length L Ch R = 1 ,89823   ,301.4,300,303.3
XS GIS Cut Line= 3
2389691.85136171639935.532212771     2389927.651       639598.83
     2390161.578       639243.88
#Sta/Elev= 30
       0 3548.73      37 3538.49    49.6 3533.55    59.4 3531.81    78.9 3524.42
    95.7 3520.38   117.4 3512.21   127.8  3510.1   235.3 3469.84   269.6  3453.9
     284 3449.11   308.4 3437.12     328 3435.77   342.6 3431.94   391.5 3429.59
     411  3427.2     419 3427.95   425.4 3430.28   436.3 3435.59   449.3  3439.8
     502 3445.78   516.4 3449.37   530.8 3448.22   540.3 3451.47   576.6 3457.76
   626.6 3469.78   698.4 3494.03   775.1 3522.54   813.4  3533.5   836.2 3538.14
#Mann= 7 ,-1 , 0
       0      .1       0  318.44     .06       0   391.5    .045       0
   425.4     .06       0  452.55      .1       0  584.26      .1       0
  726.82      .1       0
Bank Sta=391.5,425.4
XS Rating Curve= 0 ,0
Exp/Cntr=0.3,0.1

Type RM Length L Ch R = 1 ,89523   ,295.7,300,303.1
XS GIS Cut Line= 3
      2389961.63      640057.282     2390208.317      639691.759
2390424.30817024639371.532148955
#Sta/Elev= 30
       0  3522.1    22.7  3516.8    51.1 3504.75    65.6 3500.79    84.9 3493.65
    97.6 3487.32   109.1 3484.07   117.8 3478.98   128.4 3477.06   152.5 3466.08
   195.6 3450.09   234.5 3430.16   253.8  3427.8   336.7 3426.25   377.1 3428.44
   393.8 3427.17   408.2 3423.19   426.1 3421.43   446.2 3420.19   466.8 3421.75
   475.8 3425.23   490.3 3436.19   518.3 3447.91   532.7 3450.48   596.1 3474.09
   642.2 3495.95     694 3524.46     717  3532.3   755.6 3542.61   827.2 3557.65
#Mann= 7 ,-1 , 0
       0      .1       0  267.83     .06       0  400.87      .1       0
   426.1    .045       0   466.8      .1       0  515.26      .1       0
  799.89      .1       0
Bank Sta=426.1,466.8
XS Rating Curve= 0 ,0
Exp/Cntr=0.3,0.1

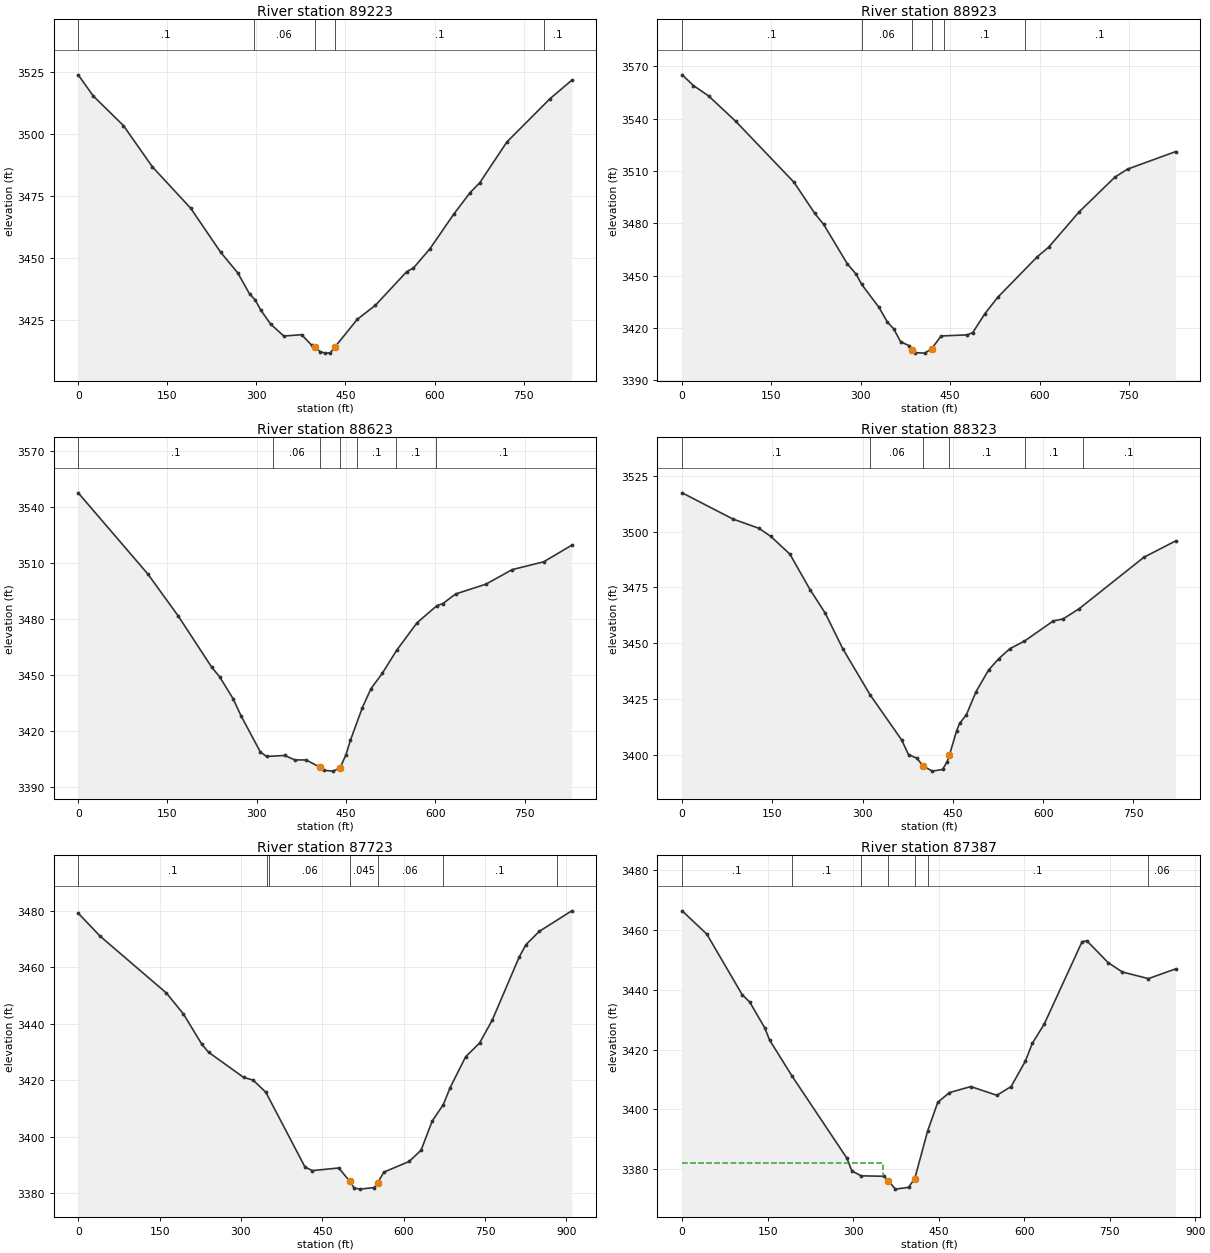
Type RM Length L Ch R = 1 ,89223   ,302.3,300,297.9
XS GIS Cut Line= 3
2390103.93555317640207.826617008     2390390.735      639911.044
     2390688.453      639617.364
#Sta/Elev= 30
       0    3524    25.3 3515.45    76.2 3503.47   124.9 3486.79   189.4 3470.06
     240 3452.22   268.6 3443.93   288.4 3435.45   297.6  3433.1   307.2 3428.96
   323.9 3423.23   346.2  3418.4   376.1 3418.95     393 3414.69   398.7 3414.01
   407.2 3412.11   415.7 3411.49   424.3 3411.58   432.6 3414.09   469.9 3425.17
   500.5 3430.87   553.2 3444.46   564.4 3445.89   592.5 3453.78   631.9 3467.56
   659.9 3476.42   675.9 3480.33   721.8 3496.88   794.6 3514.41   830.9  3521.8
#Mann= 5 ,-1 , 0
       0      .1       0  295.23     .06       0   398.7    .045       0
   432.6      .1       0  784.63      .1       0
Bank Sta=398.7,432.6
XS Rating Curve= 0 ,0
Exp/Cntr=0.3,0.1

Type RM Length L Ch R = 1 ,88923   ,300.2,300,300.3
XS GIS Cut Line= 3
     2390364.158      640442.215     2390605.735      640114.079
     2390866.349      639783.448
#Sta/Elev= 30
       0 3565.19      19 3559.05    44.3 3553.12    90.1 3538.49   187.9 3503.53
   222.7 3485.71   237.6 3479.41   277.3 3456.82   292.2 3450.85   301.2 3445.12
   330.4 3431.85   344.7 3423.37   355.2 3419.51   366.7 3412.17   381.6 3409.79
   386.6 3407.55   391.6  3405.9   407.5 3405.62     419 3408.24   434.9 3415.46
   478.8  3416.1   487.9 3417.44   508.3 3428.26   530.1 3437.74   596.5 3460.98
   615.3 3466.37   666.2 3486.53   726.6 3506.56   747.7 3511.12   828.5 3521.18
#Mann= 6 ,-1 , 0
       0      .1       0  302.16     .06       0   386.6    .045       0
     419     .06       0   440.2      .1       0     575      .1       0
Bank Sta=386.6,419
XS Rating Curve= 0 ,0
Exp/Cntr=0.3,0.1

Type RM Length L Ch R = 1 ,88623   ,296.4,300,303.4
XS GIS Cut Line= 3
     2390612.309      640574.525     2390874.947      640244.254
     2391104.868      639908.055
#Sta/Elev= 30
       0  3547.8   117.1 3504.29   168.2 3481.77   224.4 3454.37   237.8  3449.2
   260.2 3437.56   273.8 3428.25   306.1 3408.99   316.4 3406.61   347.1 3407.13
   363.8 3404.76   383.1 3404.73   405.7 3400.91   413.5 3399.16   428.5 3398.75
   440.1 3400.55     450 3407.59   457.3 3415.17   477.5  3432.8   491.9 3442.89
   510.8 3451.06     535  3463.4     569 3478.08   602.9 3487.44   612.6 3488.45
   634.2 3493.63   685.3 3498.91   728.9 3506.64   782.2 3510.86   829.3 3519.74
#Mann= 7 ,-1 , 0
       0      .1       0  327.82     .06       0   405.7    .045       0
   440.1     .06       0  468.23      .1       0   533.9      .1       0
  602.03      .1       0
Bank Sta=405.7,440.1
XS Rating Curve= 0 ,0
Exp/Cntr=0.3,0.1

Type RM Length L Ch R = 1 ,88323   ,583.2,600,628.6
XS GIS Cut Line= 3
     2390764.277      640735.325     2391076.186      640460.715
2391378.76517661640191.902374482
#Sta/Elev= 30
       0 3517.43    84.2 3505.71   127.8 3501.51   147.2 3497.94   179.2  3489.9
   212.5 3474.08   237.8 3463.51     267 3447.53   312.4 3426.88   364.8 3406.65
   376.3 3400.04   390.3 3398.43   400.2 3395.03   415.8 3392.66   432.8  3393.4
   440.4 3396.86   444.2 3399.82   456.4 3410.87   461.2 3414.05   472.5 3417.97
   488.5  3428.3   509.3 3437.96   526.3 3443.09   544.8 3447.57   568.9 3450.94
     617 3460.02     633 3460.87   659.8 3465.45   767.6 3488.56   820.3 3495.87
#Mann= 6 ,-1 , 0
       0      .1       0     313     .06       0   400.2    .045       0
   444.2      .1       0   569.7      .1       0  665.63      .1       0
Bank Sta=400.2,444.2
XS Rating Curve= 0 ,0
Exp/Cntr=0.3,0.1

Type RM Length L Ch R = 1 ,87723   ,323.4,336,350.1
XS GIS Cut Line= 3
     2390823.141       640888.96     2391333.381      640987.483
     2391712.907      641077.215
#Sta/Elev= 30
       0 3479.11    40.3 3470.98   162.6 3450.85     194 3443.43   227.7 3432.78
   240.3 3429.91   305.1 3420.98   322.3 3420.07   345.9 3415.74   417.9 3389.34
   431.4 3388.04   480.3 3388.97   500.7 3384.22   508.8 3381.89   519.7 3381.49
   545.7 3382.05   551.9 3383.74   563.5 3387.51   610.1 3391.28     632 3395.27
   652.6  3405.6     673 3411.41   685.5 3417.37   714.2 3428.32   739.7 3433.16
     763 3441.19   812.8 3463.56   825.2 3467.94   849.9 3472.67   909.7 3479.93
#Mann= 7 ,-1 , 0
       0      .1       0  347.33      .1       0  352.35     .06       0
   500.7    .045       0   551.9     .06       0  672.15      .1       0
  882.69     .06       0
Bank Sta=500.7,551.9
XS Rating Curve= 0 ,0
Exp/Cntr=0.3,0.1

Type RM Length L Ch R = 1 ,87387   ,274.6,264,222.3
XS GIS Cut Line= 3
2390864.80750562 640939.881612742391214.83827082641306.013627017
2391560.78699996641208.959936184
#Sta/Elev= 30
       0 3466.48    43.3 3458.68   105.3 3438.42   118.6 3435.94     145 3427.28
   153.4 3423.23   193.1 3411.09   289.2 3383.63   297.7 3379.42   314.1 3377.78
   354.3 3377.63   361.7 3376.13   374.1 3373.33   397.1 3373.92   408.1 3376.88
   430.7 3392.81   448.5 3402.41     469 3405.65   506.5 3407.65   552.1 3404.74
   577.1 3407.66     602 3416.13   614.4 3422.16   635.2 3428.56   701.7 3456.19
     710 3456.44   747.4 3449.14   772.3    3446     818 3443.79   865.8 3447.05
#Mann= 7 ,-1 , 0
       0      .1       0   193.1      .1       0   314.1     .06       0
   361.7    .045       0   408.1     .06       0   430.7      .1       0
     818     .06       0
#XS Ineff= 2 , 0
           351.5    3382
Permanent Ineff=
       F       F
Bank Sta=361.7,408.1
XS Rating Curve= 0 ,0
Exp/Cntr=0.3,0.1

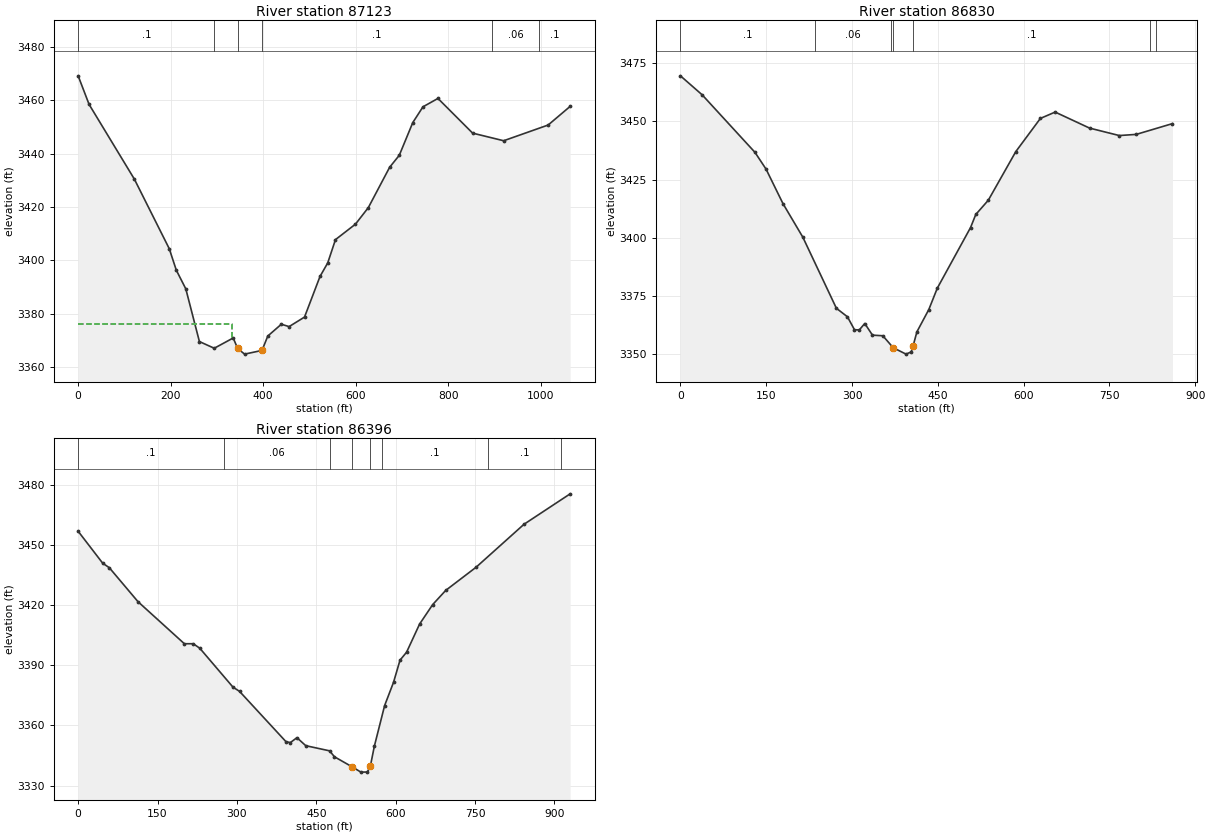
Type RM Length L Ch R = 1 ,87123   ,301.4,293.7,255.1
XS GIS Cut Line= 3
       2390655.6      641489.027     2391003.799      641410.915
     2391680.288      641205.372
#Sta/Elev= 30
       0 3469.12    23.7  3458.4   121.6 3430.41   196.9  3404.4   212.3 3396.29
   232.8 3389.31   262.2 3369.57   294.3 3367.06   335.3 3370.91   344.9 3366.98
   359.9 3364.86   397.6 3366.25   410.1 3371.64   439.4 3376.06   456.1 3375.17
   489.5 3378.74     523 3393.97   539.7 3399.04   556.4 3407.75   599.7 3413.56
   627.5 3419.76   673.5 3434.85   694.4 3439.35   723.6 3451.61   745.6 3457.51
     778 3460.65     853 3447.65   920.1  3444.8  1016.3 3450.69  1063.9 3457.68
#Mann= 6 ,-1 , 0
       0      .1       0  294.81     .06       0   344.9    .045       0
   397.6      .1       0  895.67     .06       0  995.89      .1       0
#XS Ineff= 2 , 0
          331.65 3376.13
Permanent Ineff=
       F       F
Bank Sta=344.9,397.6
XS Rating Curve= 0 ,0
Exp/Cntr=0.3,0.1

Type RM Length L Ch R = 1 ,86830   ,426,434.2,454.1
XS GIS Cut Line= 3
2391090.43496594641848.5665489282391329.52977023641390.888997838
2391649.76884466641265.308385114
#Sta/Elev= 30
       0 3469.55      38  3461.4   130.3 3436.73   149.7 3429.53   179.3 3414.72
     214 3400.33   272.7 3369.82     292 3366.17   304.3 3360.63   312.7 3360.52
   322.3 3363.29   335.8 3358.29   353.9 3358.03   372.1 3352.88   394.5 3350.15
   403.5 3351.11   406.7 3353.57   413.5 3359.73   434.3 3369.28   449.1 3378.43
   507.3 3404.47   516.4 3410.06   538.3 3416.18   586.4 3437.04   629.4 3451.28
   655.2    3454   715.3 3447.13   767.3 3443.93   796.9 3444.42   860.3 3449.05
#Mann= 7 ,-1 , 0
       0      .1       0  234.98     .06       0  368.24      .1       0
   372.1    .045       0   406.7      .1       0  820.21     .06       0
  832.05      .1       0
Bank Sta=372.1,406.7
XS Rating Curve= 0 ,0
Exp/Cntr=0.3,0.1

Type RM Length L Ch R = 1 ,86396   ,324.4,322.1,317.8
XS GIS Cut Line= 3
2391138.23345954641848.4968659222391648.28593404641698.001812759
2392035.78893404641607.648812759
#Sta/Elev= 30
       0    3457    46.4 3441.04    58.9 3438.79   113.1 3421.82   200.7 3400.82
   217.5 3400.82   229.9 3398.56   292.5 3379.16     305 3377.02   392.6 3351.93
   400.9 3351.43   413.4 3353.89   430.1  3349.9   475.1 3347.32   484.3 3344.36
   517.7 3339.33   534.3 3336.69   546.6 3336.75   552.3 3339.88   559.7 3349.65
   579.1 3369.93   595.9 3381.52   608.2 3392.62   620.6 3396.59   645.2 3410.65
   669.9 3420.36   694.5 3427.45     752 3439.04   842.4 3460.47   929.7 3475.69
#Mann= 8 ,-1 , 0
       0      .1       0  274.86     .06       0  475.09      .1       0
   517.7    .045       0   552.3      .1       0  574.96      .1       0
  774.05      .1       0  912.21      .1       0
Bank Sta=517.7,552.3
XS Rating Curve= 0 ,0
Exp/Cntr=0.3,0.1