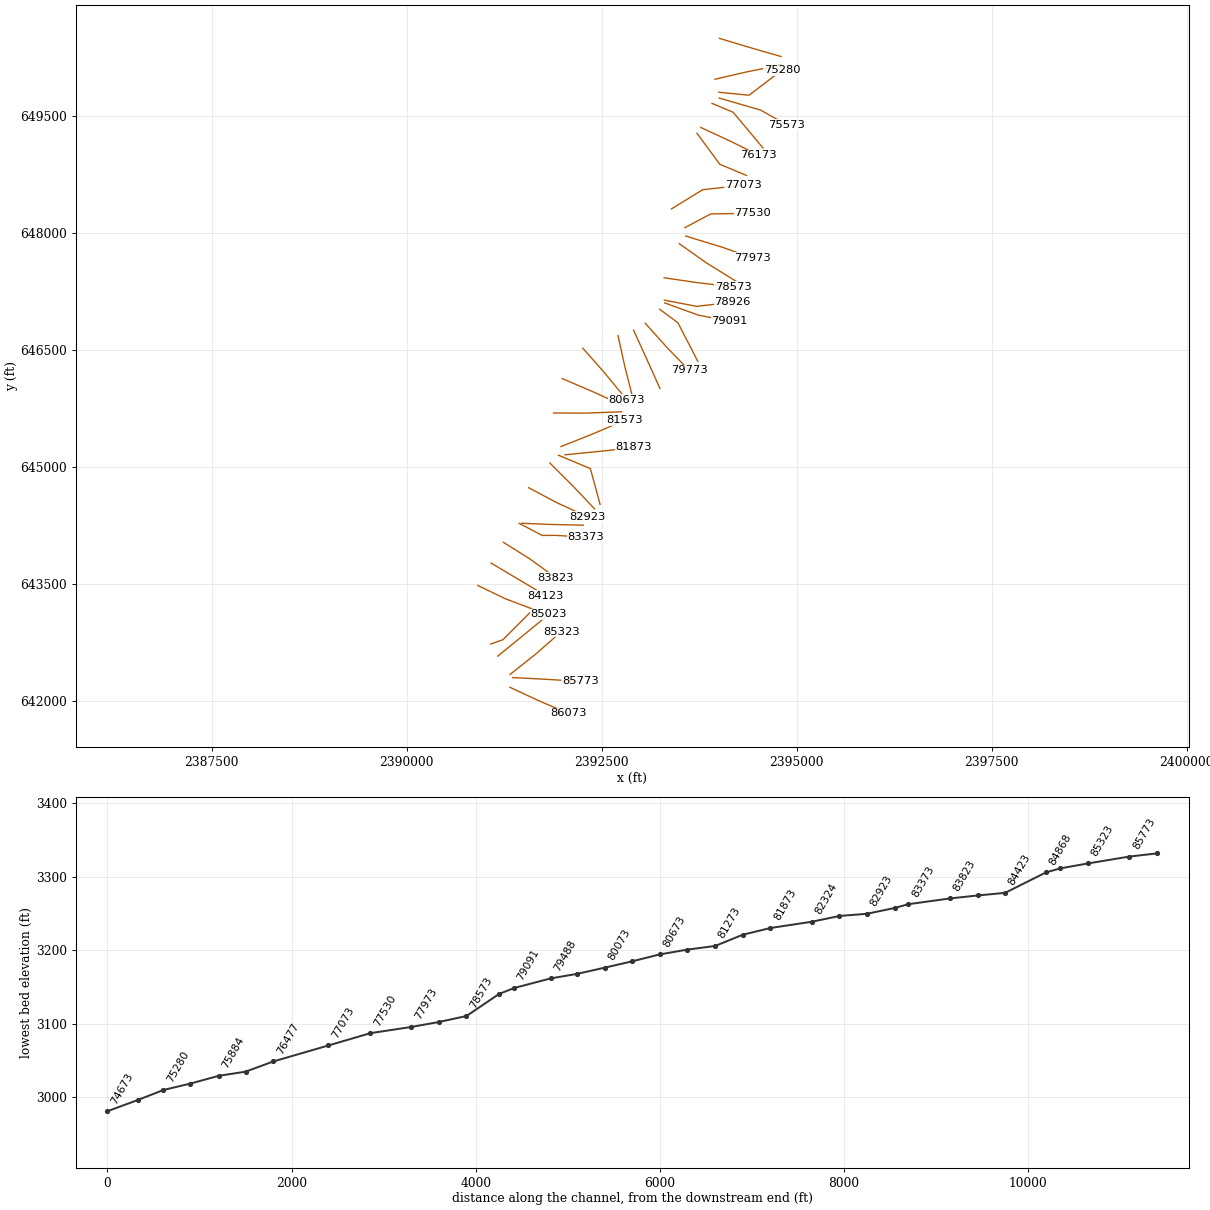
HEC-RAS study SENECACK.prj: SENECACK

--- SENECACK.g03 (geometry) --- (continued)

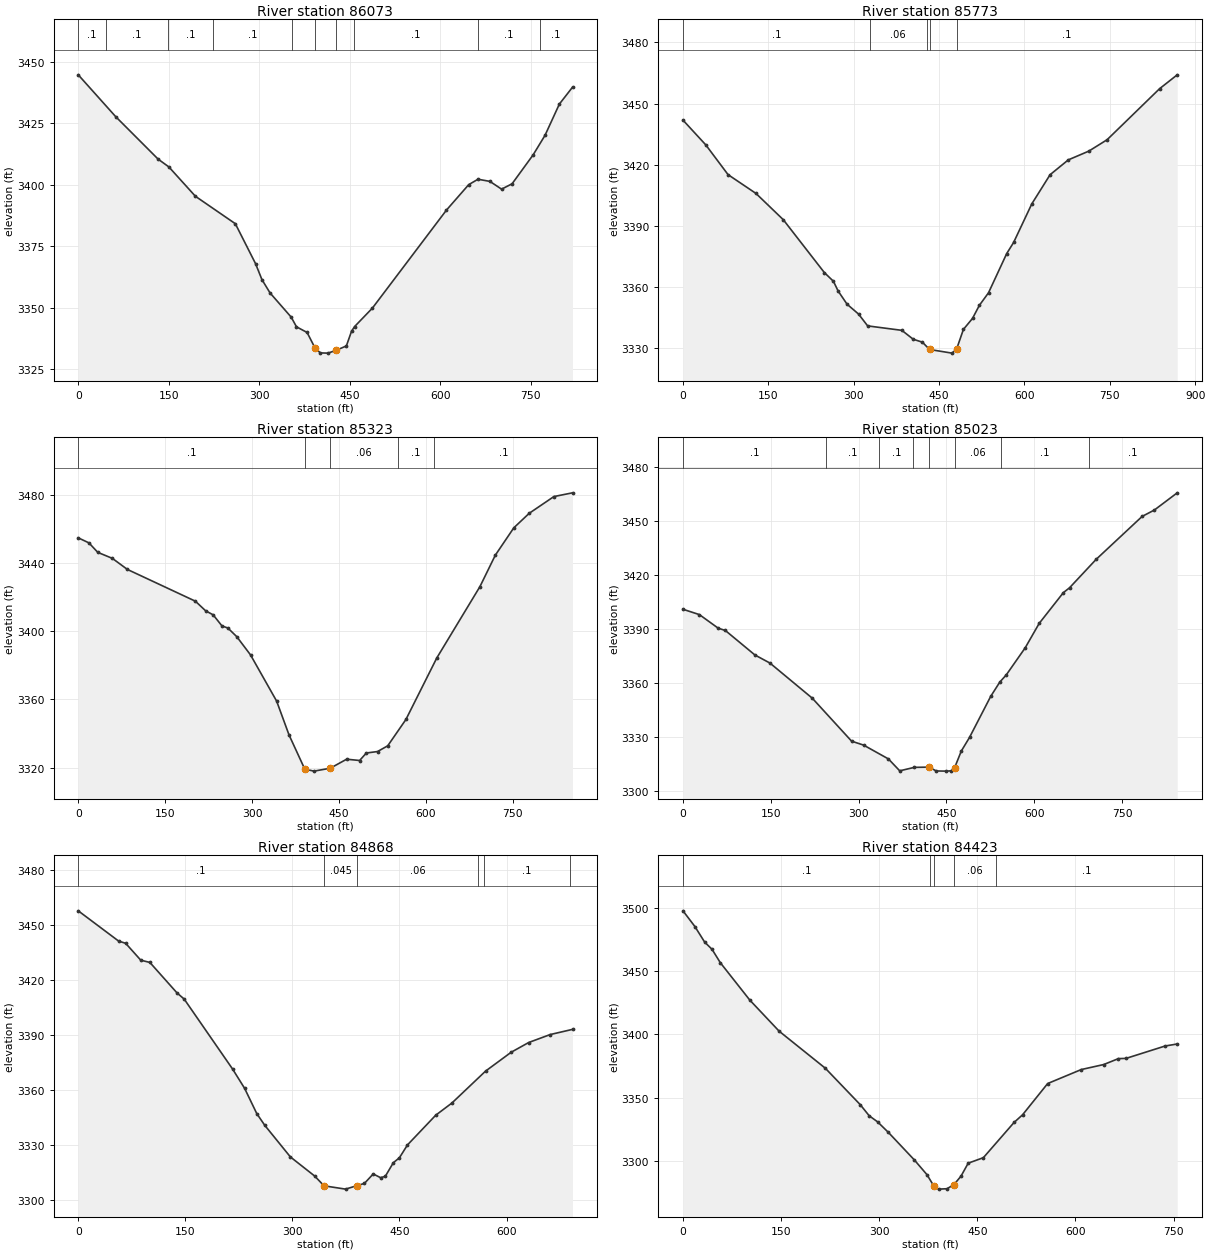
Type RM Length L Ch R = 1 ,86073   ,291.6,300,308.6
XS GIS Cut Line= 3
      2391322.55      642177.289     2391693.841      642004.748
     2392070.761      641843.038
#Sta/Elev= 30
       0 3444.62      62 3427.65   132.5 3410.36   150.2 3407.22   194.3 3395.28
   260.5 3384.13   294.1 3367.87   304.6 3361.42   318.1    3356   353.1 3346.19
   361.9 3342.25   379.5 3339.95   392.8 3333.56   401.6 3331.65   414.1 3331.56
   427.8 3332.71   444.6 3334.48   453.3 3340.52   458.3 3342.36   487.7 3349.83
   610.6 3389.67   647.5 3400.01   662.9  3402.2   682.6 3401.33     702 3398.18
   719.4 3400.35   754.3  3412.1     774 3420.02   797.8 3432.73   819.6 3439.59
#Mann= 10 ,-1 , 0
       0      .1       0   45.75      .1       0  148.93      .1       0
  223.33      .1       0  355.27     .06       0   392.8    .045       0
   427.8     .06       0  458.06      .1       0  662.79      .1       0
  765.15      .1       0
Bank Sta=392.8,427.8
XS Rating Curve= 0 ,0
Exp/Cntr=0.3,0.1

Type RM Length L Ch R = 1 ,85773   ,431.4,450,465
XS GIS Cut Line= 3
2391358.66033426642302.050855758     2391813.358      642278.417
2392225.72222469642252.259414705
#Sta/Elev= 30
       0 3441.83    40.1 3429.65    79.2 3415.03   128.3 3405.78   176.3 3392.86
   248.4 3366.89   264.4 3362.59   272.5 3357.87   288.3 3351.34   308.5 3346.49
   324.5 3340.67   384.6 3338.48   404.6  3334.1   420.7 3332.66   433.3 3329.07
   472.7 3327.28   480.7 3329.17   492.8 3338.96   508.8 3344.36   520.8 3350.77
   536.9 3356.95   568.9 3376.25     581 3381.69     613 3400.68   645.1    3415
   677.1 3422.29   713.2  3426.6   745.3  3432.2   837.5 3457.28   868.5  3464.1
#Mann= 5 ,-1 , 0
       0      .1       0  328.26     .06       0  428.17      .1       0
   433.3    .045       0   480.7      .1       0
Bank Sta=433.3,480.7
XS Rating Curve= 0 ,0
Exp/Cntr=0.3,0.1

Type RM Length L Ch R = 1 ,85323   ,299.1,300,299.8
XS GIS Cut Line= 3
2391324.32511234642342.298628293     2391650.126      642600.344
2391978.87568086642888.883127651
#Sta/Elev= 30
       0  3454.9    18.4 3451.96    33.7 3446.39    58.9 3442.85    84.8 3436.36
   202.1 3417.72     220 3412.02   232.8 3409.71     248 3403.21   258.2 3401.95
   273.5 3396.91   297.3 3386.18   342.4 3359.03   363.8 3339.16   390.9 3319.13
   406.8 3317.93   434.9 3319.63   463.2 3324.93   485.6 3324.17   497.2 3328.57
   516.5 3329.43   534.1 3332.79   565.5 3348.25   618.7 3384.33   693.2 3426.24
   719.8 3444.73   751.7 3460.79   778.3 3469.32   820.9 3479.15     853 3481.34
#Mann= 5 ,-1 , 0
       0      .1       0   390.9    .045       0   434.9     .06       0
  551.33      .1       0  614.37      .1       0
Bank Sta=390.9,434.9
XS Rating Curve= 0 ,0
Exp/Cntr=0.3,0.1

Type RM Length L Ch R = 1 ,85023   ,155.4,155.3,159.6
XS GIS Cut Line= 3
     2391167.525      642577.212     2391508.881      642855.471
     2391821.049      643111.661
#Sta/Elev= 30
       0 3401.07      28 3398.11    60.3 3390.54    72.3 3389.31   122.8 3375.71
   148.5 3371.22   220.9  3351.7     288 3327.86   308.6 3325.66   350.9    3318
   370.2  3311.4   395.2 3313.32   420.5 3313.45   432.5 3311.32   449.8 3311.23
   458.4 3311.41     464 3313.16   475.4 3322.38   489.4 3329.93   525.6 3352.71
   541.1 3360.64   552.2 3364.65   584.5 3379.66   608.4 3393.23   649.8 3410.34
   660.2 3412.97   705.6 3428.74   784.3 3452.62   805.2 3456.16   844.2  3465.7
#Mann= 8 ,-1 , 0
       0      .1       0  243.63      .1       0  335.59      .1       0
  393.21     .06       0   420.5    .045       0     464     .06       0
  543.17      .1       0  693.31      .1       0
Bank Sta=420.5,464
XS Rating Curve= 0 ,0
Exp/Cntr=0.3,0.1

Type RM Length L Ch R = 1 ,84868   ,465.3,444.7,423.3
XS GIS Cut Line= 3
2391076.20409772642731.9322652932391232.84589618642787.578329273
 2391604.8328571643159.639137028
#Sta/Elev= 30
       0  3457.5    56.6 3440.99    66.4  3439.8    87.6 3430.58   100.3 3429.37
   138.5 3412.68   148.4 3409.38   216.2 3371.23   233.1 3360.68   250.1 3346.93
   261.4 3340.49   297.2  3323.3   331.1 3312.92   344.3 3307.56   374.5 3305.75
   390.5 3307.66   400.9 3308.87   413.2 3314.02   423.5    3312   430.1  3312.7
   441.4 3320.16   449.9 3322.83   461.2 3329.85   500.8 3346.06   523.5 3352.71
   570.6  3370.1   606.5 3380.39     631 3385.69   661.1 3390.03   692.4 3392.86
#Mann= 6 ,-1 , 0
       0      .1       0   344.3    .045       0   390.5     .06       0
  560.04      .1       0  567.74      .1       0  688.55      .1       0
Bank Sta=344.3,390.5
XS Rating Curve= 0 ,0
Exp/Cntr=0.3,0.1

Type RM Length L Ch R = 1 ,84423   ,300.7,300,296.5
XS GIS Cut Line= 3
2390910.70685021 643483.08818169     2391265.655      643312.129
2391603.97857974643184.215510399
#Sta/Elev= 30
       0 3497.61    18.2 3485.22    33.1 3472.95    44.4 3467.24    57.1 3456.65
   102.2 3427.12     147  3402.6   217.6 3373.36   270.9 3344.65   284.8 3335.76
   297.5 3331.03   313.9 3322.76   353.8 3300.91     373 3289.34   383.7 3280.23
   390.7 3277.89   403.7  3278.2   414.3 3281.46   425.1 3288.14   436.1 3298.38
   459.3 3302.72   506.3 3330.58   519.2 3336.56   557.6 3361.25     609  3372.3
   643.2 3376.24   665.8 3380.93   677.4  3381.1   737.2 3390.89   755.7 3392.47
#Mann= 5 ,-1 , 0
       0      .1       0  377.17     .06       0   383.7    .045       0
   414.3     .06       0  478.89      .1       0
Bank Sta=383.7,414.3
XS Rating Curve= 0 ,0
Exp/Cntr=0.3,0.1

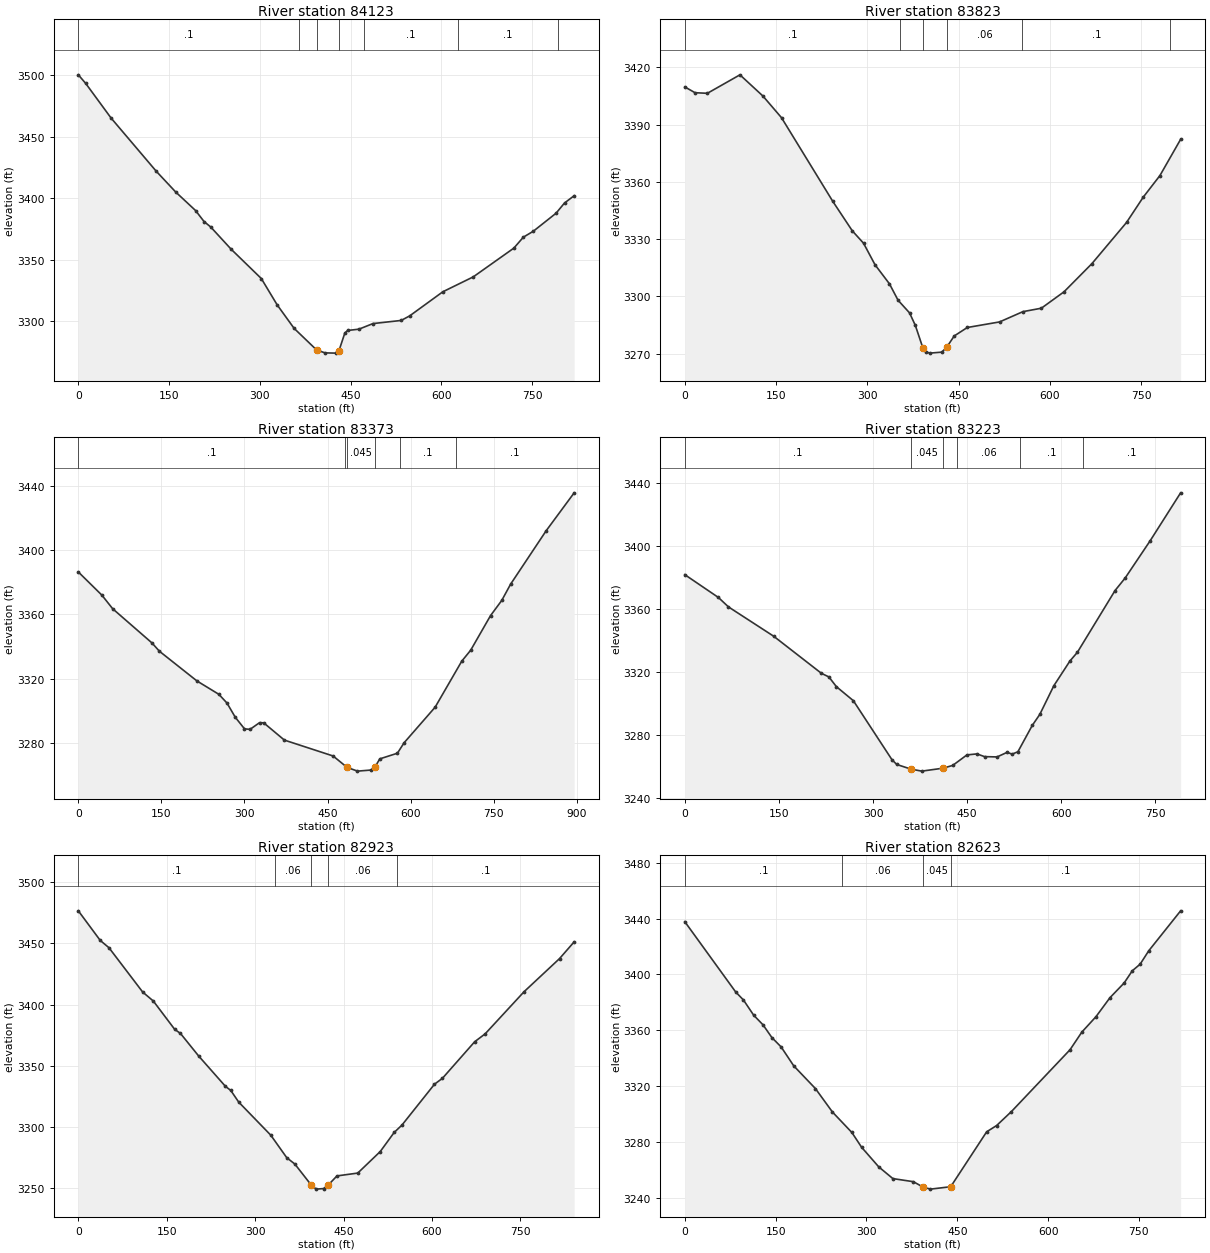
Type RM Length L Ch R = 1 ,84123   ,300.2,300,297.3
XS GIS Cut Line= 3
     2391080.221      643770.603     2391432.421      643561.359
     2391784.383      643352.044
#Sta/Elev= 30
       0 3500.22    12.2 3493.24    54.1 3465.14   128.6 3422.03   161.1 3404.98
   193.7 3390.06   207.7 3381.12   218.7 3376.71   252.6  3358.6   302.3 3334.88
   328.5 3313.49   356.5 3294.42   393.8 3276.82   407.7 3274.51   426.3 3274.31
   430.7  3276.4   440.3  3290.6   444.9 3292.69   463.6 3293.76   486.8  3298.3
   533.4 3300.84   547.4 3304.53   602.3 3324.13   652.5 3336.21   719.6 3359.56
   735.3 3368.46   751.7 3373.25   789.3 3387.88   803.3  3396.2   819.2 3402.08
#Mann= 7 ,-1 , 0
       0      .1       0  365.05     .06       0   393.8    .045       0
   430.7     .06       0  471.81      .1       0  626.64      .1       0
  792.11      .1       0
Bank Sta=393.8,430.7
XS Rating Curve= 0 ,0
Exp/Cntr=0.3,0.1

Type RM Length L Ch R = 1 ,83823   ,439.5,450,468.7
XS GIS Cut Line= 3
2391238.01037171 644037.28259362     2391578.543      643823.345
     2391912.349      643580.995
#Sta/Elev= 30
       0 3409.76    16.8 3406.72    37.1 3406.41    90.6 3416.09   128.4 3404.97
   158.9 3393.63   243.1 3349.82   275.2 3334.36   293.7 3327.85   312.6 3316.55
   336.3 3306.56   350.4 3297.99   369.3 3291.34   378.8 3284.79     391 3273.17
   395.5 3271.05   402.4 3270.26   422.2 3270.78   430.2 3273.28   442.7 3279.26
   464.2 3283.69   517.2 3286.61   555.6    3292   585.9  3293.8   623.1 3302.39
     669 3317.17   725.8 3338.72   753.4 3352.04   780.7 3363.31   814.7 3382.29
#Mann= 6 ,-1 , 0
       0      .1       0  353.84     .06       0     391    .045       0
   430.2     .06       0  554.85      .1       0  797.28     .12       0
Bank Sta=391,430.2
XS Rating Curve= 0 ,0
Exp/Cntr=0.3,0.1

Type RM Length L Ch R = 1 ,83373   ,154.5,150,154.7
XS GIS Cut Line= 4
     2391441.088       644279.712391737.48183574644124.234045654
     2391901.917      644125.906     2392297.223      644101.928
#Sta/Elev= 30
       0 3386.26    42.5 3371.86      62  3363.4   132.9 3342.16   146.4 3336.99
   214.2 3318.51   253.7 3310.22   268.4 3304.78   283.3 3295.98     300 3288.76
     310 3288.43   327.1 3292.57   334.7 3292.49     372 3281.76     460 3271.88
   485.1 3264.82     504 3262.47     528 3263.13   535.2 3264.85   544.3 3270.09
   576.1  3273.6   588.1 3280.07   644.2 3302.21   692.3 3330.83   708.4 3337.63
   744.2 3359.12   764.5 3368.58   780.5  3378.7   844.6 3411.85   895.2 3435.45
#Mann= 6 ,-1 , 0
       0      .1       0  481.56     .06       0   485.1    .045       0
   535.2     .06       0  581.54      .1       0  681.36      .1       0
Bank Sta=485.1,535.2
XS Rating Curve= 0 ,0
Exp/Cntr=0.3,0.1

Type RM Length L Ch R = 1 ,83223   ,305,300,290.3
XS GIS Cut Line= 3
2391473.24974341644280.651700414     2391859.994      644265.079
 2392263.2344785644255.758294035
#Sta/Elev= 30
       0 3381.79    53.5 3367.35    69.6 3361.36   141.6  3342.8   217.7  3319.3
   229.7 3316.98   241.7 3310.81   268.7 3301.93   330.2 3264.56   337.9 3261.51
     361 3258.52   377.8  3257.3   411.93259.172   427.1 3260.92   449.8 3267.59
   465.8 3268.21   477.8 3266.49   497.8  3266.3   513.8  3269.2   521.8 3268.08
     531 3269.57   553.9 3286.27   565.9 3293.23   588.3 3311.42   613.9 3327.05
   625.9 3332.63   685.9 3371.75   701.9 3379.62   741.9  3403.3   790.4 3433.64
#Mann= 6 ,-1 , 0
       0      .1       0     361    .045       0   411.9      .1       0
  433.83     .06       0   534.1      .1       0  634.36      .1       0
Bank Sta=361,411.9
XS Rating Curve= 0 ,0
Exp/Cntr=0.3,0.1

Type RM Length L Ch R = 1 ,82923   ,302.7,300,292.5
XS GIS Cut Line= 3
     2391562.331       644736.84     2391919.539      644547.032
     2392315.792       644363.12
#Sta/Elev= 30
       0 3476.63    37.2 3452.45      52  3446.5   109.2 3410.33   127.3 3402.97
   163.5 3379.88   173.3 3376.54   204.3 3358.05   249.6 3333.36   258.7 3329.98
   272.2 3320.46   326.6 3293.46   353.7 3275.08   367.4 3269.92   395.1 3252.86
   403.6 3249.43   416.1 3249.87   423.8 3252.65   438.9 3260.21   474.2 3262.54
   512.4 3280.14   535.9 3295.67   549.2 3301.73   604.4 3335.09   617.9 3339.92
   672.6 3369.76   690.3 3376.17   756.4  3410.6   816.6 3437.64   841.4  3451.3
#Mann= 5 ,-1 , 0
       0      .1       0  334.12     .06       0   395.1    .045       0
   423.8     .06       0  541.61      .1       0
Bank Sta=395.1,423.8
XS Rating Curve= 0 ,0
Exp/Cntr=0.3,0.1

Type RM Length L Ch R = 1 ,82623   ,309,299,284.5
XS GIS Cut Line= 3
2391835.19485298 645052.32059362     2392124.458      644764.452
     2392406.952      644466.287
#Sta/Elev= 30
       0 3437.79      84 3387.51    96.9 3381.73   113.8 3370.84   129.2 3363.96
   143.8 3354.86   159.1 3348.16   179.9 3334.62   215.7 3318.37   243.9 3301.55
   275.9 3286.94     292 3276.35   320.3 3262.33   343.6 3253.95   377.5 3251.73
   393.3 3247.91   405.7 3246.41   439.1 3248.13   498.5 3287.43   514.9  3291.9
   539.4 3301.92   636.2 3346.16   655.7 3358.79     679  3369.8   702.2 3383.44
   725.5 3393.91     739 3402.65   751.9 3407.36   766.2 3416.98   818.8 3445.55
#Mann= 4 ,-1 , 0
       0      .1       0  260.25     .06       0   393.3    .045       0
   439.1      .1       0
Bank Sta=393.3,439.1
XS Rating Curve= 0 ,0
Exp/Cntr=0.3,0.1

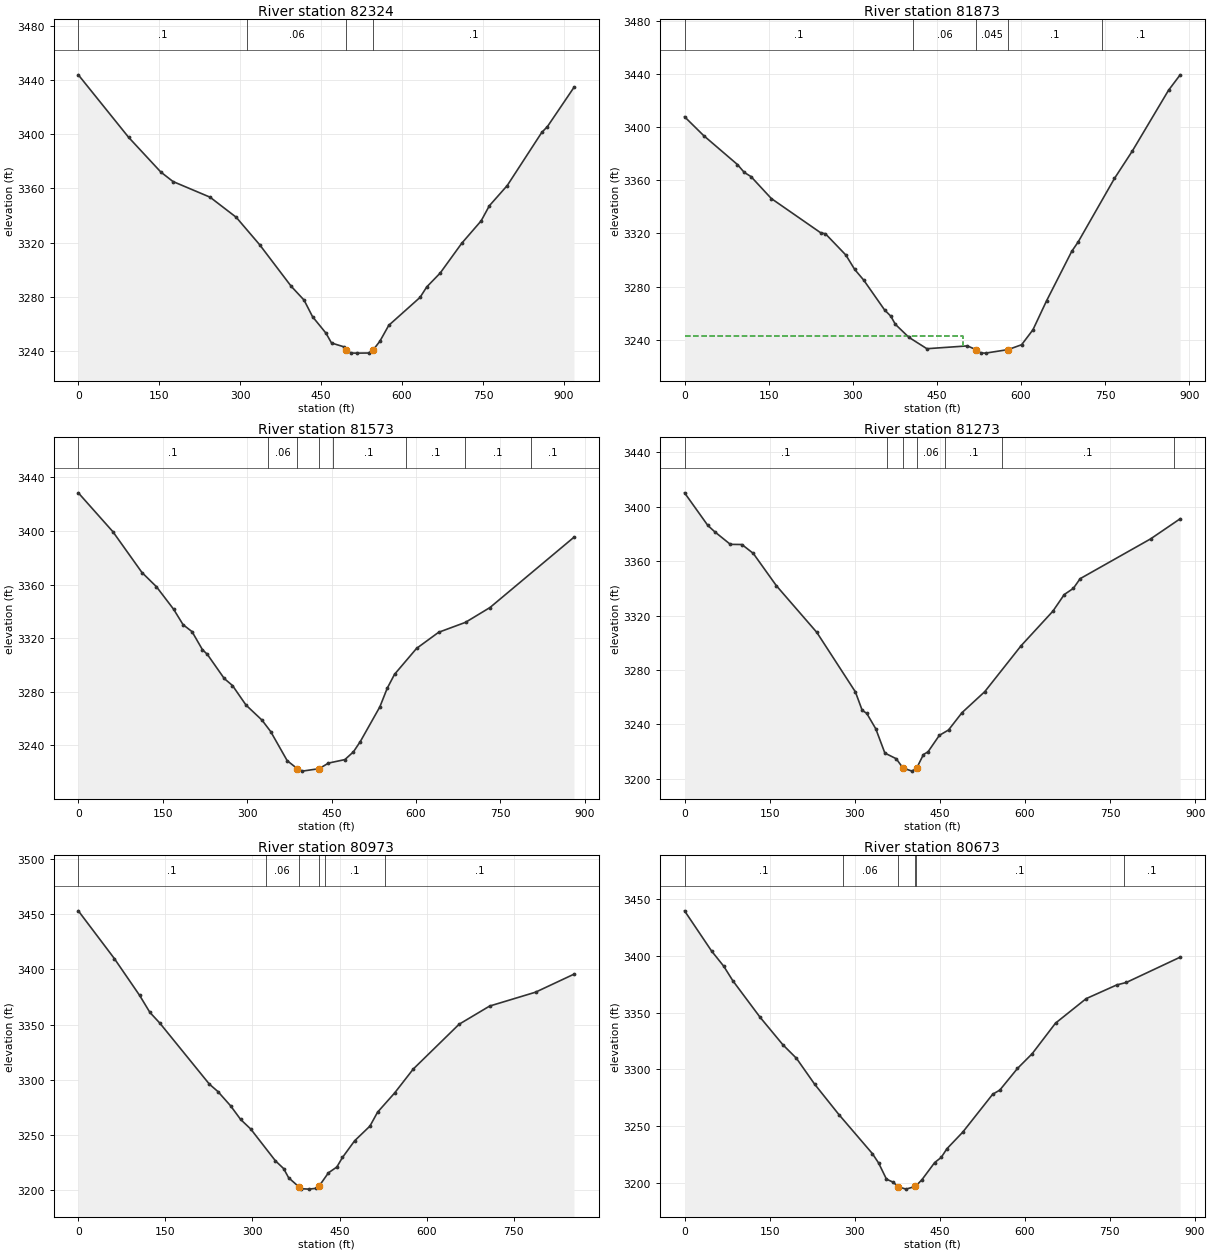
Type RM Length L Ch R = 1 ,82324   ,414.8,451,489.1
XS GIS Cut Line= 3
     2391944.895      645153.2122392354.51007212644981.579377257
     2392478.336      644523.528
#Sta/Elev= 30
       0 3443.71    93.1  3397.7   152.9 3372.06   175.5 3365.06   244.1 3353.54
   292.6 3338.74     336 3318.53   394.4 3287.93   418.4 3277.67   434.1 3265.47
     459 3253.31   469.3 3246.05   492.2 3243.25   496.6 3240.97   504.9 3238.65
   517.3 3238.59   538.1 3238.68   546.4 3240.93   558.8 3247.28   575.4 3259.08
   633.4 3279.68   645.8 3287.39   670.7 3297.61   710.7 3319.59   746.6 3336.07
   761.8 3347.19     795 3362.12   858.9 3401.22   869.5 3405.58   918.6 3434.43
#Mann= 4 ,-1 , 0
       0      .1       0  311.96     .06       0   496.6    .045       0
   546.4      .1       0
Bank Sta=496.6,546.4
XS Rating Curve= 0 ,0
Exp/Cntr=0.3,0.1

Type RM Length L Ch R = 1 ,81873   ,296.2,300,320.8
XS GIS Cut Line= 3
2392028.80911512645158.565585295     2392565.789      645212.114
2392907.35073786645253.193294035
#Sta/Elev= 30
       0 3407.75    34.1 3393.57    94.4 3371.78   106.5 3365.88   118.5 3362.75
   154.7 3346.26   242.9 3320.46   251.2 3319.75   287.6 3303.78   303.4 3292.93
   319.5  3284.9   356.6 3262.53   367.8 3257.81   375.8 3251.72   399.9 3241.94
   432.1 3233.35   504.4 3235.47   520.5 3232.47   528.5 3230.15   536.6 3230.03
   576.9 3232.68     601 3236.35   621.2 3247.59   645.4  3269.3   690.4 3306.58
   701.8  3313.6   766.5 3361.34   798.5 3382.04   862.9 3427.63   883.7 3439.26
#Mann= 5 ,-1 , 0
       0      .1       0  407.95     .06       0   520.5    .045       0
   576.9      .1       0  744.06      .1       0
#XS Ineff= 2 , 0
          496.59 3243.25
Permanent Ineff=
       F       F
Bank Sta=520.5,576.9
XS Rating Curve= 0 ,0
Exp/Cntr=0.3,0.1

Type RM Length L Ch R = 1 ,81573   ,304.4,300,295.9
XS GIS Cut Line= 3
2391977.53989043645264.652700415     2392364.539      645417.537
2392791.97722827645599.874102688
#Sta/Elev= 30
       0 3428.48    61.5 3399.45   113.1 3369.04   138.9  3358.4   169.4 3341.61
   186.2  3330.1   202.1 3324.92   220.6 3311.45   229.2 3308.02   259.3 3289.97
     274 3284.71   298.1  3270.1   326.4 3258.93   341.8 3250.42   371.2 3228.66
   389.2 3222.69     398 3220.86     428  3222.7   444.6 3226.86   473.7 3229.46
   488.9 3235.24   501.1  3242.9   535.9 3268.82     549 3282.71     562  3293.1
   601.1 3312.41   640.3 3324.43   688.1 3331.86   731.6 3342.91   880.8 3395.34
#Mann= 8 ,-1 , 0
       0      .1       0  336.25     .06       0   389.2    .045       0
     428     .06       0  452.43      .1       0  581.49      .1       0
  687.46      .1       0  804.98      .1       0
Bank Sta=389.2,428
XS Rating Curve= 0 ,0
Exp/Cntr=0.3,0.1

Type RM Length L Ch R = 1 ,81273   ,305.9,300,294.5
XS GIS Cut Line= 3
     2391881.681      645695.064     2392279.481      645692.567
     2392754.912      645710.096
#Sta/Elev= 30
       0 3410.31      41 3386.33    53.1  3381.7    80.7 3372.41   101.1 3372.29
   121.1 3365.78   161.9 3341.96   233.1 3307.68   301.1 3263.92   313.1 3250.35
   321.1 3248.12   337.1 3236.71   353.1 3218.89   373.1 3214.73   385.1 3207.85
   401.1 3205.61   409.1  3207.8   421.1 3217.83   429.1 3219.79   449.1 3231.92
   465.3 3235.87   489.1 3248.64   529.2 3264.07   593.2 3297.84   649.2 3323.24
   669.3  3335.5   685.3 3340.04   697.3 3347.17   821.4 3376.41   873.6 3391.23
#Mann= 7 ,-1 , 0
       0      .1       0  357.37     .06       0   385.1    .045       0
   409.1     .06       0  458.35      .1       0  559.64      .1       0
  863.51      .1       0
Bank Sta=385.1,409.1
XS Rating Curve= 0 ,0
Exp/Cntr=0.3,0.1

Type RM Length L Ch R = 1 ,80973   ,309.3,300,295.1
XS GIS Cut Line= 3
     2391993.711      646135.739     2392363.307      645977.458
     2392775.159       645792.08
#Sta/Elev= 30
       0 3453.13      62 3409.87   105.6  3376.4   123.3 3360.98   140.4 3351.27
   225.7 3295.93   240.5 3289.16   262.2 3276.31   279.6 3263.86     297 3255.18
   339.6  3226.3   353.6 3219.34   362.3 3210.97   379.7 3202.86     384 3201.05
   397.1 3200.67   409.6  3201.4   414.6 3203.32   430.8 3215.45   445.3 3220.74
     455 3229.41     476 3244.56   502.3 3257.85   515.5 3270.51   544.8 3287.87
   576.9 3309.59   655.9 3350.24   708.5 3366.74   787.5 3379.31   853.7 3395.65
#Mann= 6 ,-1 , 0
       0      .1       0  322.61     .06       0   379.7    .045       0
   414.6     .06       0  425.07      .1       0   527.9      .1       0
Bank Sta=379.7,414.6
XS Rating Curve= 0 ,0
Exp/Cntr=0.3,0.1

Type RM Length L Ch R = 1 ,80673   ,310.3,300,297
XS GIS Cut Line= 3
     2392255.699      646526.557     2392519.592      646229.048
     2392822.781      645861.493
#Sta/Elev= 30
       0 3439.77    47.7 3404.28    69.1  3390.9    85.1 3378.11   133.2 3345.85
   173.4 3321.58   197.4 3309.59   229.5 3286.73   272.2 3259.97   331.1  3225.6
   342.2 3217.27   356.1 3202.96   368.5 3200.14   375.9 3196.47   390.4 3194.16
   407.1 3196.54   418.5 3202.37   441.2 3217.65   452.6 3222.11   462.7 3229.79
   490.6 3244.43   543.5 3277.93     556 3281.57   587.1 3300.64   613.1 3313.68
   654.3 3340.67   708.3 3362.27   762.3 3374.38     779 3376.52   874.1 3398.88
#Mann= 6 ,-1 , 0
       0      .1       0  279.22     .06       0   375.9    .045       0
   407.1     .06       0  407.71      .1       0   774.7      .1       0
Bank Sta=375.9,407.1
XS Rating Curve= 0 ,0
Exp/Cntr=0.3,0.1

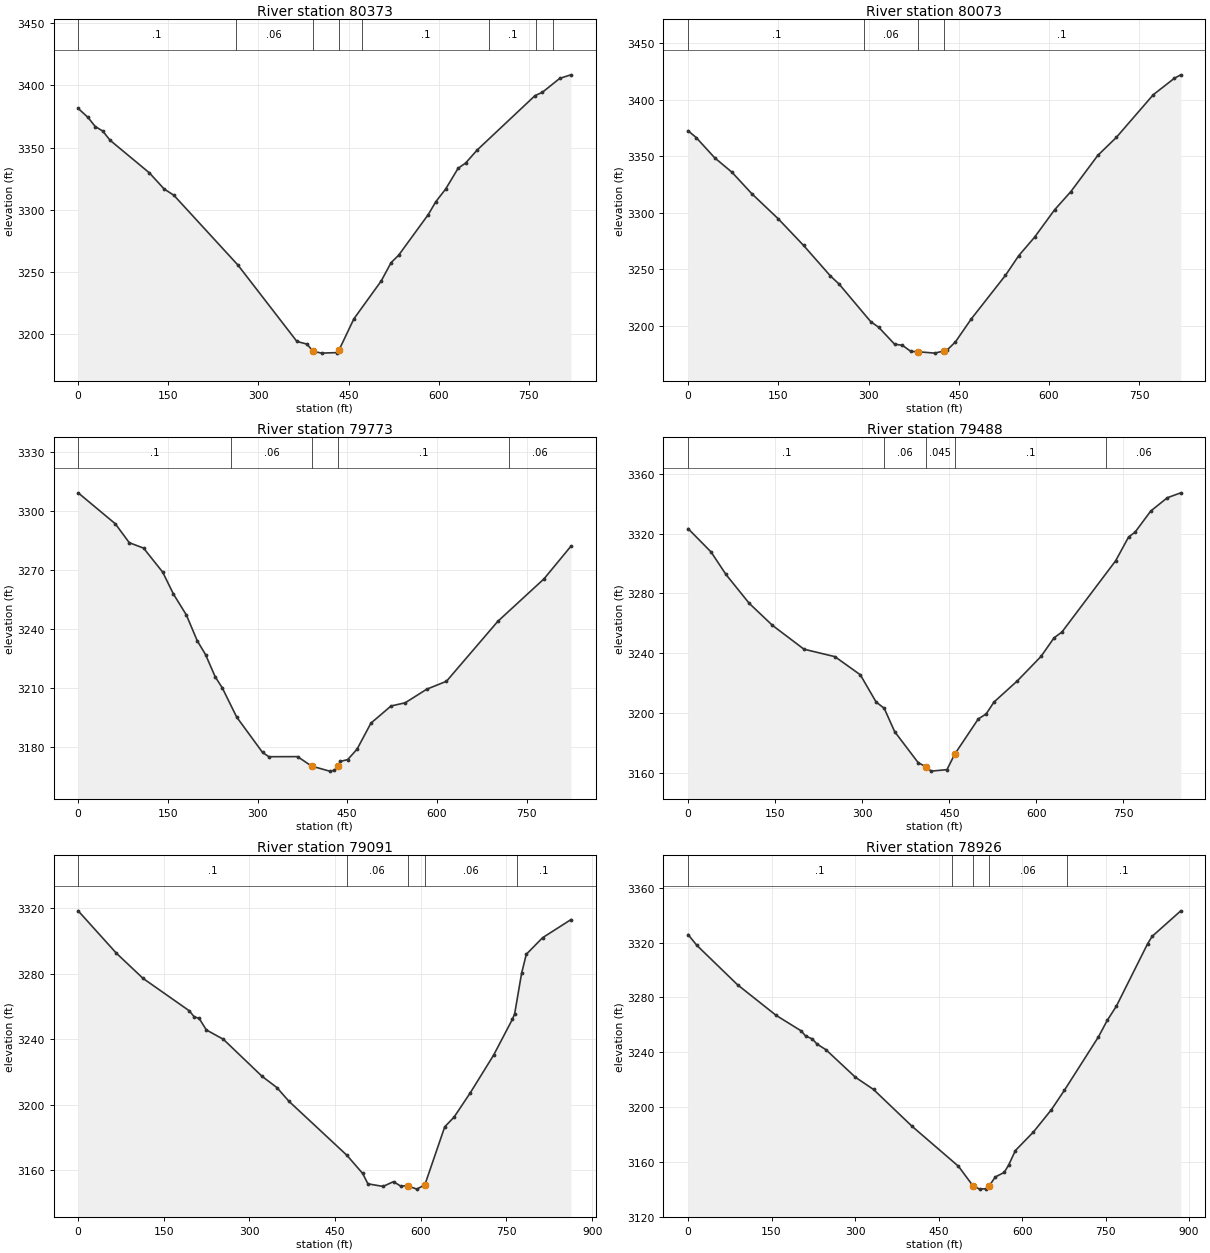
Type RM Length L Ch R = 1 ,80373   ,295.8,300,303.1
XS GIS Cut Line= 3
2392708.96655317646686.704787229     2392795.942      646290.384
      2392898.18      645888.958
#Sta/Elev= 30
       0 3381.42    16.2 3374.26    28.5 3366.81    40.8 3363.28      53 3355.87
   118.6 3329.59   143.1 3316.65   159.2 3311.65     266 3255.46     364 3194.15
   380.7 3191.99   390.9 3186.25   390.9 3186.24   405.2 3184.74     430 3185.16
     434 3187.11   458.9 3212.35   504.3 3242.71   520.8 3257.51   533.2 3263.35
   582.7 3296.14   595.1 3306.37   611.6 3316.65   632.3 3333.29   644.9 3337.56
   664.2 3348.07   760.2 3391.66   772.6  3394.4   801.5 3405.57     820 3408.42
#Mann= 8 ,-1 , 0
       0      .1       0  261.93     .06       0   390.9    .045       0
     434     .06       0  472.07      .1       0  684.18      .1       0
  761.47      .1       0  790.23      .1       0
Bank Sta=390.9,434
XS Rating Curve= 0 ,0
Exp/Cntr=0.3,0.1

Type RM Length L Ch R = 1 ,80073   ,292.4,300,306.5
XS GIS Cut Line= 3
     2392908.513      646755.164     2393078.441      646382.578
     2393246.418      646009.117
#Sta/Elev= 30
       0 3372.44    13.5  3366.4    44.3 3348.49    72.9 3335.81   105.8  3316.9
   149.8  3294.7   192.1 3271.09   236.7 3244.14   250.9 3237.12   303.6 3203.85
   316.8 3198.91   343.2    3184   356.4 3182.93   370.2 3177.59   382.3 3177.26
   410.2 3176.05   424.6 3177.92   431.1 3179.07   444.3 3185.88   470.6 3206.16
   527.6 3244.75   549.5 3262.01   575.9 3278.38   609.2 3302.56   636.4 3318.76
   681.1 3350.67   711.8 3366.49   773.2 3404.18   808.3 3418.74     819 3421.79
#Mann= 4 ,-1 , 0
       0      .1       0  293.23     .06       0   382.3    .045       0
   424.6      .1       0
Bank Sta=382.3,424.6
XS Rating Curve= 0 ,0
Exp/Cntr=0.3,0.1

Type RM Length L Ch R = 1 ,79773   ,287.9,285.6,274.1
XS GIS Cut Line= 3
     2393057.643      646845.472     2393333.208      646538.516
2393619.42598581646242.602482263
#Sta/Elev= 30
       0 3309.37    62.1 3293.61    85.5 3283.97   109.4 3281.22   141.4 3268.97
   159.4 3257.79   180.9 3247.22   199.2 3234.01   213.1 3226.96   229.2  3215.7
   241.2 3209.95   265.1 3195.19   308.5 3177.12     319 3174.97   366.9 3175.02
   390.5  3170.2   420.5 3167.63   428.7    3168   434.2  3170.2   438.8 3172.58
   450.9 3173.52   466.5 3178.81   489.7 3192.06   523.3  3200.8     547 3202.43
   583.1 3209.36   616.1  3213.4   701.9  3243.9   779.3 3265.58   824.2 3282.15
#Mann= 5 ,-1 , 0
       0      .1       0  256.07     .06       0   390.5    .045       0
   434.2      .1       0  720.89     .06       0
Bank Sta=390.5,434.2
XS Rating Curve= 0 ,0
Exp/Cntr=0.3,0.1

Type RM Length L Ch R = 1 ,79488   ,383.2,396.7,409.6
XS GIS Cut Line= 3
     2393241.782      647025.2642393476.62394324646851.673420838
     2393731.947      646356.937
#Sta/Elev= 30
       0 3323.26    39.6 3307.69    65.3 3292.67   105.3 3273.44   145.4 3258.71
   199.7 3242.81     253 3237.84   296.7 3225.75   323.9  3207.6   337.9 3203.39
   355.9 3187.82   396.4 3167.12     410 3164.34     410 3164.31   418.9 3161.47
     446 3162.46   459.5 3172.86     500 3196.32   513.5 3199.61     527 3207.55
   567.5 3221.78     608 3237.98   630.5 3250.41     644 3254.25   736.6 3301.82
   758.9 3317.67     770 3320.87   797.1 3335.01   825.6 3343.86   848.8 3347.14
#Mann= 5 ,-1 , 0
       0      .1       0  338.37     .06       0     410    .045       0
   459.5      .1       0  720.64     .06       0
Bank Sta=410,459.5
XS Rating Curve= 0 ,0
Exp/Cntr=0.3,0.1

Type RM Length L Ch R = 1 ,79091   ,160.7,165.3,170.2
XS GIS Cut Line= 3
     2393307.715      647105.6862393737.73682901 646949.75279667
2394135.43807301646871.012056355
#Sta/Elev= 30
       0 3318.54      67  3292.6   113.8 3277.19   194.7  3257.4   203.2 3253.72
   211.7 3252.85   224.5 3245.73   254.3    3240   322.3 3217.29   347.9 3210.53
   369.1 3202.11   470.7 3169.07   498.2 3157.99   507.4 3151.65   533.9 3150.08
   552.2 3152.99   564.5 3150.32   577.1 3150.45     593 3148.42   607.1 3151.08
   641.9 3186.52   658.3 3192.47   686.8 3207.39   727.6  3230.4   760.2 3252.13
   764.3 3255.54   776.5 3280.36   784.7 3291.97   813.2 3302.09   862.8 3313.15
#Mann= 5 ,-1 , 0
       0      .1       0  470.37     .06       0   577.1    .045       0
   607.1     .06       0   768.5      .1       0
Bank Sta=577.1,607.1
XS Rating Curve= 0 ,0
Exp/Cntr=0.3,0.1

Type RM Length L Ch R = 1 ,78926   ,360.1,352.4,340.8
XS GIS Cut Line= 3
     2393303.397      647141.3222393718.16099167647061.869414505
2394177.82391867647115.831349343
#Sta/Elev= 30
       0 3325.94    15.6 3318.11    88.9 3289.27   158.2 3266.96     203 3255.69
   211.1 3251.92   223.3 3249.75   231.5 3246.09   247.8 3241.86   300.7  3221.8
   333.1 3212.91   402.5 3185.99   485.7 3156.89   511.5 3142.78   523.6  3140.2
   535.7 3140.54   540.4 3142.15   551.8 3149.06   567.9 3152.38   575.9 3157.78
     588 3168.36   620.2  3181.8   652.5 3198.06   676.1 3212.35     737 3251.14
   753.1 3263.37   769.3 3273.59   825.6 3319.27   833.7 3324.62   885.1 3343.22
#Mann= 5 ,-1 , 0
       0      .1       0  474.51     .06       0   511.5    .045       0
   540.4     .06       0  681.05      .1       0
Bank Sta=511.5,540.4
XS Rating Curve= 0 ,0
Exp/Cntr=0.3,0.1

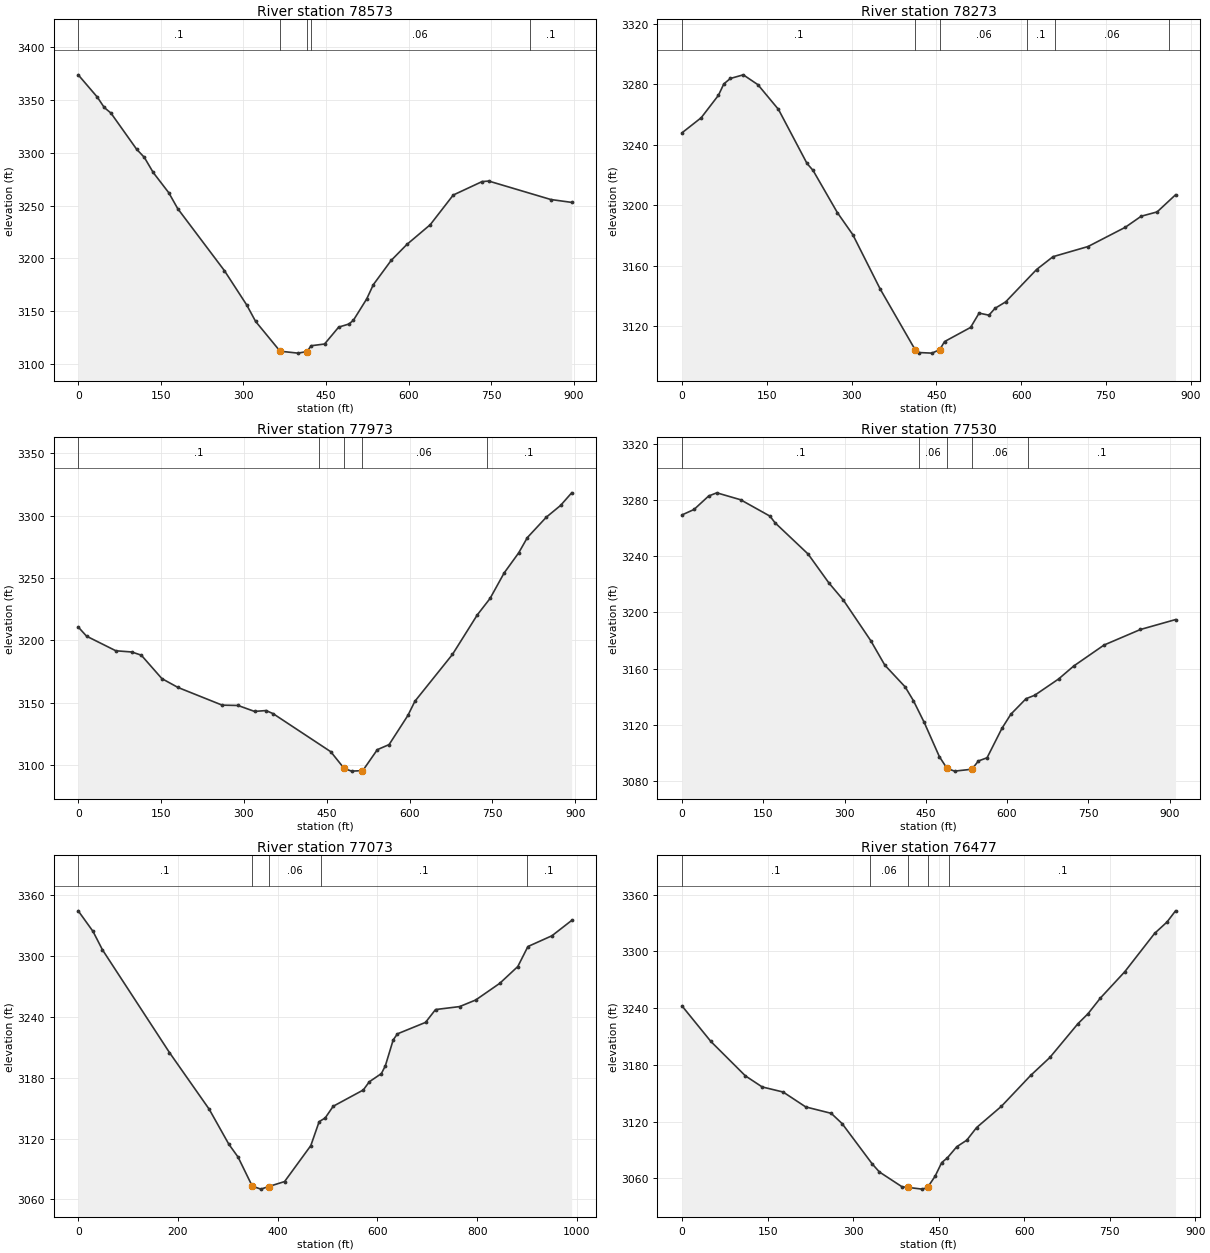
Type RM Length L Ch R = 1 ,78573   ,309.9,300,288.6
XS GIS Cut Line= 3
2393299.97589361647428.466170201     2393689.383      647371.005
     2394188.285       647310.35
#Sta/Elev= 30
       0 3373.87    34.6 3352.81    47.3 3342.93    59.4 3337.67     106 3303.46
   120.1 3295.68   136.2 3281.39   164.5 3262.17   180.7 3247.16   265.6 3188.36
     306 3155.92   322.2 3140.32   366.6 3112.13     399  3110.3   415.1 3111.73
   423.2 3117.31   447.4 3118.93     473 3134.92   491.7 3137.88   499.8 3141.45
   523.9  3161.6     536 3175.15   568.3 3198.07   596.9 3213.22   639.3 3231.91
   681.1 3260.02   733.5 3272.77   745.6 3273.26   858.4 3255.77   896.2 3253.06
#Mann= 5 ,-1 , 0
       0      .1       0   366.6    .045       0   415.1      .1       0
  422.42     .06       0  820.01      .1       0
Bank Sta=366.6,415.1
XS Rating Curve= 0 ,0
Exp/Cntr=0.3,0.1

Type RM Length L Ch R = 1 ,78273   ,291.4,300,295.3
XS GIS Cut Line= 3
2393494.23057446647865.441936165      2393840.93      647620.074
     2394222.471      647383.942
#Sta/Elev= 30
       0 3247.83    33.8 3257.75    64.3 3272.58    73.9 3280.13    85.4 3283.71
   108.3 3286.13   134.2 3279.62   170.6 3263.27   221.1 3227.54   231.8 3222.95
   274.8 3195.06   302.2 3180.44   350.6 3144.54   412.3 3104.52   419.9 3102.52
   442.2 3102.14     456 3104.41   464.5 3109.77   510.6 3119.12   525.7 3128.59
   543.1 3127.23   553.9 3131.77   572.7 3136.02   627.4 3157.41   656.5  3165.9
   718.5 3172.61   784.4 3185.33   812.6 3192.65   840.8  3195.5   873.4 3206.82
#Mann= 6 ,-1 , 0
       0      .1       0   412.3    .045       0     456     .06       0
  610.62      .1       0  659.69     .06       0  861.08      .1       0
Bank Sta=412.3,456
XS Rating Curve= 0 ,0
Exp/Cntr=0.3,0.1

Type RM Length L Ch R = 1 ,77973   ,436.7,443.7,447.1
XS GIS Cut Line= 3
2393577.59440426647963.326659578     2394055.992      647816.587
      2394425.78      647683.129
#Sta/Elev= 30
       0 3210.78    15.1 3203.43    68.1 3191.73      97 3190.76   114.2 3188.21
   151.5 3169.44   180.6 3162.37   260.6 3148.21   289.4 3147.93   319.2 3143.18
   340.1 3143.86   352.7 3141.44   457.3 3110.91   481.5 3097.54   494.9 3095.37
   513.2 3095.73   516.1 3096.33   541.6 3112.56   562.9 3116.62   596.9 3139.92
   609.6  3151.3   677.7 3188.85   722.6 3220.46   745.7 3233.62   771.2 3254.03
   797.6 3270.15   813.2 3282.34   847.6  3298.7   873.3 3308.06   893.5 3318.19
#Mann= 5 ,-1 , 0
       0      .1       0  436.65     .06       0   481.5    .045       0
   513.2     .06       0   739.3      .1       0
Bank Sta=481.5,513.2
XS Rating Curve= 0 ,0
Exp/Cntr=0.3,0.1

Type RM Length L Ch R = 1 ,77530   ,433.8,456.3,466.6
XS GIS Cut Line= 3
     2393567.339      648071.6262393897.95248932648247.130893614
      2394434.71      648254.972
#Sta/Elev= 30
       0 3269.35      22 3273.19    49.1  3282.8    64.1 3285.05     108 3280.13
   162.4 3268.42   171.4 3263.82   232.7 3241.47     271 3220.94   297.8 3208.69
   348.2 3179.92   374.3 3162.42   411.9  3146.9   427.1 3137.13   447.1  3121.6
   475.1 3097.23   489.2  3088.9   503.1 3086.97   535.1 3088.32   547.1  3094.2
   563.1 3096.48   590.5 3117.39   607.1 3127.51   635.1 3138.54   650.9 3140.93
   695.1 3152.54   723.1 3161.78   779.1 3176.72   846.3 3187.78   911.1 3194.84
#Mann= 5 ,-1 , 0
       0      .1       0  437.72     .06       0   489.2    .045       0
   535.1     .06       0  639.45      .1       0
Bank Sta=489.2,535.1
XS Rating Curve= 0 ,0
Exp/Cntr=0.3,0.1

Type RM Length L Ch R = 1 ,77073   ,627.1,596.9,577.7
XS GIS Cut Line= 3
     2393393.441      648311.0222393794.38428726648557.532638313
     2394310.013      648614.805
#Sta/Elev= 30
       0 3344.47    29.7 3324.17    48.5 3306.15     183 3204.79   262.6 3148.99
     302 3114.49   320.5 3101.83     349 3073.13   366.3 3070.21   382.13072.785
   413.8 3077.66   466.4  3113.1   483.1  3136.7   495.2 3140.32   511.3 3151.88
   571.6  3167.9   583.7 3176.01   607.9 3184.06   615.9  3191.8   631.6 3217.25
   640.1 3223.24   696.4 3234.51   716.5 3247.18   764.8  3250.1     797 3256.58
   845.3 3273.03   881.5 3289.59   901.7 3309.27     950 3319.92   989.5 3335.01
#Mann= 5 ,-1 , 0
       0      .1       0     349    .045       0   382.1     .06       0
  486.98      .1       0  899.34      .1       0
Bank Sta=349,382.1
XS Rating Curve= 0 ,0
Exp/Cntr=0.3,0.1

Type RM Length L Ch R = 1 ,76477   ,295.3,303.1,311.3
XS GIS Cut Line= 3
     2393720.864      649281.4922394014.30057236648883.415240404
     2394356.596      648740.201
#Sta/Elev= 30
       0 3242.25    50.4 3204.81     111 3168.38   140.5 3156.63   177.2 3151.26
   216.9 3135.49   261.6 3128.71   280.7 3117.86   333.5 3075.21   346.1 3066.67
   385.9 3050.96   395.8 3050.38   421.1 3048.51   430.6 3050.34   443.7 3062.04
   455.4 3076.57   465.4 3081.64   481.8 3093.34   499.4 3100.31   516.6 3113.66
   560.1 3136.13   611.4 3168.79   645.1 3187.79   694.5 3223.65   711.8 3233.93
   733.7 3250.64   776.5 3278.51   828.9 3319.11   850.6 3331.14   865.6 3342.98
#Mann= 5 ,-1 , 0
       0      .1       0  330.32     .06       0   395.8    .045       0
   430.6     .06       0  468.81      .1       0
Bank Sta=395.8,430.6
XS Rating Curve= 0 ,0
Exp/Cntr=0.3,0.1

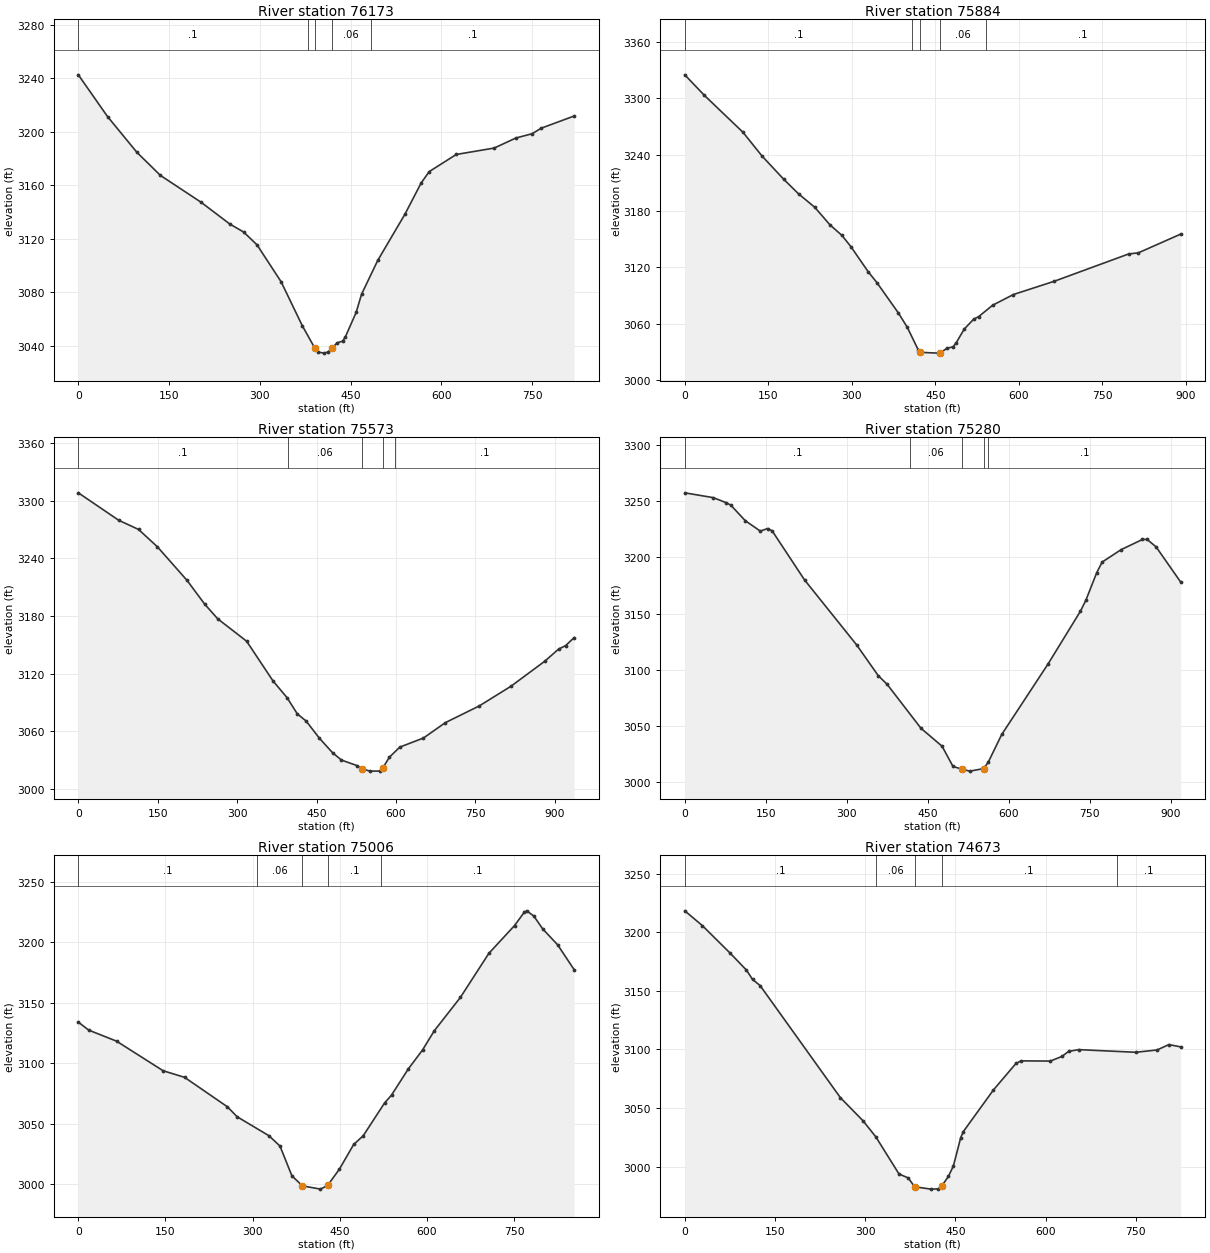
Type RM Length L Ch R = 1 ,76173   ,301.1,289.9,286.4
XS GIS Cut Line= 3
      2393770.92      649355.287     2394142.441      649183.148
     2394509.011      649000.145
#Sta/Elev= 30
       0 3242.63    48.3 3211.39    96.8 3184.65   135.7 3167.39   202.6 3147.41
   250.2  3131.1   273.1 3125.09   295.2 3115.51   334.9    3088   370.1 3054.97
     391 3038.05   396.6 3035.35   405.4 3034.53   412.9 3035.36   418.5 3038.07
   427.7 3042.24   436.6 3043.49   441.1  3046.6     459 3064.96   467.9 3078.53
   494.7 3103.87   539.5 3138.32   566.3 3161.69   579.7 3170.26   624.4 3183.08
     687 3187.86     723  3195.4   749.8 3198.59   764.7 3202.71   819.2 3211.84
#Mann= 5 ,-1 , 0
       0      .1       0  379.26     .06       0     391    .045       0
   418.5     .06       0  483.04      .1       0
Bank Sta=391,418.5
XS Rating Curve= 0 ,0
Exp/Cntr=0.3,0.1

Type RM Length L Ch R = 1 ,75884   ,300.6,310.1,320.7
XS GIS Cut Line= 3
 2393914.4382702649664.1737127612394184.74061699649550.627787269
     2394567.863      649092.688
#Sta/Elev= 30
       0 3324.83      35 3303.09   104.5 3263.75   138.7 3238.49   177.7 3213.76
   204.2 3198.32   233.4 3183.98   260.6 3165.38   282.2 3154.08   298.1  3142.3
   329.3 3115.48     345 3103.87   383.6 3071.58   399.5  3056.4   419.4 3032.09
   423.2 3029.78   454.5 3028.95   459.1 3029.17   470.2 3033.99   481.8 3035.71
   487.5 3040.12   501.7 3054.49   518.7 3065.06   527.5 3067.69   552.8 3079.89
   590.1 3091.27   663.1 3105.29     797 3134.39   814.4 3135.58   890.3 3155.46
#Mann= 5 ,-1 , 0
       0      .1       0  408.63     .06       0   423.2    .045       0
   459.1     .06       0  539.97      .1       0
Bank Sta=423.2,459.1
XS Rating Curve= 0 ,0
Exp/Cntr=0.3,0.1

Type RM Length L Ch R = 1 ,75573   ,280.9,293.1,322
XS GIS Cut Line= 3
     2394005.453      649732.431     2394535.772      649579.008
     2394870.997      649391.012
#Sta/Elev= 30
       0 3308.33    76.3 3279.73   113.8 3270.16   149.5 3251.99   205.4 3217.03
   238.7 3192.29   263.3 3177.01   317.8 3153.73   367.8 3112.23   394.2 3094.87
   413.6 3077.96   430.2 3070.53   455.2 3052.69   480.2 3037.46   496.9 3029.87
     526 3024.16   535.2 3020.84     551 3018.33   569.2 3018.42   574.9 3021.49
   587.6 3032.94   607.2 3043.38   651.8 3052.83   693.1 3068.83   757.3 3086.31
   816.9 3106.71   880.5 3132.69   906.9 3145.43   920.3 3149.15   936.4 3157.49
#Mann= 5 ,-1 , 0
       0      .1       0  395.58     .06       0   535.2    .045       0
   574.9     .06       0  598.15      .1       0
Bank Sta=535.2,574.9
XS Rating Curve= 0 ,0
Exp/Cntr=0.3,0.1

Type RM Length L Ch R = 1 ,75280   ,281.1,274.6,261.2
XS GIS Cut Line= 3
     2394001.997      649806.9992394388.91921878649769.260897268
     2394810.308      650090.417
#Sta/Elev= 30
       0 3257.64      53 3253.33    77.1 3248.75    85.2 3246.68     112 3232.83
   139.9 3223.53   153.5 3225.83   161.9 3223.73   221.8 3180.05   318.3 3122.13
   358.4  3094.7   374.8 3087.01   437.6 3047.77   476.6 3031.83   496.8 3013.85
   513.9 3011.21   528.2  3009.6   553.9 3011.89   562.5 3017.86   587.2 3042.29
   672.7 3104.88     733 3152.14   743.1 3161.96   763.2 3186.52   773.3 3195.95
   808.5 3207.05   847.9 3216.07   856.4 3216.15   873.2 3209.46   918.6 3178.19
#Mann= 5 ,-1 , 0
       0      .1       0  417.92     .06       0   513.9    .045       0
   553.9     .06       0  562.26      .1       0
Bank Sta=513.9,553.9
XS Rating Curve= 0 ,0
Exp/Cntr=0.3,0.1

Type RM Length L Ch R = 1 ,75006   ,341.2,332.3,319.6
XS GIS Cut Line= 3
2393952.63506596649974.1877361692394347.38859362650065.720417012
2394786.69719787 650154.60907659
#Sta/Elev= 30
       0 3134.04    17.9 3127.42    65.7 3118.34   145.9 3093.88   182.8 3088.45
   256.7 3064.07   273.2 3055.91     328 3040.24   347.1 3031.65   367.6 3007.08
   385.7 2998.81   416.8  2996.1   429.1 2999.15   449.5 3012.72   473.9 3032.98
   490.3 3040.14     527 3067.18   539.2 3073.86   567.8 3095.28   592.4 3111.01
   612.7 3126.92   657.6 3154.46   706.6 3190.83   750.8 3213.81   767.8 3224.95
   771.9 3225.96   784.1 3221.57   799.4 3210.96   824.9 3197.93   853.4 3177.35
#Mann= 5 ,-1 , 0
       0      .1       0  307.84     .06       0   385.7    .045       0
   429.1      .1       0  521.19      .1       0
Bank Sta=385.7,429.1
XS Rating Curve= 0 ,0
Exp/Cntr=0.3,0.1

Type RM Length L Ch R = 1 ,74673   ,300.5,300,297.1
XS GIS Cut Line= 3
     2394006.821      650498.539     2394405.637      650378.905
     2394797.873      650265.782
#Sta/Elev= 30
       0 3218.24    29.2 3205.63    75.1  3182.3   102.5 3167.67   112.7 3159.65
   125.2 3154.48   258.8 3058.78   296.4 3039.06   317.7 3025.34   356.2 2993.68
   371.6 2990.27   382.2 2982.75   409.2 2980.73   421.7 2980.93     427 2983.14
   438.3 2991.52   446.7 3000.47   458.9 3024.72   463.3 3029.88   513.3 3065.38
   550.7 3087.95   559.1 3090.19   607.9 3090.02   627.3 3093.99   638.2 3098.24
   654.8 3099.79   750.1 3097.52   785.6  3099.5     805 3104.09   824.6 3102.14
#Mann= 5 ,-1 , 0
       0      .1       0  318.04     .06       0   382.2    .045       0
     427      .1       0  718.32      .1       0
Bank Sta=382.2,427
XS Rating Curve= 0 ,0
Exp/Cntr=0.3,0.1