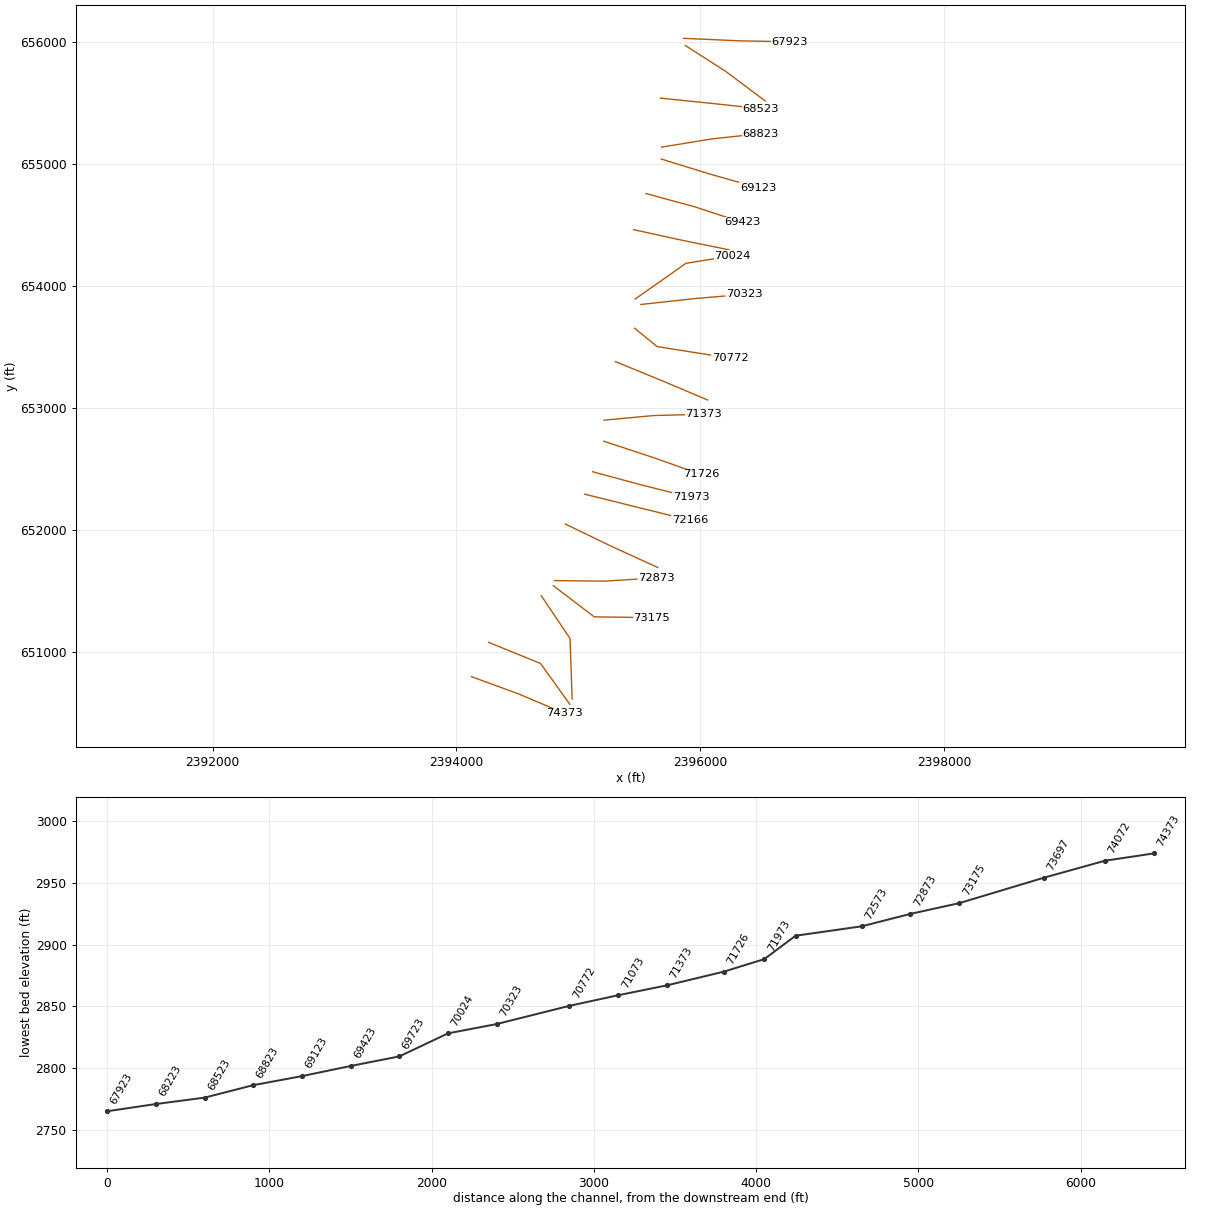
HEC-RAS study SENECACK.prj: SENECACK

--- SENECACK.g03 (geometry) --- (continued)

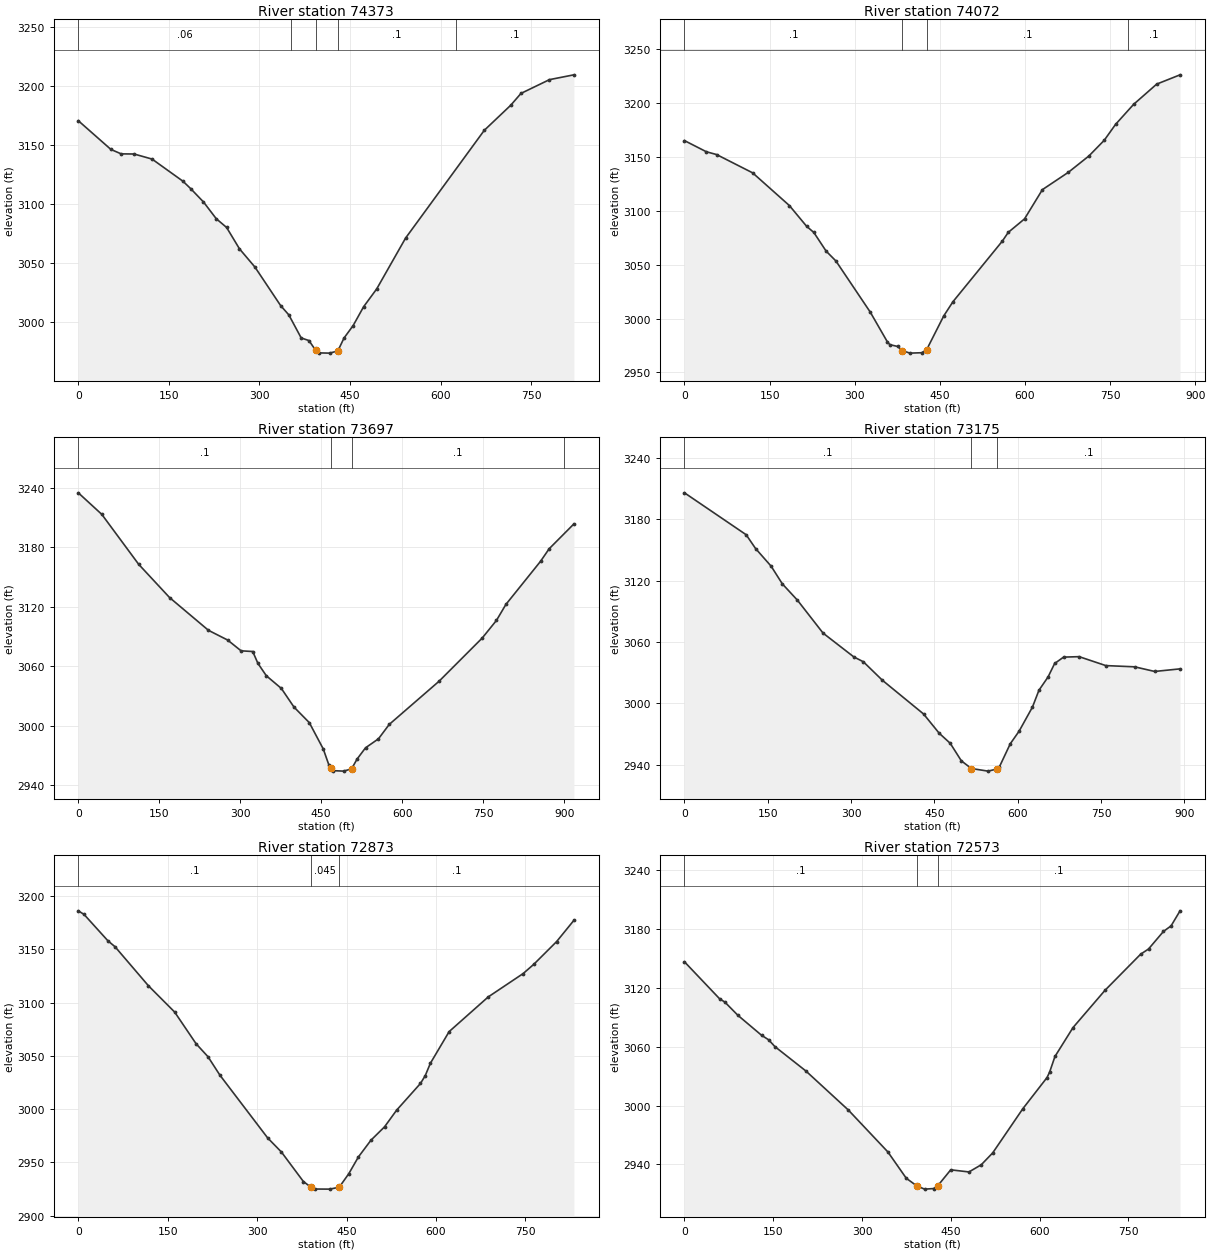
Type RM Length L Ch R = 1 ,74373   ,301.7,301.5,301.9
XS GIS Cut Line= 3
       2394124.1      650795.376      2394509.62      650654.403
     2394887.388      650494.564
#Sta/Elev= 30
       0 3170.64    53.9 3146.35      71 3142.56    92.3 3142.46   122.1 3138.17
   173.2 3119.44     186 3113.18   207.3 3101.83   228.5 3087.62   245.6 3080.24
   266.9 3062.15   292.5 3046.71     335 3014.14   348.6 3006.23   369.1  2986.7
   381.9 2984.48   393.1 2976.23   398.9 2974.04   416.1 2973.84   429.8 2975.69
     440 2986.61   455.1 2997.14   472.5 3013.14   494.2 3028.24     542 3071.27
   672.3  3162.5   716.2 3183.78   733.1 3193.77   780.3 3205.43   820.7  3209.5
#Mann= 5 ,-1 , 0
       0     .06       0  352.72      .1       0   393.1    .045       0
   429.8      .1       0  625.22      .1       0
Bank Sta=393.1,429.8
XS Rating Curve= 0 ,0
Exp/Cntr=0.3,0.1

Type RM Length L Ch R = 1 ,74072   ,392.8,374.9,344.7
XS GIS Cut Line= 3
     2394263.516      651077.448 2394690.0369681650903.919878717
      2394930.77      650568.374
#Sta/Elev= 30
       0 3165.22    38.6 3154.85    56.6 3152.27   120.1 3135.29   184.9  3104.9
   215.1 3085.75     228  3079.9   249.6 3062.63   266.9 3053.44   327.4 3005.98
   357.6 2978.32   361.9 2975.76   375.9 2974.05   383.5 2970.29   397.3 2967.89
   418.1 2968.26   426.7 2970.99   456.9 3002.43   473.2 3015.66   560.2 3071.91
   570.6    3080   599.3 3092.54   630.8 3119.69   676.7 3135.84   712.8 3150.98
   739.8 3165.53   759.8 3180.33   791.6 3198.91   832.2 3217.67   873.4  3226.3
#Mann= 4 ,-1 , 0
       0      .1       0   383.5    .045       0   426.7      .1       0
  781.54      .1       0
Bank Sta=383.5,426.7
XS Rating Curve= 0 ,0
Exp/Cntr=0.3,0.1

Type RM Length L Ch R = 1 ,73697   ,484.7,522,548.8
XS GIS Cut Line= 3
     2394696.318      651458.9552394931.73782555651109.106836187
2394949.40269148650613.080131916
#Sta/Elev= 30
       0 3234.83    43.5 3213.11   111.8 3162.76   169.1 3129.19   241.1 3096.18
   276.6 3086.39   301.5 3075.51   323.1 3074.82   332.7 3062.85   348.3 3050.36
   376.1 3037.59   399.5  3018.8   427.9 3003.09   453.8 2976.48   463.9  2960.8
   467.9 2957.03   471.9 2954.68   491.4  2954.2   506.2 2956.47   516.3  2966.3
     532 2977.69     556 2986.78     576 3001.32   668.1 3044.76   748.1 3088.34
   774.6  3106.2   792.1 3122.31   856.2 3165.74   872.2 3178.42     918 3203.47
#Mann= 4 ,-1 , 0
       0      .1       0   467.9    .045       0   506.2      .1       0
  899.17      .1       0
Bank Sta=467.9,506.2
XS Rating Curve= 0 ,0
Exp/Cntr=0.3,0.1

Type RM Length L Ch R = 1 ,73175   ,300.3,301.6,302
XS GIS Cut Line= 3
     2394794.545      651542.0072395130.76579996      651286.054
2395600.49708722651279.893691476
#Sta/Elev= 30
       0 3205.78     111 3164.81     128  3151.3   156.1 3133.95   176.2 3116.72
   203.3 3100.81   249.5 3068.58   304.9 3045.29     322 3040.58   356.3 3022.47
   430.5 2989.47   458.5 2970.72   478.5  2960.8   498.5 2943.66   516.6 2936.15
   546.5 2933.59   562.6 2935.64   566.6 2937.29   586.6 2960.35   602.6 2972.76
   626.6  2996.3   638.2 3012.68   654.6 3025.65   666.5 3038.86   682.6  3045.1
   710.6 3045.54   758.6 3036.81   810.6  3035.6   846.6 3031.07   892.3 3033.61
#Mann= 3 ,-1 , 0
       0      .1       0   516.6    .045       0   562.6      .1       0
Bank Sta=516.6,562.6
XS Rating Curve= 0 ,0
Exp/Cntr=0.3,0.1

Type RM Length L Ch R = 1 ,72873   ,306.4,300,287.4
XS GIS Cut Line= 3
2394805.13413192651583.586087223     2395215.149      651578.938
     2395635.666      651605.395
#Sta/Elev= 30
       0 3186.12     9.6 3182.76    49.6 3158.02    61.6  3152.4   117.6 3115.79
   161.6 3091.11   197.6 3061.34   217.6 3049.14   237.6 3031.81   317.6 2972.98
   340.8 2959.67   377.6 2932.02   389.6 2926.97   397.6 2924.96   421.7 2924.87
   437.7 2926.65   453.7  2939.3   469.9 2955.07   490.9 2970.76   513.8 2983.38
     534 2998.98     574 3024.05     582 3031.34   590.6 3042.96   622.1 3072.73
   687.7  3105.3   746.3 3127.23   764.1 3135.89   802.4 3157.23   831.4 3177.17
#Mann= 3 ,-1 , 0
       0      .1       0   389.6    .045       0   437.7      .1       0
Bank Sta=389.6,437.7
XS Rating Curve= 0 ,0
Exp/Cntr=0.3,0.1

Type RM Length L Ch R = 1 ,72573   ,402.2,407.8,411.3
XS GIS Cut Line= 3
     2394893.396      652047.462     2395258.437      651870.782
     2395651.231      651691.242
#Sta/Elev= 30
       0 3146.72    59.3 3109.02    68.2 3105.65    90.4 3092.06   130.2  3071.8
   142.2 3067.17   152.6 3060.32   205.1 3035.37   276.8 2995.56   343.7 2952.76
   374.8 2925.89   392.6  2918.1   405.7 2914.83   420.8 2915.39   427.9 2918.21
   449.9 2934.53   480.7 2932.36   501.5  2939.7   520.8 2951.79   571.7 2996.84
   612.6 3028.64     617 3034.22     626 3050.15   656.6  3079.7   710.6 3117.67
   770.9 3154.56   784.1 3159.78   809.4 3177.75   822.2 3183.36   837.4 3198.74
#Mann= 3 ,-1 , 0
       0      .1       0   392.6    .045       0   427.9      .1       0
Bank Sta=392.6,427.9
XS Rating Curve= 0 ,0
Exp/Cntr=0.3,0.1

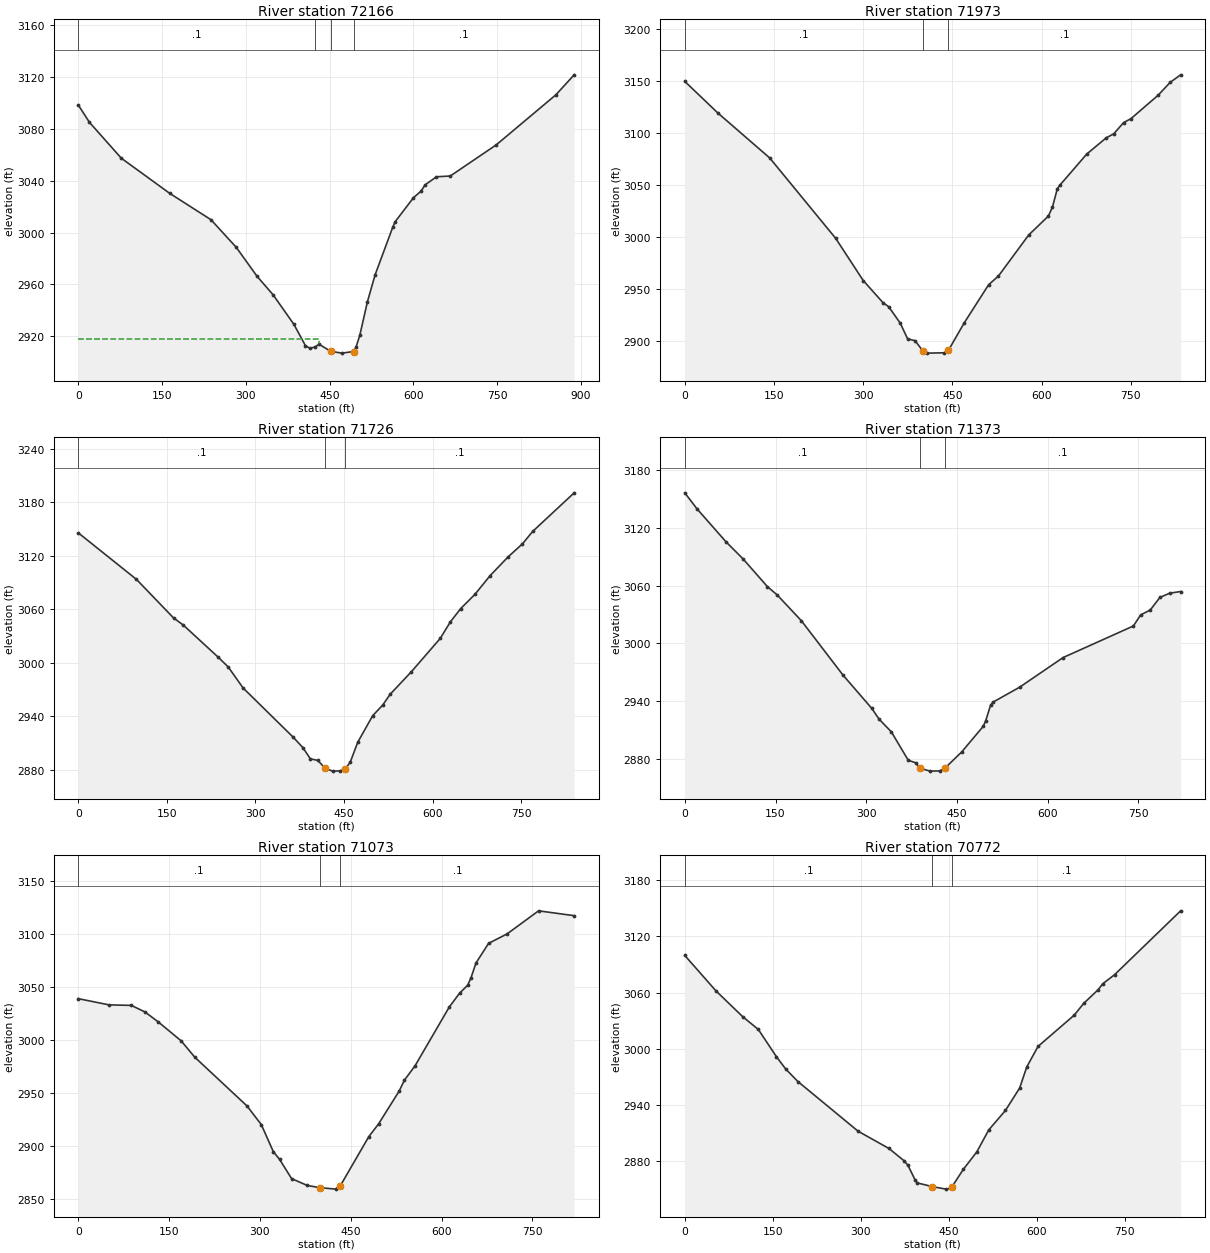
Type RM Length L Ch R = 1 ,72166   ,190.3,192.2,189
XS GIS Cut Line= 2
2395052.00965541652292.1383243312395914.12714302652078.581026084
#Sta/Elev= 30
       0 3098.05    19.8 3084.84      77 3057.18   163.5 3030.19   237.6 3009.85
     283 2988.54   320.1 2966.33     349 2952.02   386.1 2929.38   406.7 2913.02
   414.9 2910.88   423.8 2911.95   431.4 2913.97   452.42908.522   472.3 2907.19
   493.32908.435   497.3 2911.59   504.3 2921.02   517.9 2946.79   531.7 2967.52
   563.3 3004.17   567.4 3008.24   600.3 3026.74   614.3    3032     621 3036.63
   641.6 3042.88   666.3 3043.47   748.7 3067.46   855.4 3105.93   888.2 3121.33
#Mann= 4 ,-1 , 0
       0      .1       0   423.8    .045       0   452.4    .045       0
   493.3      .1       0
#XS Ineff= 2 , 0
           431.4    2918
Permanent Ineff=
       F       F
Bank Sta=452.4,493.3
XS Rating Curve= 0 ,0
Exp/Cntr=0.3,0.1

Type RM Length L Ch R = 1 ,71973   ,247,247.9,242.4
XS GIS Cut Line= 3
2395116.97732979652476.284176608     2395512.291      652369.529
      2395923.83      652265.802
#Sta/Elev= 30
       0  3149.3    55.7 3118.91   142.9 3075.73   253.8 2998.52   300.1 2958.01
   333.3 2936.78   342.9 2932.83   362.3 2917.16   374.7 2902.01   387.2 2900.26
   400.6 2890.27   407.9 2888.28   436.7  2888.6   443.3 2890.85   469.7 2917.12
     511    2954   527.5 2962.34   578.4 3001.79   611.4 3019.87   618.3 3028.49
   626.5 3046.15   630.6 3049.47     676  3079.5     709  3095.2   721.4 3098.89
   737.9 3109.69   750.3 3113.49   795.9 3135.93   816.3 3148.35   833.9 3155.62
#Mann= 3 ,-1 , 0
       0      .1       0   400.6    .045       0   443.3      .1       0
Bank Sta=400.6,443.3
XS Rating Curve= 0 ,0
Exp/Cntr=0.3,0.1

Type RM Length L Ch R = 1 ,71726   ,345,352.1,358
XS GIS Cut Line= 3
2395209.65702223652726.2143335572395622.56256499652590.041747794
2396004.29182435652454.720563328
#Sta/Elev= 30
       0 3145.82    98.5 3093.56   161.2 3050.33   177.7 3042.31     237 3006.11
   253.9 2995.19   279.1 2971.57   363.4 2916.66   380.4 2904.59   392.9 2892.03
   405.5 2890.25   418.4 2881.22   430.8  2878.2   443.5 2878.43   451.9 2880.69
   460.4 2887.97   473.2 2910.58   498.6 2940.52   515.6 2952.44   528.3 2964.66
   563.9  2989.7   612.9 3027.21   630.2 3045.89   647.7 3060.85   671.7 3076.74
   697.4 3097.75   727.8 3118.79   752.1 3133.41   769.5 3147.42   839.8 3190.81
#Mann= 3 ,-1 , 0
       0      .1       0   418.4    .045       0   451.9      .1       0
Bank Sta=418.4,451.9
XS Rating Curve= 0 ,0
Exp/Cntr=0.3,0.1

Type RM Length L Ch R = 1 ,71373   ,308.2,300,290.3
XS GIS Cut Line= 3
     2395210.811      652899.145     2395618.342      652937.138
      2396028.85      652947.582
#Sta/Elev= 30
       0 3156.69      20 3140.16    68.2 3105.66    96.4 3087.89   136.5 3059.14
   152.6 3050.51   192.8 3023.56   261.6 2966.96   309.3 2932.26   321.3 2921.08
   341.5 2907.98   369.5 2878.35   381.6 2875.76   389.2 2869.94   405.7 2867.03
   421.7 2867.25   429.7 2869.87   457.7 2886.87   493.7  2913.8   497.7 2919.72
   505.7 2935.75   509.7 2938.86   553.7 2954.39   625.5 2985.22   741.8  3018.1
   753.8 3029.63   769.8  3034.8   785.6  3047.8   801.8 3052.25   819.9 3053.96
#Mann= 3 ,-1 , 0
       0      .1       0   389.2    .045       0   429.7      .1       0
Bank Sta=389.2,429.7
XS Rating Curve= 0 ,0
Exp/Cntr=0.3,0.1

Type RM Length L Ch R = 1 ,71073   ,295.9,301.7,303.3
XS GIS Cut Line= 3
     2395304.767      653379.201     2395683.713      653224.005
     2396060.908      653064.505
#Sta/Elev= 30
       0 3039.04    50.8 3033.18    87.6 3032.69   110.2 3026.45   131.8 3017.18
   169.7 2999.27   192.3 2983.77   278.8 2937.55   302.3 2919.97     322 2894.58
   332.5  2887.1   352.3 2868.98   378.2 2862.51   398.4 2860.52   424.9 2859.06
   432.9 2862.37   479.8 2908.67   495.9 2920.66     530 2951.76   538.7 2962.11
   556.1 2975.53   612.6 3031.05   629.9 3044.35     643 3051.66   648.6 3058.79
   656.8 3072.72   677.7 3091.35   708.1 3100.19   760.2 3122.06     819 3117.47
#Mann= 3 ,-1 , 0
       0      .1       0   398.4    .045       0   432.9      .1       0
Bank Sta=398.4,432.9
XS Rating Curve= 0 ,0
Exp/Cntr=0.3,0.1

Type RM Length L Ch R = 1 ,70772   ,438.4,448.3,450
XS GIS Cut Line= 3
     2395461.573      653653.175  2395646.408871653502.503521499
     2396245.798      653407.919
#Sta/Elev= 30
       0 3099.76    53.1 3061.99    98.6 3034.52   125.4 3020.77   156.3 2991.66
   171.8 2978.77   192.9  2965.2   295.5 2912.22   348.1 2893.79     374 2880.62
   380.5  2875.8   392.7 2860.16   396.7 2857.02     422 2853.12   445.3 2850.44
   453.4 2851.43   455.7 2853.17   474.9  2871.6     498 2890.34   518.2 2913.63
   546.6 2934.34   570.9 2958.33     583 2980.79   602.2 3002.71     664 3036.12
   680.2 3048.72   704.5 3063.06   712.6 3069.57   732.8 3079.29   845.3 3147.38
#Mann= 3 ,-1 , 0
       0      .1       0     422    .045       0   455.7      .1       0
Bank Sta=422,455.7
XS Rating Curve= 0 ,0
Exp/Cntr=0.3,0.1

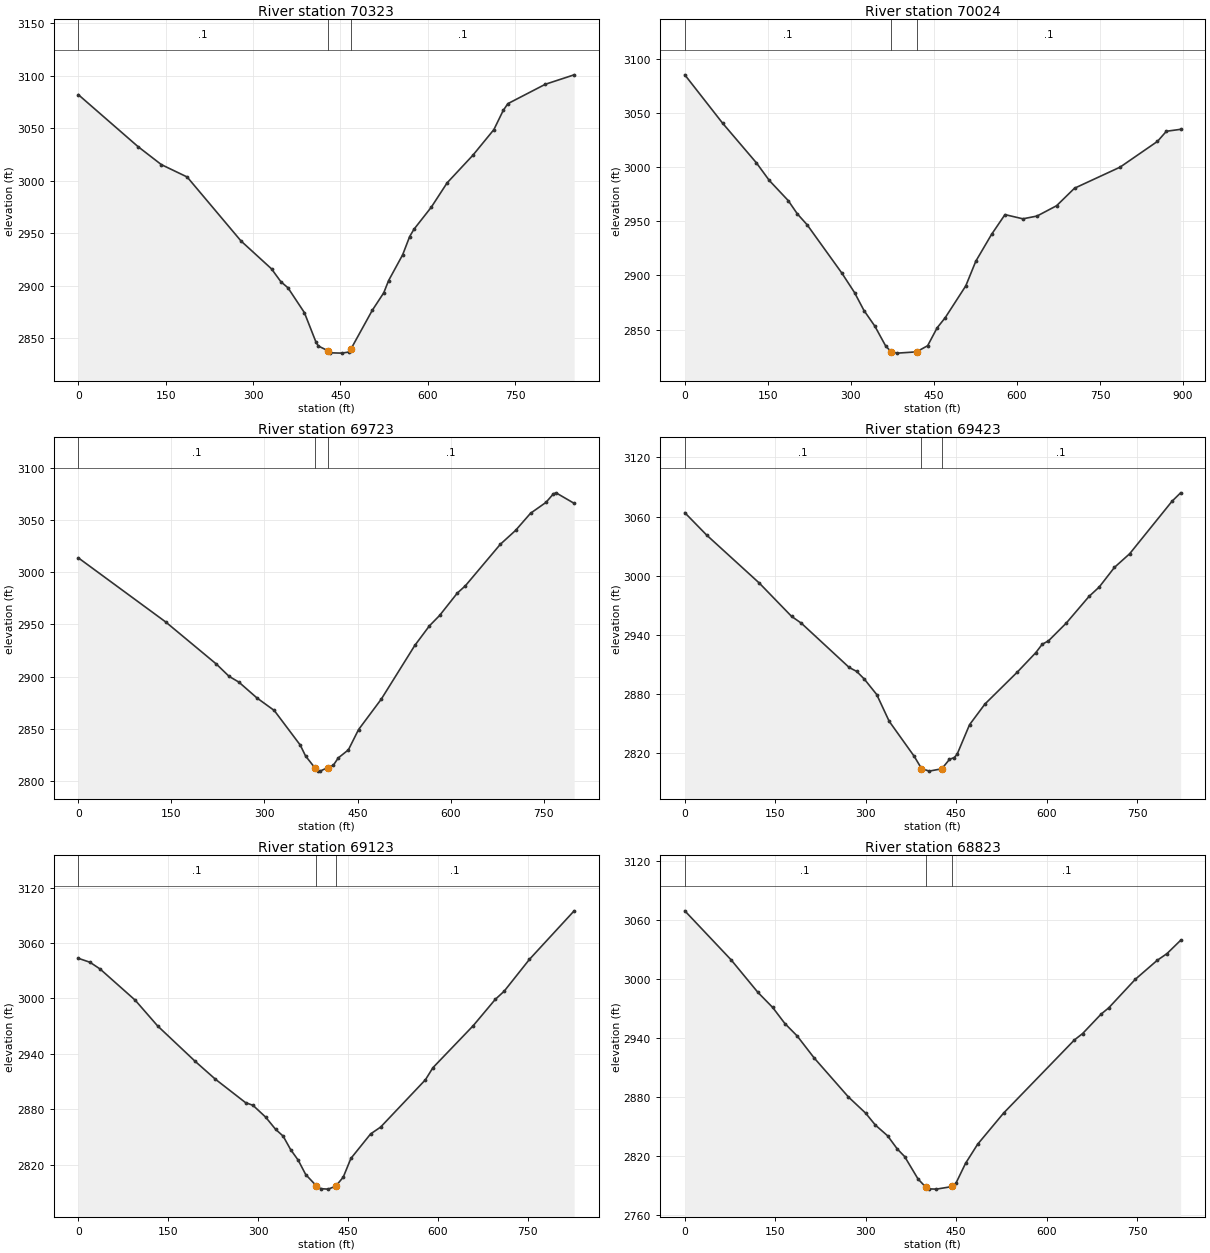
Type RM Length L Ch R = 1 ,70323   ,285.8,299.3,306.7
XS GIS Cut Line= 3
2395513.08614979653847.934521499     2395963.274      653897.248
      2396360.11      653930.482
#Sta/Elev= 30
       0 3082.01   102.3 3032.58   142.5 3015.35   186.8 3003.56   279.3 2942.55
   331.6 2916.03   347.7 2903.73   359.8 2897.99     388 2874.36   408.1 2845.97
   412.1 2842.47   427.8 2838.17   432.2 2836.01   452.3 2835.71   464.4 2836.78
     468 2839.71   504.5 2876.46   524.3 2893.23   532.6 2904.87   556.7 2929.41
   568.7 2946.74   576.1 2953.74   605.8 2974.73     633 2997.95   677.1 3024.19
   713.3 3048.71   729.3 3066.92   737.3 3073.44   801.6 3091.91   851.1 3100.91
#Mann= 3 ,-1 , 0
       0      .1       0   427.8    .045       0     468      .1       0
Bank Sta=427.8,468
XS Rating Curve= 0 ,0
Exp/Cntr=0.3,0.1

Type RM Length L Ch R = 1 ,70024   ,324.6,300.7,288.4
XS GIS Cut Line= 3
     2395465.961      653892.4652395882.57245215654185.526486826
     2396264.001      654247.152
#Sta/Elev= 30
       0 3085.51    68.3  3040.8   129.4 3004.11   152.6 2987.87   186.8 2969.25
   203.3 2956.95     221 2946.86   283.7  2902.2   306.6  2884.2   323.7 2867.59
   343.3 2853.16   362.9 2834.77   372.6 2829.54   384.1 2828.18   418.6 2829.35
   438.7 2835.05   455.9 2851.64   470.3 2860.83   507.6 2890.38   525.7 2913.16
   554.1 2937.93   578.4 2956.26   610.8 2952.37   636.3 2954.93   671.6 2964.46
     704 2980.66   786.3 3000.14   853.9 3023.98     870 3033.33   895.7 3035.12
#Mann= 3 ,-1 , 0
       0      .1       0   372.6    .045       0   418.6      .1       0
Bank Sta=372.6,418.6
XS Rating Curve= 0 ,0
Exp/Cntr=0.3,0.1

Type RM Length L Ch R = 1 ,69723   ,297.9,300,298
XS GIS Cut Line= 3
2395453.39659085654461.678101244     2395832.866      654378.437
 2396235.3814785654296.573812759
#Sta/Elev= 30
       0 3013.74   140.6 2952.45   222.5 2912.02     243 2900.26   258.7 2894.77
     288 2879.53   315.8 2867.58   357.7 2834.44   366.2 2824.07   381.1  2812.8
   386.3 2809.59   389.7  2809.5   401.7 2812.82   410.8 2814.95     419 2822.15
   435.3 2829.88   451.6  2849.2   488.4 2878.52   542.3 2929.83   565.9 2948.63
   582.3 2958.55   610.8 2979.96   623.8 2986.96   680.2 3026.73   704.7 3039.98
   728.9 3056.44   753.7 3066.82   765.9 3075.13     770 3076.01   799.2 3065.94
#Mann= 3 ,-1 , 0
       0      .1       0   381.1    .045       0   401.7      .1       0
Bank Sta=381.1,401.7
XS Rating Curve= 0 ,0
Exp/Cntr=0.3,0.1

Type RM Length L Ch R = 1 ,69423   ,299.2,300,299.7
XS GIS Cut Line= 3
     2395555.584      654757.616     2395952.849      654649.552
     2396343.025      654521.259
#Sta/Elev= 30
       0 3063.89    36.4  3041.1   123.5 2992.55   177.1 2958.73   193.3 2951.82
   272.7 2906.88   285.1  2902.9   297.6 2895.23   318.3 2879.48     339 2852.35
   380.5  2816.8   392.6 2804.43   405.4 2801.77   426.3 2804.17     439 2813.68
     447 2815.58   451.6 2818.75   472.3 2848.85   497.9 2869.87   551.6 2902.26
   582.1 2921.86   592.8 2930.43   603.2 2933.89   632.7  2951.9   670.5 2978.98
   687.4  2988.5   712.7 3008.44   737.9 3022.25   808.2 3075.53   822.4 3084.03
#Mann= 3 ,-1 , 0
       0      .1       0   392.6    .045       0   426.3      .1       0
Bank Sta=392.6,426.3
XS Rating Curve= 0 ,0
Exp/Cntr=0.3,0.1

Type RM Length L Ch R = 1 ,69123   ,289.4,300,304.6
XS GIS Cut Line= 3
     2395680.195      655040.671     2396079.001      654917.487
 2396473.4485215654805.302636619
#Sta/Elev= 30
       0 3043.44    19.4 3039.15    36.2 3031.91    94.8 2998.16   132.4 2970.19
   195.2 2931.78   228.7 2912.57     279 2887.22   291.5 2884.26   312.5 2871.58
   329.2 2858.32   341.8 2850.95   354.3 2836.36   366.9 2824.94   379.5 2809.32
   396.9 2797.37   404.6 2794.01   417.1 2793.55   429.6 2796.75   442.1 2806.51
   454.9 2826.79   487.8 2853.32   504.5 2860.73   579.3 2911.96   591.8 2925.03
   658.9  2970.4   695.8 2998.93   710.7 3007.81   752.8 3042.23   827.5 3094.83
#Mann= 3 ,-1 , 0
       0      .1       0   396.9    .045       0   429.6      .1       0
Bank Sta=396.9,429.6
XS Rating Curve= 0 ,0
Exp/Cntr=0.3,0.1

Type RM Length L Ch R = 1 ,68823   ,302.4,300,291.8
XS GIS Cut Line= 3
     2395682.887      655138.465        2396091.      655205.169
     2396497.357       655249.57
#Sta/Elev= 30
       0 3069.67    76.9 3019.69   121.4 2986.52   145.8 2971.23     166 2954.87
   186.3 2942.28   214.7 2919.72   271.4 2880.07   299.8 2863.72     316 2851.51
   336.3 2840.59   352.5 2827.05   364.6 2819.41   386.9  2796.5   399.4 2788.44
   405.2 2786.49   417.3 2786.24   443.9 2788.92   449.5 2792.04   465.6  2812.5
   485.7    2832   528.7 2863.68   646.2  2938.2   659.8 2944.71   690.5 2964.53
     703 2970.82   747.2 2999.96   783.5 3019.28   799.6 3026.06   822.3 3039.65
#Mann= 3 ,-1 , 0
       0      .1       0   399.4    .045       0   443.9      .1       0
Bank Sta=399.4,443.9
XS Rating Curve= 0 ,0
Exp/Cntr=0.3,0.1

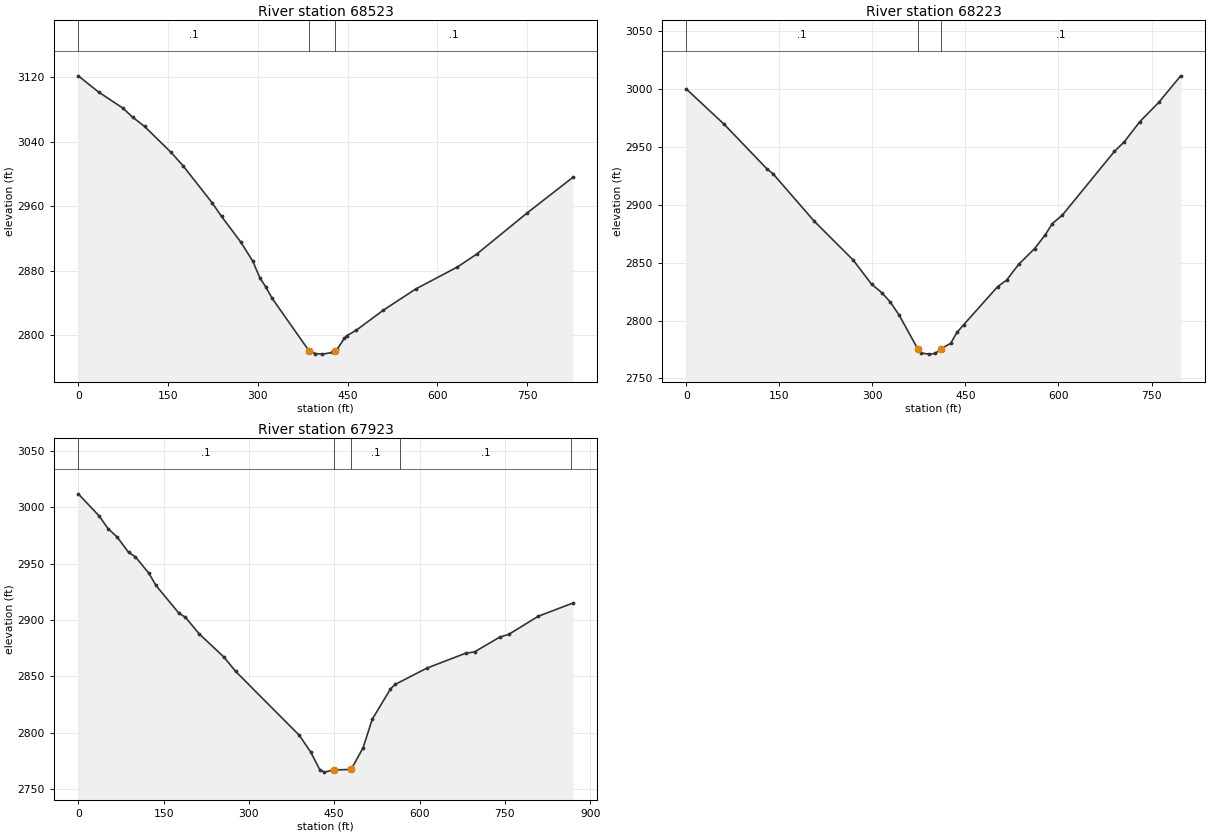
Type RM Length L Ch R = 1 ,68523   ,308.3,300,288.1
XS GIS Cut Line= 3
     2395672.656      655540.194     2396078.944      655498.557
2396494.14281553655453.949040224
#Sta/Elev= 30
       0 3121.85    34.3 3101.51    74.5 3081.79    90.6  3070.6   110.7    3059
   154.9 3026.83     175 3010.21   223.3 2964.47   239.3 2947.26   271.5 2915.33
   291.6 2891.51   303.7 2870.43   313.1 2859.87     324 2845.33   384.1 2781.75
   386.2  2780.4   396.2  2776.8   407.9 2776.15   424.3 2778.22   428.3 2779.97
   432.4 2782.11   444.4 2795.71   448.4 2798.95   464.5 2805.89   509.6 2830.76
   564.1 2857.21   633.2 2884.33   665.9 2900.56   749.4 2951.24     826 2995.61
#Mann= 3 ,-1 , 0
       0      .1       0   386.2    .045       0   428.3      .1       0
Bank Sta=386.2,428.3
XS Rating Curve= 0 ,0
Exp/Cntr=0.3,0.1

Type RM Length L Ch R = 1 ,68223   ,292.2,300,308.7
XS GIS Cut Line= 3
2395877.07185576655972.005631069     2396208.407      655759.836
 2396531.4880749655518.048409155
#Sta/Elev= 30
       0 3000.28    61.4 2969.54   130.2 2931.08   139.7 2927.03   206.2 2885.97
   269.1 2852.31   298.8  2831.4   315.5 2823.99   329.2 2815.83   343.3 2804.57
   372.9 2775.81   378.4 2771.93   391.5 2770.98   401.5 2771.53   411.4 2775.84
   426.3 2780.35   436.3 2789.69   447.2 2796.39   501.8 2829.25   516.3 2834.95
   535.8 2848.55   561.5 2862.21   578.7 2874.13   590.1 2883.83   606.2  2891.1
   690.1 2946.18   706.1 2954.54   731.1 2971.92   761.6 2988.57     797 3011.57
#Mann= 3 ,-1 , 0
       0      .1       0   372.9    .045       0   411.4      .1       0
Bank Sta=372.9,411.4
XS Rating Curve= 0 ,0
Exp/Cntr=0.3,0.1

Type RM Length L Ch R = 1 ,67923   ,304.8,300,284.9
XS GIS Cut Line= 3
     2395862.425      656030.592     2396320.363      656010.242
     2396731.198      656002.572
#Sta/Elev= 30
       0 3012.09    36.4 2992.62    52.4 2981.21    68.4 2973.76    88.4 2960.18
   100.4 2956.25   124.4 2941.43   136.5 2930.87   176.6 2906.38   188.5 2902.47
   212.5 2887.88   256.2 2867.19   276.6  2854.6   388.7 2797.76   408.7 2782.89
   424.7 2767.24   432.7 2765.14   448.8 2767.07   479.7 2767.52   500.8 2786.79
   516.8 2811.98   548.8 2838.91   556.8  2842.9   612.8 2857.41   680.8 2870.62
   696.8 2871.88   740.8 2884.89   756.8 2887.38   808.8 2903.48   869.3 2915.12
#Mann= 5 ,-1 , 0
       0      .1       0   448.8    .045       0   479.7      .1       0
  565.05      .1       0  866.03      .1       0
Bank Sta=448.8,479.7
XS Rating Curve= 0 ,0
Exp/Cntr=0.3,0.1