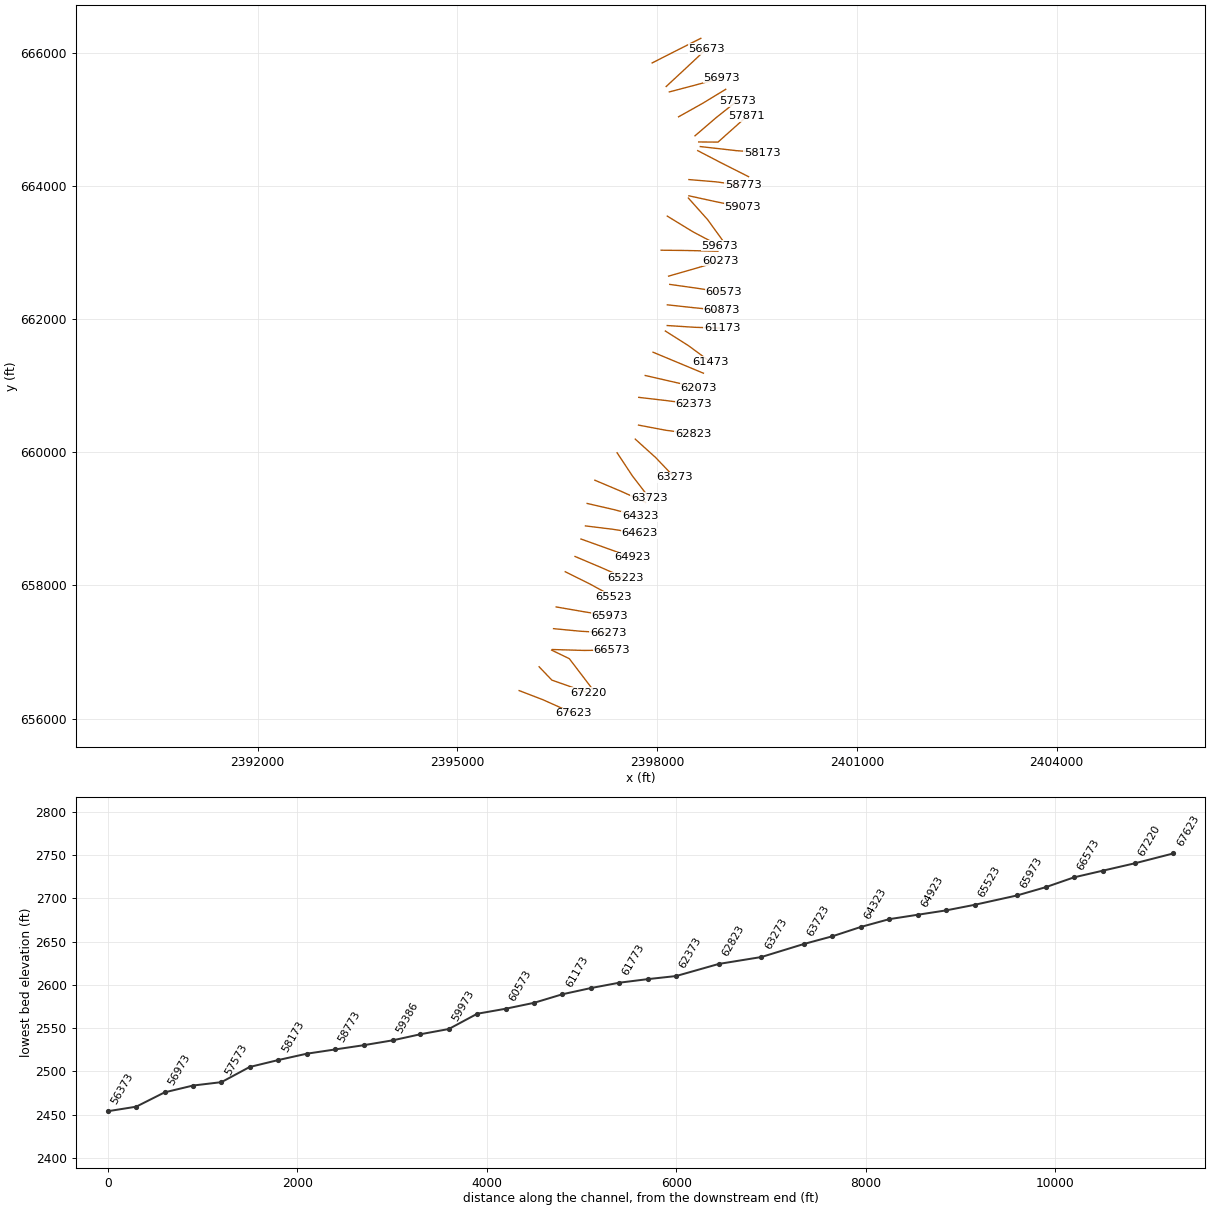
HEC-RAS study SENECACK.prj: SENECACK

--- SENECACK.g03 (geometry) --- (continued)

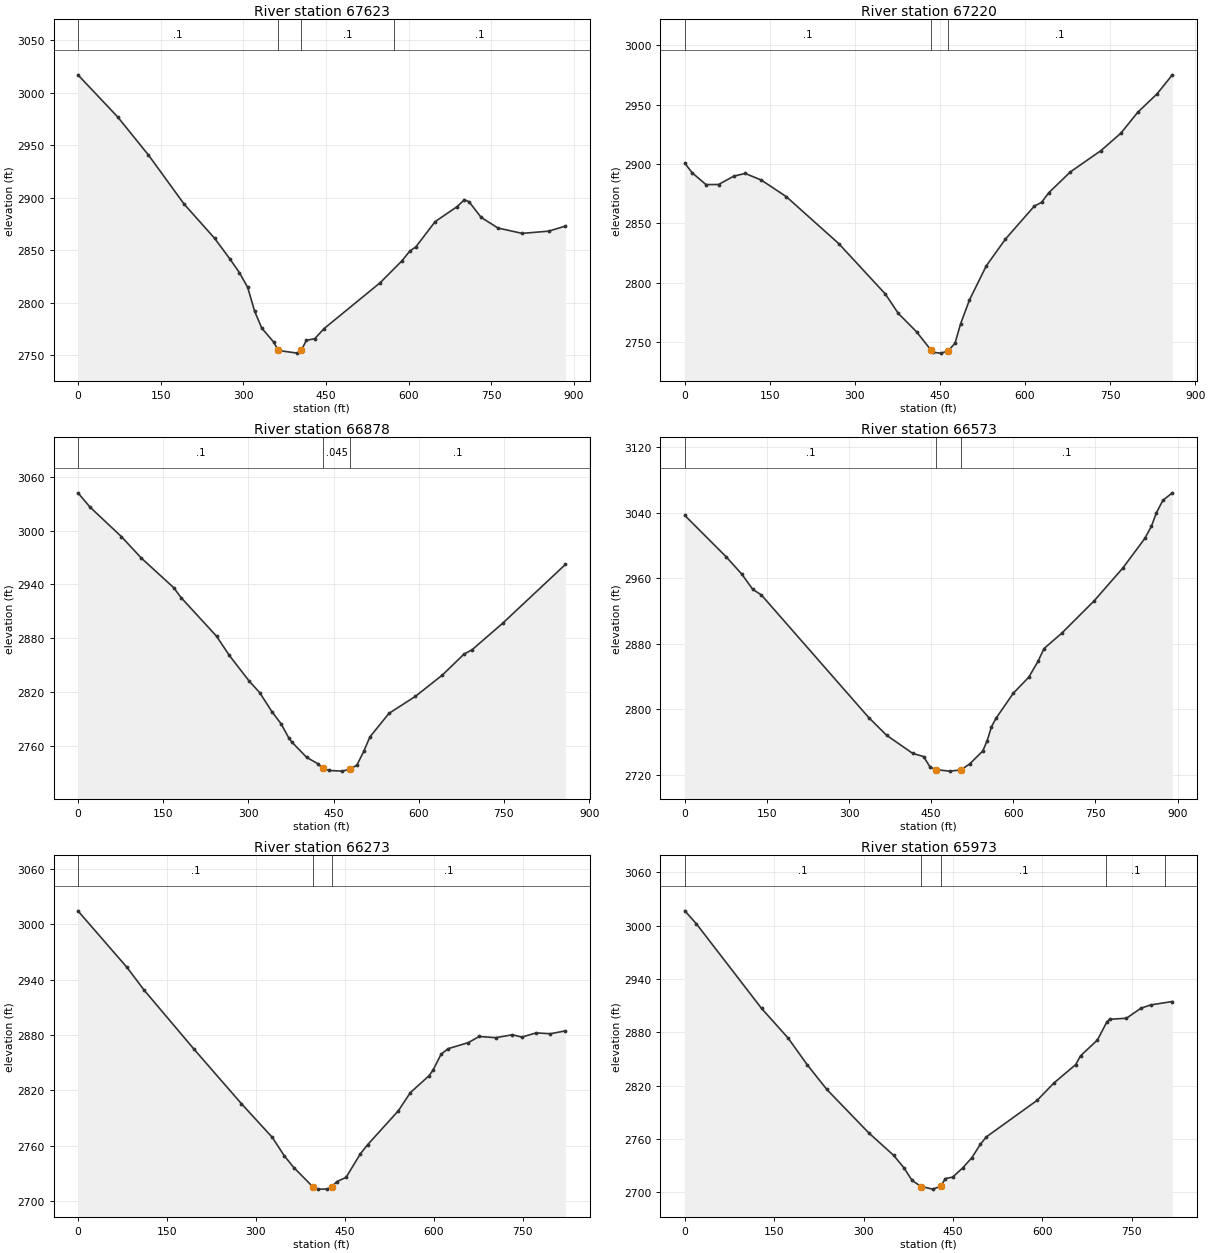
Type RM Length L Ch R = 1 ,67623   ,399,403.8,394.6
XS GIS Cut Line= 3
2395927.40089043656420.058631069     2396284.579      656282.666
     2396742.406      656077.525
#Sta/Elev= 30
       0 3016.99    72.2 2976.83   127.9 2940.63   192.7 2893.78   247.9 2861.26
   275.9  2841.4   292.9 2828.56   307.9 2814.47   320.7 2791.47   333.6 2775.59
     355 2762.39   363.6 2754.32   398.2  2751.8   405.3 2754.56   414.4 2763.99
   429.6 2765.57   446.4 2775.11   548.4 2818.96   587.6 2839.65   602.1  2849.1
     613 2853.03   648.1 2877.15   687.5 2891.24   700.7 2897.85   709.4 2896.15
   731.3 2881.22     762    2871   805.9 2865.91   854.1 2868.05   884.4 2872.87
#Mann= 4 ,-1 , 0
       0      .1       0   363.6    .045       0   405.3      .1       0
  573.65      .1       0
Bank Sta=363.6,405.3
XS Rating Curve= 0 ,0
Exp/Cntr=0.3,0.1

Type RM Length L Ch R = 1 ,67220   ,350.5,341.8,328.7
XS GIS Cut Line= 3
     2396227.278      656777.8672396418.47753952656577.606112345
     2396968.315      656383.963
#Sta/Elev= 30
       0 2900.55      13 2892.46    37.3 2882.55    59.4 2882.61    86.6 2889.69
   106.4 2891.94   134.7 2886.39   178.8 2872.43   271.5 2832.78   353.5 2790.38
   376.4 2774.02   408.6 2758.48   434.1 2743.03   438.3 2741.11     451 2740.47
   463.8 2742.05   476.5 2748.82   486.2 2764.99   501.9  2785.2   531.6 2814.02
   565.5 2836.66   616.4 2864.43   629.1 2867.54   641.9  2875.7     680 2893.26
     734 2911.23   769.1 2925.93   798.8 2943.52   832.7 2958.97   859.8 2975.06
#Mann= 3 ,-1 , 0
       0      .1       0   434.1    .045       0   463.8      .1       0
Bank Sta=434.1,463.8
XS Rating Curve= 0 ,0
Exp/Cntr=0.3,0.1

Type RM Length L Ch R = 1 ,66878   ,283.9,304.4,326.2
XS GIS Cut Line= 3
      2396415.08      657028.238 2396681.0584355656899.434011101
     2397021.858      656451.605
#Sta/Elev= 30
       0 3042.16    21.8 3025.93    76.5 2993.38   111.5  2969.5   168.5  2936.5
   181.8 2925.21   244.1 2882.27   266.3  2861.1   301.2 2832.52     320 2819.39
   341.4  2798.3   357.8 2784.49   371.3 2768.85   376.6 2764.31   402.7 2747.21
   421.9 2740.31   431.3 2734.98     442 2732.58   465.5 2731.86   479.8 2734.17
   491.2 2738.64   503.1 2753.79     514 2769.96   547.5 2796.21     594 2815.18
   641.8 2839.11   679.6 2862.25   693.9 2867.21   747.5 2896.59   858.3 2962.37
#Mann= 3 ,-1 , 0
       0      .1       0   431.3    .045       0   479.8      .1       0
Bank Sta=431.3,479.8
XS Rating Curve= 0 ,0
Exp/Cntr=0.3,0.1

Type RM Length L Ch R = 1 ,66573   ,297.8,300,298.3
XS GIS Cut Line= 3
2396426.84707212657037.165475726     2396908.459      657023.123
2397317.05233426657030.217072121
#Sta/Elev= 30
       0 3036.56    75.9 2985.75   103.9 2964.96     124  2946.3     140 2939.29
     336 2789.54   368.5 2768.01   416.1 2745.88   436.1 2741.95   448.1 2729.05
   459.12725.854   484.1 2724.15   504.1 2725.62   520.1 2732.85   544.1 2748.66
   552.1 2761.05   560.1 2778.38   568.1 2788.46   600.1 2819.47   628.1 2838.81
   645.1 2858.28   656.1 2873.92   688.3 2892.61   747.3 2931.98   800.2 2972.46
   840.2 3008.47   852.2 3023.31   861.3 3039.75   873.1 3054.92   890.5 3064.18
#Mann= 3 ,-1 , 0
       0      .1       0   459.1    .045       0   504.1      .1       0
Bank Sta=459.1,504.1
XS Rating Curve= 0 ,0
Exp/Cntr=0.3,0.1

Type RM Length L Ch R = 1 ,66273   ,300.2,300,297.1
XS GIS Cut Line= 3
     2396444.269      657350.432      2396850.95       657311.64
     2397264.126      657287.511
#Sta/Elev= 30
       0 3014.52    82.9 2953.09   111.9 2928.37   196.3 2864.17   275.7 2805.47
     328 2768.79     348 2748.96   364.1 2736.18   396.3 2715.27   404.3 2712.74
   420.3 2712.81     428 2715.13   436.4 2720.76   452.4 2725.55   476.4 2750.97
   488.5  2760.8   540.5 2797.68   560.7 2817.36   592.6 2835.87     599 2841.83
   612.7 2859.11   624.5 2865.04   658.6 2871.61   676.8 2878.28   704.8 2876.96
   732.9 2880.15   748.9  2877.6   772.9 2882.15     797 2881.26   822.4 2884.36
#Mann= 3 ,-1 , 0
       0      .1       0   396.3    .045       0     428      .1       0
Bank Sta=396.3,428
XS Rating Curve= 0 ,0
Exp/Cntr=0.3,0.1

Type RM Length L Ch R = 1 ,65973   ,451.2,450,440.1
XS GIS Cut Line= 3
     2396483.807      657676.883     2396892.302       657606.26
2397290.85329681657540.277633844
#Sta/Elev= 30
       0 3016.81    19.2 3002.35   128.8 2906.91   173.5 2873.38   205.9 2843.06
   238.4 2815.56   308.8 2766.65   350.4 2741.46   367.7 2727.46   381.5  2713.1
   396.7 2706.23   416.1 2703.29     430 2706.61   437.3 2715.23   449.5 2716.77
   466.9 2727.48   481.9 2738.71   496.1  2753.8   506.2 2762.13   591.4 2803.28
   619.8 2822.95   656.2 2843.57   664.4 2853.53   692.7 2871.27   708.3 2891.43
     713 2894.61   741.4 2895.82   765.7 2907.08   781.9 2910.78   818.5 2914.66
#Mann= 5 ,-1 , 0
       0      .1       0   396.7    .045       0     430      .1       0
  707.61      .1       0  806.93      .1       0
Bank Sta=396.7,430
XS Rating Curve= 0 ,0
Exp/Cntr=0.3,0.1

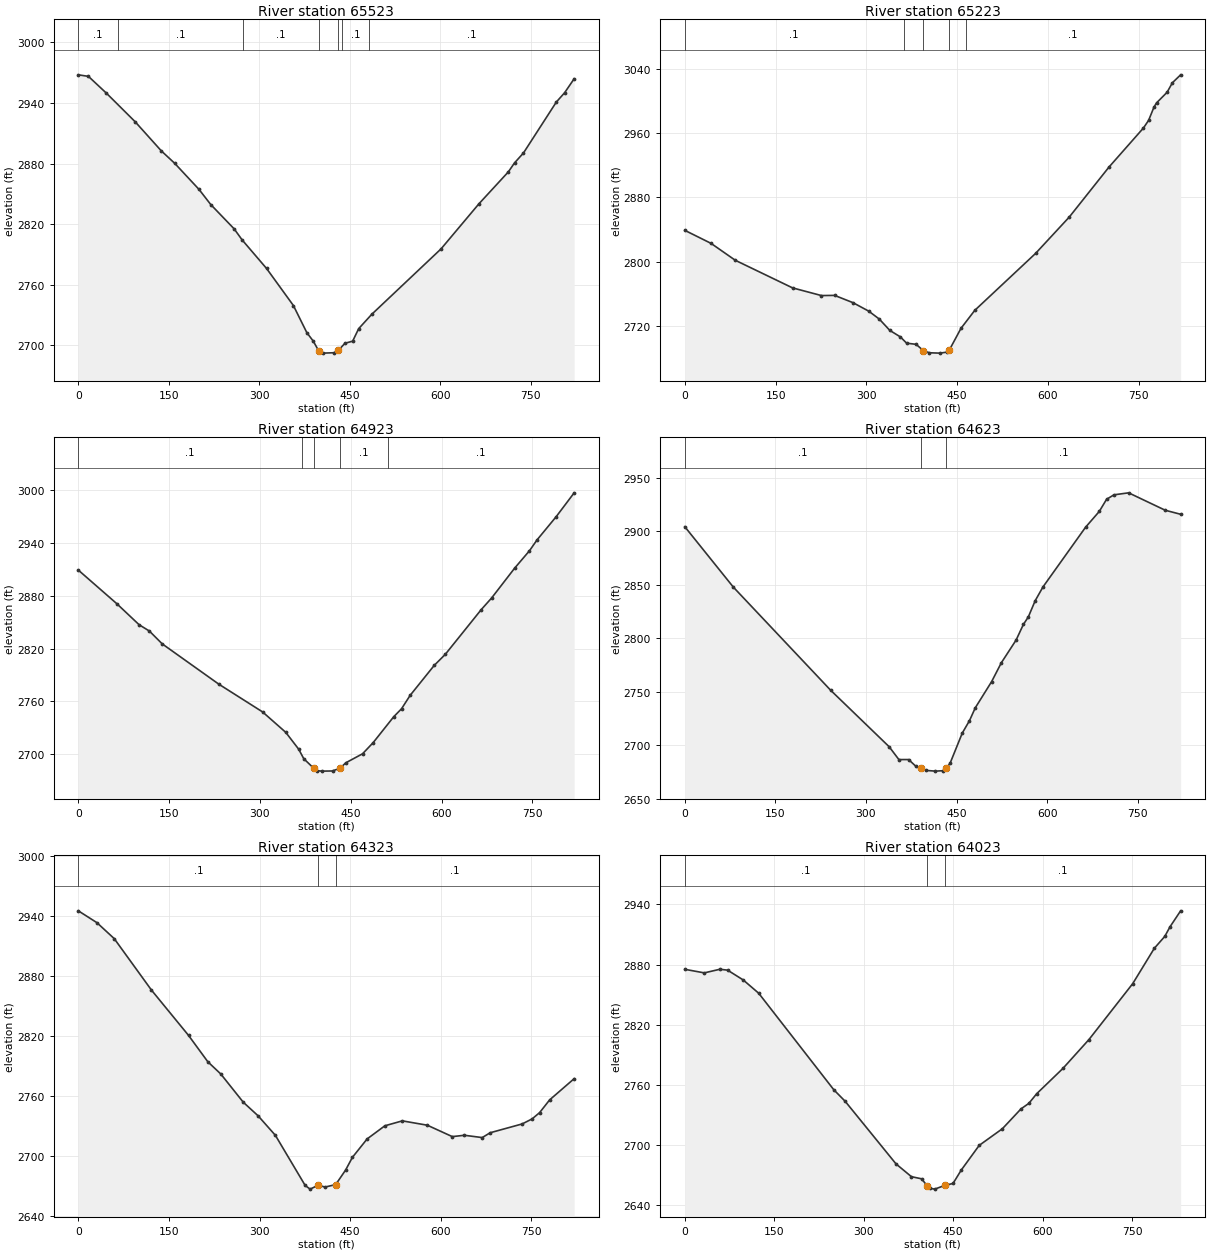
Type RM Length L Ch R = 1 ,65523   ,298.3,300,302.4
XS GIS Cut Line= 3
2396619.66755617658206.163149793     2396987.307      658022.978
     2397348.692      657826.846
#Sta/Elev= 30
       0 2967.73    16.7 2966.21    46.5 2949.61    94.2 2921.31   137.5 2892.53
   159.8 2880.16   200.1 2854.35   219.5 2839.41   258.2  2815.4   271.6 2804.36
     312 2776.18   356.5  2739.5   378.8 2712.64   389.5 2704.23   398.5 2694.57
   405.7 2692.41   423.8  2692.8   431.1 2695.18     442 2702.19   454.7 2704.22
   464.7  2716.6   486.4 2730.82   601.3 2795.57   664.1 2840.17   712.8 2871.72
   723.1 2880.63   737.9 2890.44   792.4 2940.84   806.1 2950.02   821.9 2963.85
#Mann= 7 ,-1 , 0
       0      .1       0   65.23      .1       0  273.25      .1       0
   398.5    .045       0   431.1      .1       0  436.66      .1       0
  482.09      .1       0
Bank Sta=398.5,431.1
XS Rating Curve= 0 ,0
Exp/Cntr=0.3,0.1

Type RM Length L Ch R = 1 ,65223   ,299.2,300,301.9
XS GIS Cut Line= 3
     2396766.901      658435.425     2397143.957      658275.604
     2397519.225      658111.714
#Sta/Elev= 30
       0 2838.99    43.3 2822.77    83.4 2801.69     178 2767.29   225.7 2757.72
   247.5 2757.93   277.9 2748.84   303.9 2738.27   321.3 2728.42   338.7 2714.28
   356.1 2706.22   366.4  2698.4   382.1 2696.96   393.9 2689.23   403.9 2686.44
   421.3    2686   433.5  2687.3   436.8 2689.64   456.2 2716.89     479 2739.31
   579.3 2810.15   635.2 2855.65   700.6 2917.75   757.4 2966.33   766.1 2975.97
   774.9 2992.35   779.2 2997.77   796.7 3011.05   805.4 3022.84     819 3032.74
#Mann= 5 ,-1 , 0
       0      .1       0  361.28      .1       0   393.9    .045       0
   436.8      .1       0  463.68      .1       0
Bank Sta=393.9,436.8
XS Rating Curve= 0 ,0
Exp/Cntr=0.3,0.1

Type RM Length L Ch R = 1 ,64923   ,295.3,300,303.9
XS GIS Cut Line= 3
      2396856.26      658697.452     2397241.698      658559.149
     2397627.136      658420.847
#Sta/Elev= 30
       0 2909.01    63.4 2870.99   100.4 2847.02   117.4 2839.85   138.6  2825.3
   232.1 2779.58   304.4 2748.09   342.6 2724.96   363.9 2705.91   372.4 2695.01
   388.6 2684.36   393.6 2681.54   402.1 2680.95   419.9 2681.13   432.4 2684.36
   441.8 2690.39   469.5 2700.64   487.1 2713.36   521.1 2742.76   533.9 2751.73
   548.1 2766.92   587.9 2800.93   606.1 2813.39   665.6 2864.26   682.7 2877.41
   720.8  2911.3   745.2 2930.97   757.7 2943.29   789.3 2969.61     819 2996.68
#Mann= 5 ,-1 , 0
       0      .1       0  369.22      .1       0   388.6    .045       0
   432.4      .1       0   511.9      .1       0
Bank Sta=388.6,432.4
XS Rating Curve= 0 ,0
Exp/Cntr=0.3,0.1

Type RM Length L Ch R = 1 ,64623   ,300,300,298.5
XS GIS Cut Line= 3
     2396922.898      658894.604     2397331.768      658844.394
     2397735.838      658780.636
#Sta/Elev= 30
       0 2904.18    80.4 2847.73   241.6 2751.38   338.4 2698.65   354.5 2686.67
   370.6  2686.7   382.7 2680.34   391.5 2678.87   398.8 2676.57     415 2675.88
   427.1 2676.25   433.3 2678.71   439.3 2683.27   459.5 2711.48   471.4 2723.02
     481 2735.04   508.1 2759.53   524.2 2777.17   548.6 2798.32   560.7 2812.96
   568.8 2819.88   580.2 2835.07   593.1 2847.95   663.7 2903.76   686.3 2918.45
   698.4  2929.8   710.6 2933.96   734.9 2935.83   795.6 2919.54     821  2915.8
#Mann= 3 ,-1 , 0
       0      .1       0   391.5    .045       0   433.3      .1       0
Bank Sta=391.5,433.3
XS Rating Curve= 0 ,0
Exp/Cntr=0.3,0.1

Type RM Length L Ch R = 1 ,64323   ,301.5,300,296.3
XS GIS Cut Line= 3
     2396948.731      659232.003     2397347.392       659140.28
     2397746.101      659036.652
#Sta/Elev= 30
       0 2944.97    30.8 2933.13    59.5 2917.15   121.1 2865.75   182.5 2820.48
   214.4 2794.16   235.8 2781.98   273.1 2753.73   297.6 2740.17   326.3 2720.63
   375.6 2670.56   383.8 2666.88   397.4 2670.86   408.4 2668.94   426.1 2671.41
   442.5 2685.89   453.9 2698.71   478.2 2717.04   507.6 2730.18   536.5 2735.09
   577.9 2730.74   619.2 2719.36   639.3 2720.69   668.8 2718.39     682 2723.23
   734.9 2732.02   751.4 2737.06   763.8 2743.32   780.4 2756.06     821 2777.26
#Mann= 3 ,-1 , 0
       0      .1       0   397.4    .045       0   426.1      .1       0
Bank Sta=397.4,426.1
XS Rating Curve= 0 ,0
Exp/Cntr=0.3,0.1

Type RM Length L Ch R = 1 ,64023   ,307.1,300,289.8
XS GIS Cut Line= 3
2397064.61755319659581.130978735     2397449.602      659418.332
     2397826.983      659249.076
#Sta/Elev= 30
       0 2875.21    32.7 2871.65    58.8 2875.25    71.8 2874.37      98 2864.59
   123.9  2851.4   249.9 2755.15   268.9 2743.71   354.3 2681.23   380.1 2668.52
   397.1  2666.4   406.2 2659.67   406.2 2659.65   410.5 2657.04   419.2 2656.11
   436.2 2659.85   449.9 2661.78   463.8 2675.22   493.8 2699.73   532.7 2716.32
   563.9  2736.1   577.1 2741.61   590.2  2751.2   634.1 2776.36   677.9 2805.23
   751.3 2860.96   787.5 2896.17     805 2907.98   813.8 2917.58   831.6  2933.5
#Mann= 3 ,-1 , 0
       0      .1       0   406.2    .045       0   436.2      .1       0
Bank Sta=406.2,436.2
XS Rating Curve= 0 ,0
Exp/Cntr=0.3,0.1

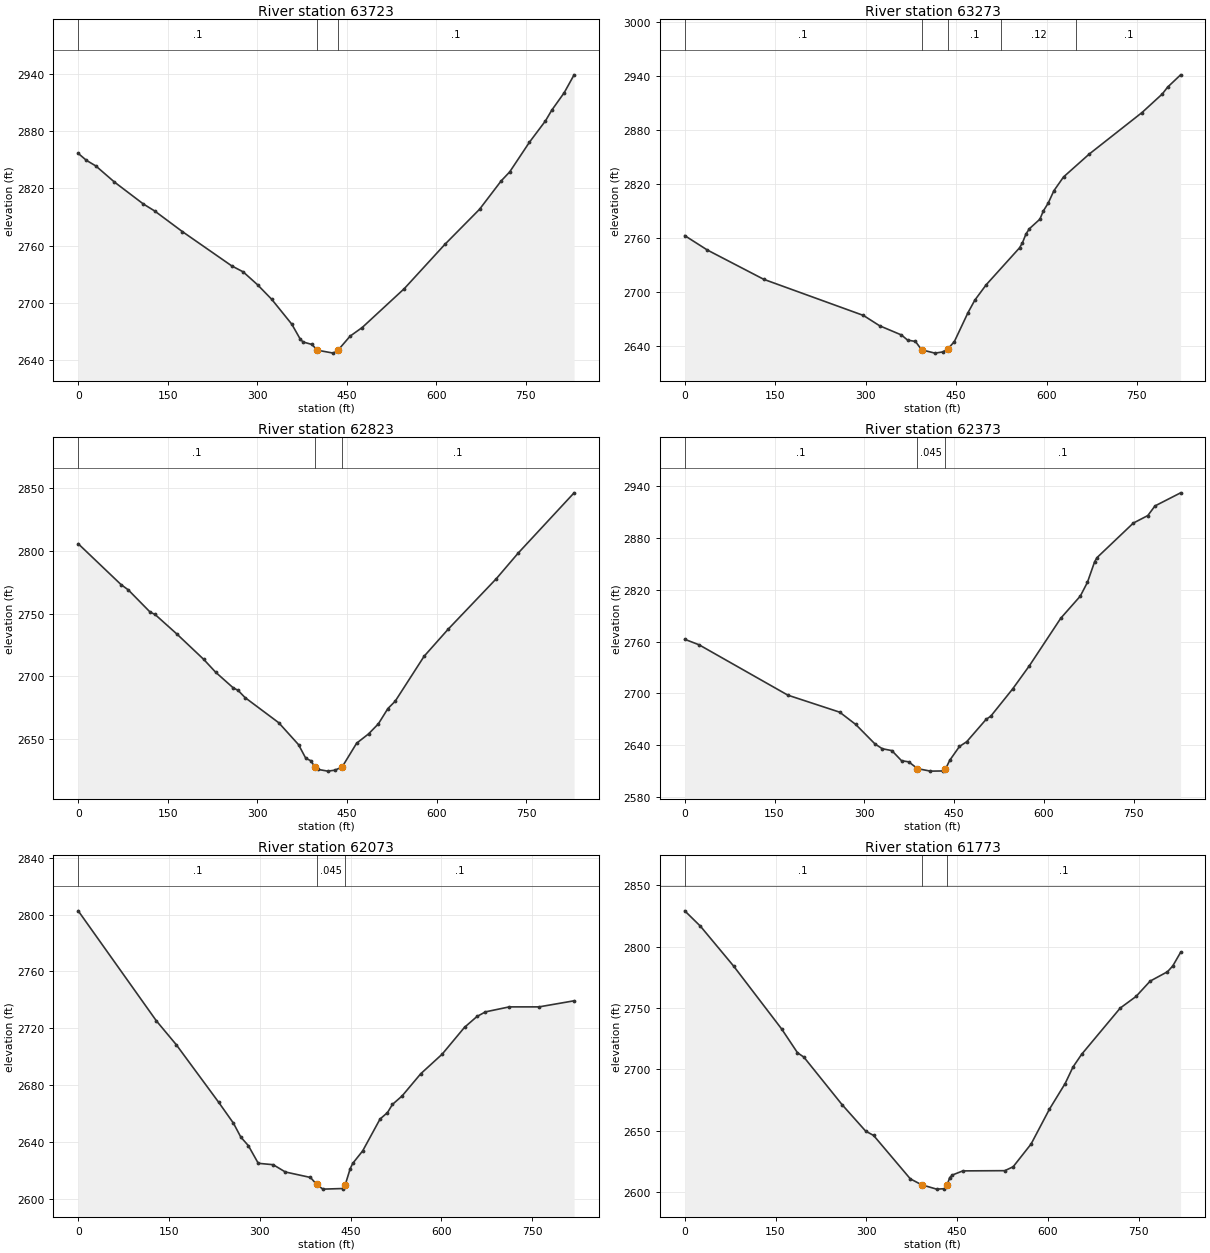
Type RM Length L Ch R = 1 ,63723   ,444.9,450,451.8
XS GIS Cut Line= 3
2397398.49005799659993.657088958      2397627.17      659647.177
     2397880.284      659317.124
#Sta/Elev= 30
       0 2856.79    13.7 2849.49    29.5 2843.61    60.8 2826.66   109.4 2803.59
   127.9 2796.47   174.7 2774.68   257.3 2738.76   276.5 2732.48   300.5    2719
   324.4 2703.63     358 2677.58   372.4 2661.61   377.1  2658.9   391.5 2656.38
   400.92650.316   427.6 2647.24     435    2650   455.8 2665.11     476 2674.12
   546.6 2714.95   614.7 2761.44   672.6 2798.12   708.9 2827.91   723.2 2837.37
   756.2 2868.44   783.1 2890.86   793.6 2902.03   814.5  2920.4   831.1 2939.18
#Mann= 3 ,-1 , 0
       0      .1       0   400.9    .045       0     435      .1       0
Bank Sta=400.9,435
XS Rating Curve= 0 ,0
Exp/Cntr=0.3,0.1

Type RM Length L Ch R = 1 ,63273   ,434.3,450,461
XS GIS Cut Line= 3
2397670.91702129660198.707872349      2397978.28      659920.882
     2398259.729      659625.401
#Sta/Elev= 30
       0 2762.73    37.5 2746.71     131 2714.18   296.3 2674.04   323.3 2662.52
   359.4 2652.32   369.6 2646.62   382.6 2645.13   392.9 2635.81     415 2632.15
   428.1  2633.5   435.9 2636.43   447.2 2645.04   469.8 2677.16   481.1 2691.04
   499.9 2708.07   555.2 2749.11     560 2754.64     566 2764.65   571.7 2770.45
     589 2780.98   594.8 2790.22   602.8 2798.83   612.2 2812.55   628.2 2827.89
   670.7 2853.27   758.4 2899.49     792  2920.1   800.8 2927.69   822.4 2941.38
#Mann= 5 ,-1 , 0
       0      .1       0   392.9    .045       0   435.9      .1       0
  524.92     .12       0  649.58      .1       0
Bank Sta=392.9,435.9
XS Rating Curve= 0 ,0
Exp/Cntr=0.3,0.1

Type RM Length L Ch R = 1 ,62823   ,448.8,450,450
XS GIS Cut Line= 3
2397720.28848936660409.383680844     2398130.486      660331.679
     2398539.667      660277.388
#Sta/Elev= 30
       0  2805.7    71.7  2773.1    83.9 2768.84   120.5 2751.09   128.7 2749.22
   165.1 2733.67   210.1  2713.4   230.1 2703.14     259 2690.87   267.8 2688.58
   279.3  2682.9   335.8 2662.79   368.9  2645.3   381.1 2634.37   389.3 2632.51
   396.7 2627.25   401.8 2625.51   417.8 2624.16   429.9 2624.92     442 2627.56
   466.2 2646.46   486.1 2653.86   502.5 2661.86   518.6 2674.16   530.7 2679.95
   579.2 2715.88   619.5  2737.5   700.2 2777.87   736.5 2798.14   830.3 2846.35
#Mann= 3 ,-1 , 0
       0      .1       0   396.7    .045       0     442      .1       0
Bank Sta=396.7,442
XS Rating Curve= 0 ,0
Exp/Cntr=0.3,0.1

Type RM Length L Ch R = 1 ,62373   ,303.4,300,298.6
XS GIS Cut Line= 3
2397723.04329787660826.285638313     2398134.535      660778.319
     2398545.138      660725.256
#Sta/Elev= 30
       0 2762.71    23.9 2756.36   172.3 2698.06   258.9 2678.37   285.6 2664.18
   317.8 2641.63   329.9 2636.13     346 2633.91   362.1 2622.26   374.2 2620.91
   388.7  2613.1   410.3 2610.19   430.6 2610.38   435.4 2612.36   442.7 2622.79
   458.9 2638.73     471 2644.21   503.2 2669.94   511.3 2673.84   547.6 2705.16
   575.8 2732.23   628.2 2787.18   660.7 2812.64   672.6 2828.55   684.7 2852.49
   688.8 2857.32   749.3 2897.16   773.5 2905.85   785.5 2916.99   828.3 2932.15
#Mann= 3 ,-1 , 0
       0      .1       0   388.7    .045       0   435.4      .1       0
Bank Sta=388.7,435.4
XS Rating Curve= 0 ,0
Exp/Cntr=0.3,0.1

Type RM Length L Ch R = 1 ,62073   ,302.8,300,295.2
XS GIS Cut Line= 3
     2397820.877      661154.977     2398220.003      661063.387
     2398619.129      660971.797
#Sta/Elev= 30
       0 2802.66   129.1 2725.15   161.9 2708.39     232 2667.78   256.4 2653.06
   268.6 2643.24     281 2637.25   297.4  2624.8     322 2623.82   342.1 2618.69
   383.6 2614.83   393.8 2609.91   404.1 2606.61   436.9 2607.03     441 2609.65
   449.2 2621.01   453.4 2624.76   469.8 2633.54   498.5 2655.98   510.8 2660.54
     519 2666.28     535 2672.28   565.7 2687.88   601.1 2701.68     638 2720.58
   658.6 2728.22   672.6 2731.48   711.9 2734.99   761.2    2735     819 2739.28
#Mann= 3 ,-1 , 0
       0      .1       0   393.8    .045       0     441      .1       0
Bank Sta=393.8,441
XS Rating Curve= 0 ,0
Exp/Cntr=0.3,0.1

Type RM Length L Ch R = 1 ,61773   ,303.1,300,295.3
XS GIS Cut Line= 3
     2397938.852       661504.36     2398316.802      661346.739
     2398694.751      661189.118
#Sta/Elev= 30
       0 2829.13    25.9 2816.61    80.6 2784.22   160.1 2732.89   186.2 2713.58
   196.8 2709.98   259.9 2671.26   298.9 2649.69   311.9 2646.22   372.6 2610.84
   391.1 2606.08   415.9 2602.49   428.9 2602.82   433.3 2605.77   437.6 2611.88
   441.9 2613.96   459.3 2617.34   528.6 2617.52   542.4  2620.7     572 2639.22
   602.3 2667.57   628.3 2688.51   641.3 2701.98   655.5 2712.28   719.3 2749.96
   745.3 2759.37   768.7  2771.9   797.3 2779.53     806 2784.22     819 2795.36
#Mann= 3 ,-1 , 0
       0      .1       0   391.1    .045       0   433.3      .1       0
Bank Sta=391.1,433.3
XS Rating Curve= 0 ,0
Exp/Cntr=0.3,0.1

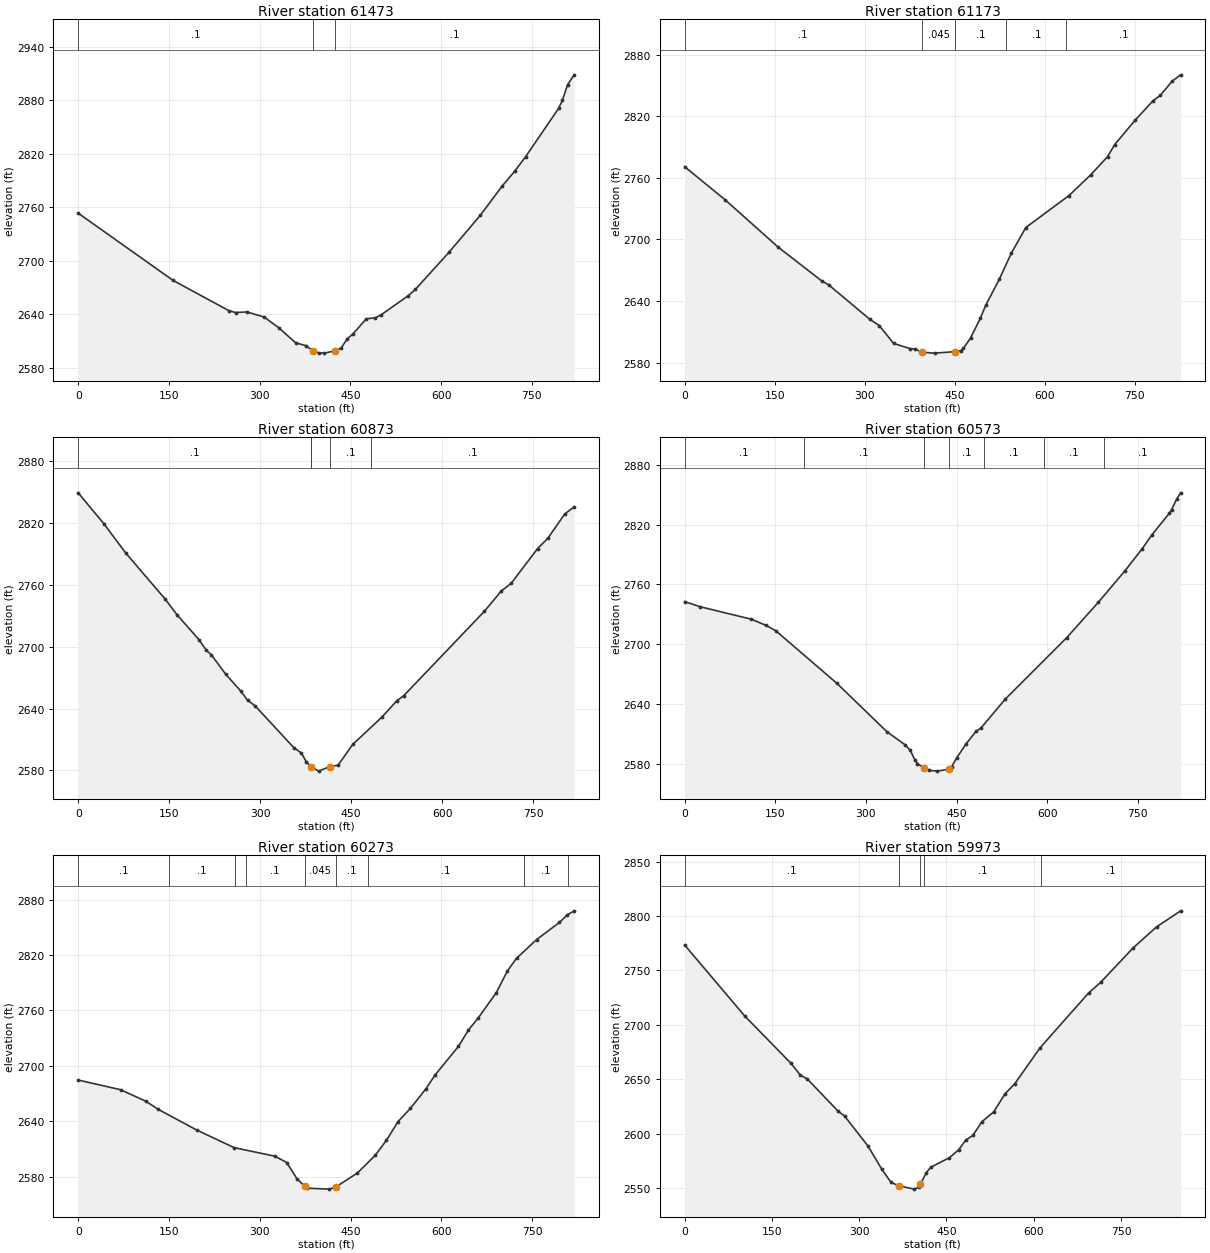
Type RM Length L Ch R = 1 ,61473   ,287.9,300,314.5
XS GIS Cut Line= 3
     2398123.008      661822.939     2398469.966      661603.128
     2398799.494      661360.385
#Sta/Elev= 30
       0  2753.4     157 2677.87   249.1 2643.99   260.1 2641.89   279.1 2642.55
   307.5 2636.79   331.2 2624.99   359.3 2608.03   376.7 2604.59     388 2598.95
   397.4 2596.61   406.9 2596.31   424.6 2598.91   434.3 2601.62   444.8 2612.34
   454.4  2617.9   476.3 2634.85   491.2 2635.94   501.1 2639.42   545.9 2660.85
   557.4 2667.79   613.5 2709.85   665.1 2751.23   701.1 2783.98   721.4 2800.23
   739.6 2816.66   794.2 2870.98   800.5    2880   809.1 2897.54     820 2908.72
#Mann= 3 ,-1 , 0
       0      .1       0     388    .045       0   424.6      .1       0
Bank Sta=388,424.6
XS Rating Curve= 0 ,0
Exp/Cntr=0.3,0.1

Type RM Length L Ch R = 1 ,61173   ,297.8,300,298.4
XS GIS Cut Line= 3
     2398151.279      661905.618     2398568.819      661878.778
     2398976.547       661865.97
#Sta/Elev= 30
       0  2770.7    67.6 2738.38   155.8 2692.36     228 2659.63     240 2655.62
   308.1 2622.28   324.1 2616.06   348.2 2598.56   376.2 2593.46   384.3 2593.28
   394.9 2590.01   416.3 2589.16   451.2 2590.63   460.3 2591.64   464.4 2593.75
   476.4    2604   492.4 2622.89   501.6 2635.74   524.4 2661.37   544.3 2686.57
   568.4  2711.5   640.4 2742.67   676.5 2762.79   704.5 2780.49   716.5 2792.34
     751 2816.36   780.5 2835.05   792.5 2840.23   812.5  2854.2   826.3 2860.21
#Mann= 5 ,-1 , 0
       0      .1       0   394.9    .045       0   451.2      .1       0
  535.89      .1       0  636.04      .1       0
Bank Sta=394.9,451.2
XS Rating Curve= 0 ,0
Exp/Cntr=0.3,0.1

Type RM Length L Ch R = 1 ,60873   ,300.1,300,298.3
XS GIS Cut Line= 3
2398152.76329787662216.752148916     2398548.024      662173.703
     2398966.084      662132.304
#Sta/Elev= 30
       0  2849.5    42.2 2819.56    78.4 2791.04   142.8 2746.72   163.1 2730.96
   199.2 2706.85   211.2 2696.58   219.3 2692.35   243.4 2673.22   267.6 2657.31
   279.2 2648.07   291.7 2642.65   355.4  2602.1   368.1  2596.8   376.2 2588.19
   384.2 2583.47   396.3 2579.26   415.12583.682   428.5 2585.04   452.6 2605.16
   500.8 2631.76   524.9 2647.32     537 2652.69   669.7 2734.46   697.8 2754.31
   713.9 2761.61   757.4 2795.36   774.2 2805.26   802.3 2829.03   817.7 2835.82
#Mann= 5 ,-1 , 0
       0      .1       0  383.18      .1       0   384.2    .045       0
   415.1      .1       0  482.68      .1       0
Bank Sta=384.2,415.1
XS Rating Curve= 0 ,0
Exp/Cntr=0.3,0.1

Type RM Length L Ch R = 1 ,60573   ,290.6,300,309.6
XS GIS Cut Line= 3
      2398189.35      662523.751     2398596.375      662466.292
2399001.38440426662405.198021285
#Sta/Elev= 30
       0 2742.66    25.6 2737.52   110.5 2724.97   134.7 2718.76   150.7 2713.44
   251.9 2660.61   334.7 2611.99     365 2598.74   373.1 2593.56   381.1 2583.45
   385.2 2579.78   395.7 2575.74   405.1 2573.24   417.5 2572.42   437.7 2574.39
   441.8 2576.81   449.9 2585.48     466 2600.14   482.2 2612.33   490.3 2615.76
   530.8 2644.91   631.9 2706.27   684.5 2741.95   728.9 2773.84   757.1 2795.79
   773.5 2809.99   801.8 2831.27   805.8 2835.05   813.9 2845.45   820.7 2851.93
#Mann= 7 ,-1 , 0
       0      .1       0  197.09      .1       0   395.7    .045       0
   437.7      .1       0  495.09      .1       0  594.41      .1       0
  693.74      .1       0
Bank Sta=395.7,437.7
XS Rating Curve= 0 ,0
Exp/Cntr=0.3,0.1

Type RM Length L Ch R = 1 ,60273   ,302.1,300,293.9
XS GIS Cut Line= 3
     2398171.634      662647.704       2398565.4      662761.001
     2398958.142      662876.537
#Sta/Elev= 30
       0 2684.64      70 2674.21   111.5 2661.79   132.3 2652.89   195.8 2630.55
   257.4 2611.56   325.1 2602.22   344.5 2595.33   361.2 2577.86   373.9  2569.8
   377.8 2567.63   414.8 2566.63   425.2 2568.83   461.2 2584.14   490.4  2603.1
     509 2619.39   528.3  2639.8   548.7 2654.01   573.8 2674.79   589.5 2690.19
     628 2721.08   644.6  2738.9   660.4  2751.6   690.5 2779.17   708.7 2802.56
   723.9 2816.38   757.2 2836.71   794.7 2855.13   807.2 2863.01   819.1 2867.76
#Mann= 9 ,-1 , 0
       0      .1       0  149.34      .1       0  259.16      .1       0
  276.44      .1       0   373.9    .045       0   425.2      .1       0
  478.99      .1       0  735.82      .1       0  809.38      .1       0
Bank Sta=373.9,425.2
XS Rating Curve= 0 ,0
Exp/Cntr=0.3,0.1

Type RM Length L Ch R = 1 ,59973   ,307.4,300,288.7
XS GIS Cut Line= 3
2398059.86485106663037.341872369     2398447.571      663033.014
     2398912.118      663022.418
#Sta/Elev= 30
       0  2773.3   102.9 2708.31   182.9 2664.52   198.9  2653.7   210.9 2650.21
   262.9 2621.09   274.9 2616.11   314.9 2588.75   338.9 2567.22   354.9 2555.12
   368.6 2552.01   394.9 2549.02   402.9 2550.84   405.2 2553.32   414.9 2563.89
   422.9 2569.14   454.9 2577.88   470.7 2585.06   482.9 2593.93   495.3 2598.36
   510.9 2610.98   530.9 2619.88   550.9 2636.82     567 2645.62     611    2679
   694.1 2729.19     715 2739.07     771 2770.83     811 2789.98   852.4 2804.77
#Mann= 5 ,-1 , 0
       0      .1       0   368.6    .045       0   405.2      .1       0
  411.62      .1       0  612.16      .1       0
Bank Sta=368.6,405.2
XS Rating Curve= 0 ,0
Exp/Cntr=0.3,0.1

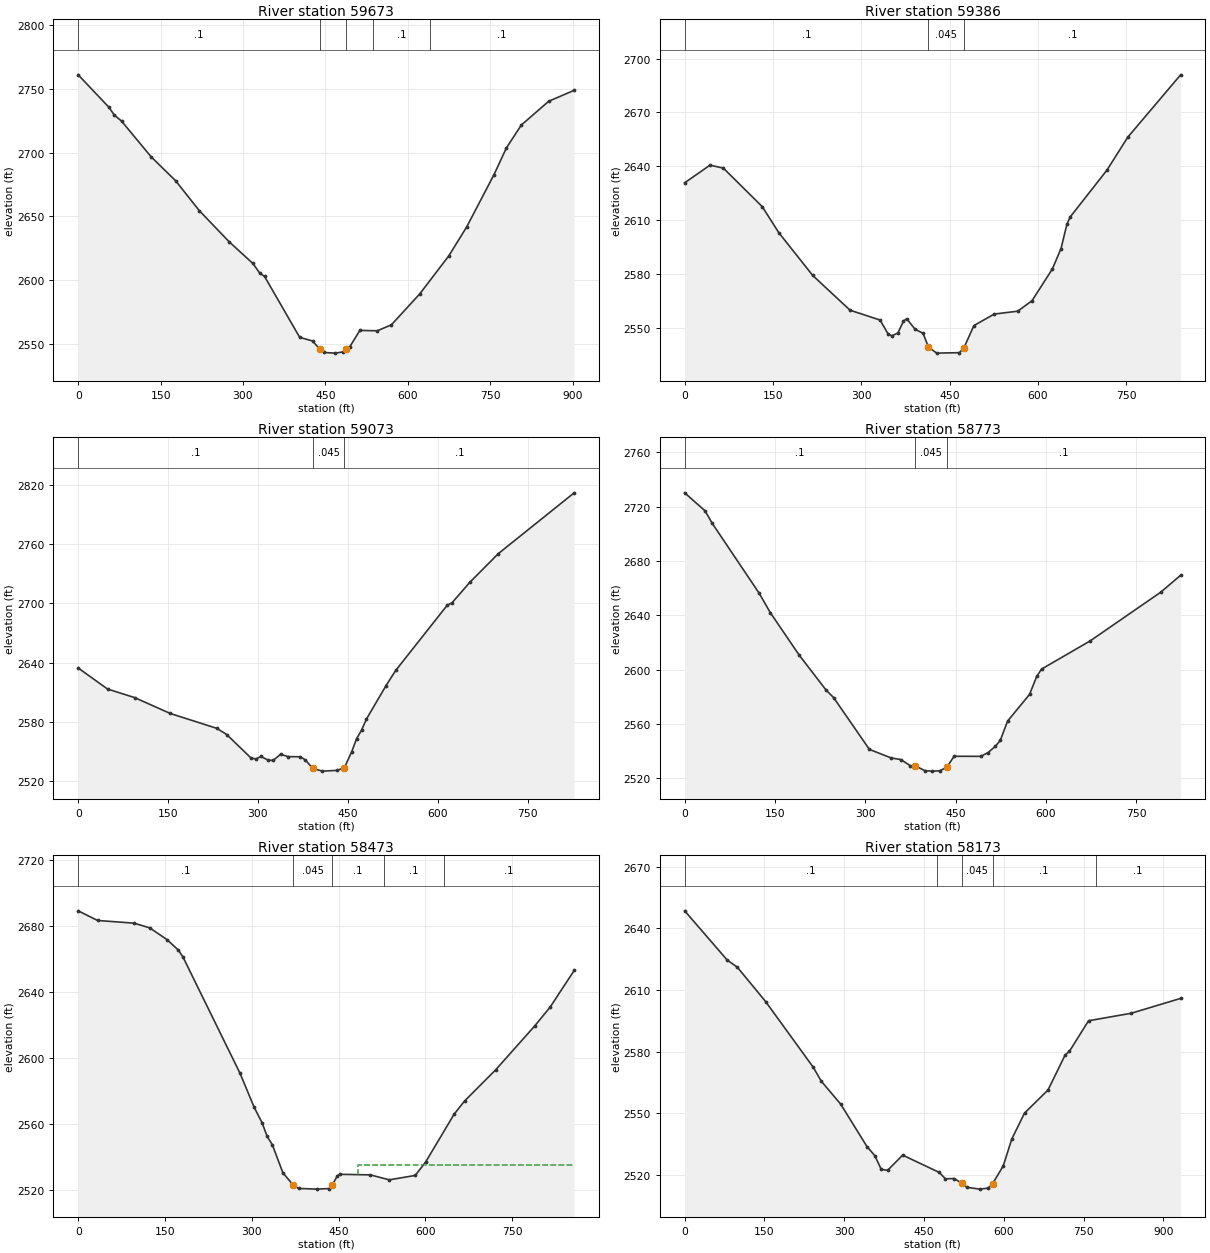
Type RM Length L Ch R = 1 ,59673   ,291.3,287.8,271
XS GIS Cut Line= 3
2398151.41544677663550.032340402     2398537.764       663313.67
      2398935.74      663103.495
#Sta/Elev= 30
       0 2760.98    55.5 2735.74    65.8 2729.46    78.9 2724.74   132.7  2696.8
   177.4    2678   220.6 2654.53   275.3    2630   318.1 2613.21   330.5 2605.67
   339.3 2603.05   403.3  2555.3   426.6  2552.5     440 2546.06   446.9 2543.49
   467.4 2542.97   482.3 2543.89   488.3 2546.47   494.7 2548.09   512.8 2560.77
   544.5 2560.47   570.2 2565.14   621.5 2589.18   674.8 2619.18   707.3 2641.81
   757.1 2682.83   779.7  2703.8   806.9 2721.68   856.6 2740.25     903 2748.85
#Mann= 5 ,-1 , 0
       0      .1       0     440    .045       0   488.3      .1       0
  536.15      .1       0  640.95      .1       0
Bank Sta=440,488.3
XS Rating Curve= 0 ,0
Exp/Cntr=0.3,0.1

Type RM Length L Ch R = 1 ,59386   ,297.1,312.2,337.4
XS GIS Cut Line= 3
2398468.37802129663821.2983829922398757.72104255663496.875744679
     2398996.764      663166.207
#Sta/Elev= 30
       0 2630.85      43 2640.66    65.7 2639.02   131.9 2617.55   159.8 2603.13
   217.6 2579.25     281 2559.92     332 2554.44   346.1 2546.46   352.1 2545.69
   362.3  2547.2   371.7 2553.82   377.3 2555.15   391.5 2549.31   405.2 2547.03
   414.2 2539.33   428.3 2536.02   466.8 2536.28   474.6 2539.03   491.4 2551.34
     526 2557.77   565.8 2559.36   590.2 2565.19   624.7 2582.85   639.5 2594.23
   649.4 2607.66   654.9 2611.75   717.6 2637.94     753 2656.28   842.7 2690.95
#Mann= 3 ,-1 , 0
       0      .1       0   414.2    .045       0   474.6      .1       0
Bank Sta=414.2,474.6
XS Rating Curve= 0 ,0
Exp/Cntr=0.3,0.1

Type RM Length L Ch R = 1 ,59073   ,295.7,300,301
XS GIS Cut Line= 3
     2398476.596      663854.986     2398887.115      663765.233
     2399286.607      663684.291
#Sta/Elev= 30
       0 2634.64    48.9 2613.38    94.1 2604.72   153.7 2588.62   231.5 2573.55
   247.9  2567.3   288.8 2543.36     297 2542.71   305.2 2545.11   317.5 2541.23
   325.7 2541.27   337.9 2547.44   350.2 2544.95   370.7 2544.82   378.9 2541.73
   391.6 2532.99   407.6 2530.29   432.1 2531.03   444.3 2533.83   456.6 2550.06
   464.7 2563.19   472.9 2571.68   481.1    2583   513.5 2616.51     530 2632.23
   615.7 2697.97   623.9  2700.6   653.6 2721.31   701.4 2750.46   827.8 2811.91
#Mann= 3 ,-1 , 0
       0      .1       0   391.6    .045       0   444.3      .1       0
Bank Sta=391.6,444.3
XS Rating Curve= 0 ,0
Exp/Cntr=0.3,0.1

Type RM Length L Ch R = 1 ,58773   ,311.3,300,289.4
XS GIS Cut Line= 3
     2398477.073      664098.781     2398884.169      664064.714
     2399295.589      664009.886
#Sta/Elev= 30
       0 2730.08    33.8 2716.84    45.8  2707.6   123.7 2656.26   142.1 2642.04
   190.5 2610.52   234.8 2585.05   247.3  2579.5   306.7 2541.42   342.9  2535.1
   358.9 2533.92     375 2529.31     383 2529.25     383 2529.26   399.1 2525.74
   411.1 2525.41   423.4 2525.62   435.3 2528.25   447.4 2536.34   491.8 2536.28
   503.9 2539.09   515.7 2543.58   524.1 2547.96   536.2 2562.19   572.7 2581.81
   584.6 2595.07   592.7 2600.46   673.4 2621.18   790.4 2656.94   823.6 2669.46
#Mann= 3 ,-1 , 0
       0      .1       0     383    .045       0   435.3      .1       0
Bank Sta=383,435.3
XS Rating Curve= 0 ,0
Exp/Cntr=0.3,0.1

Type RM Length L Ch R = 1 ,58473   ,289.6,300,307.8
XS GIS Cut Line= 3
     2398609.112        664533.8     2398968.978      664346.212
2399371.96320332664143.026539023
#Sta/Elev= 30
       0 2689.43    33.4 2683.58    96.6 2681.94   123.6 2679.09   153.4 2671.96
   173.3 2665.53   181.3 2661.22   279.7 2590.78   304.1 2570.16   317.7 2560.83
   326.6 2552.45   335.5 2547.44   353.7 2530.42   371.7  2522.9   380.8  2520.9
   412.6 2520.49   433.4 2520.83   439.2 2523.07   448.1 2528.74   452.6 2529.48
   504.9 2529.14   537.6 2526.13   582.5 2528.81   600.4 2536.94   649.7    2566
   667.6 2573.94   721.4  2592.9   788.6 2619.41   815.5 2630.93   857.1 2653.21
#Mann= 5 ,-1 , 0
       0      .1       0   371.7    .045       0   439.2      .1       0
  527.93      .1       0  632.09      .1       0
#XS Ineff= 2 , 0
                          483.92         2534.96
Permanent Ineff=
       F       F
Bank Sta=371.7,439.2
XS Rating Curve= 0 ,0
Exp/Cntr=0.3,0.1

Type RM Length L Ch R = 1 ,58173   ,277,302.1,324.9
XS GIS Cut Line= 3
      2398647.53       664594.77     2399191.081      664533.225
       2399575.3      664505.328
#Sta/Elev= 30
       0  2648.5    79.7 2624.63    99.1 2621.06   152.2 2604.37   241.5 2572.51
   256.8 2565.66   293.1 2554.57   342.7 2533.88   357.5 2529.44   369.6 2522.74
   381.6 2522.36   409.8 2529.72   478.3 2521.34   490.3  2518.2   506.4 2518.33
   521.3 2516.08   530.6 2514.06   554.7 2513.18   570.8 2513.69   578.8 2515.81
   578.8 2515.82   598.8 2524.44   614.9 2537.53   638.9 2550.17     683 2561.37
   715.1 2578.35   723.2 2580.15   759.2 2595.05   839.5  2598.7   932.3 2605.92
#Mann= 5 ,-1 , 0
       0      .1       0  474.06      .1       0   521.3    .045       0
   578.8      .1       0  772.97      .1       0
Bank Sta=521.3,578.8
XS Rating Curve= 0 ,0
Exp/Cntr=0.3,0.1

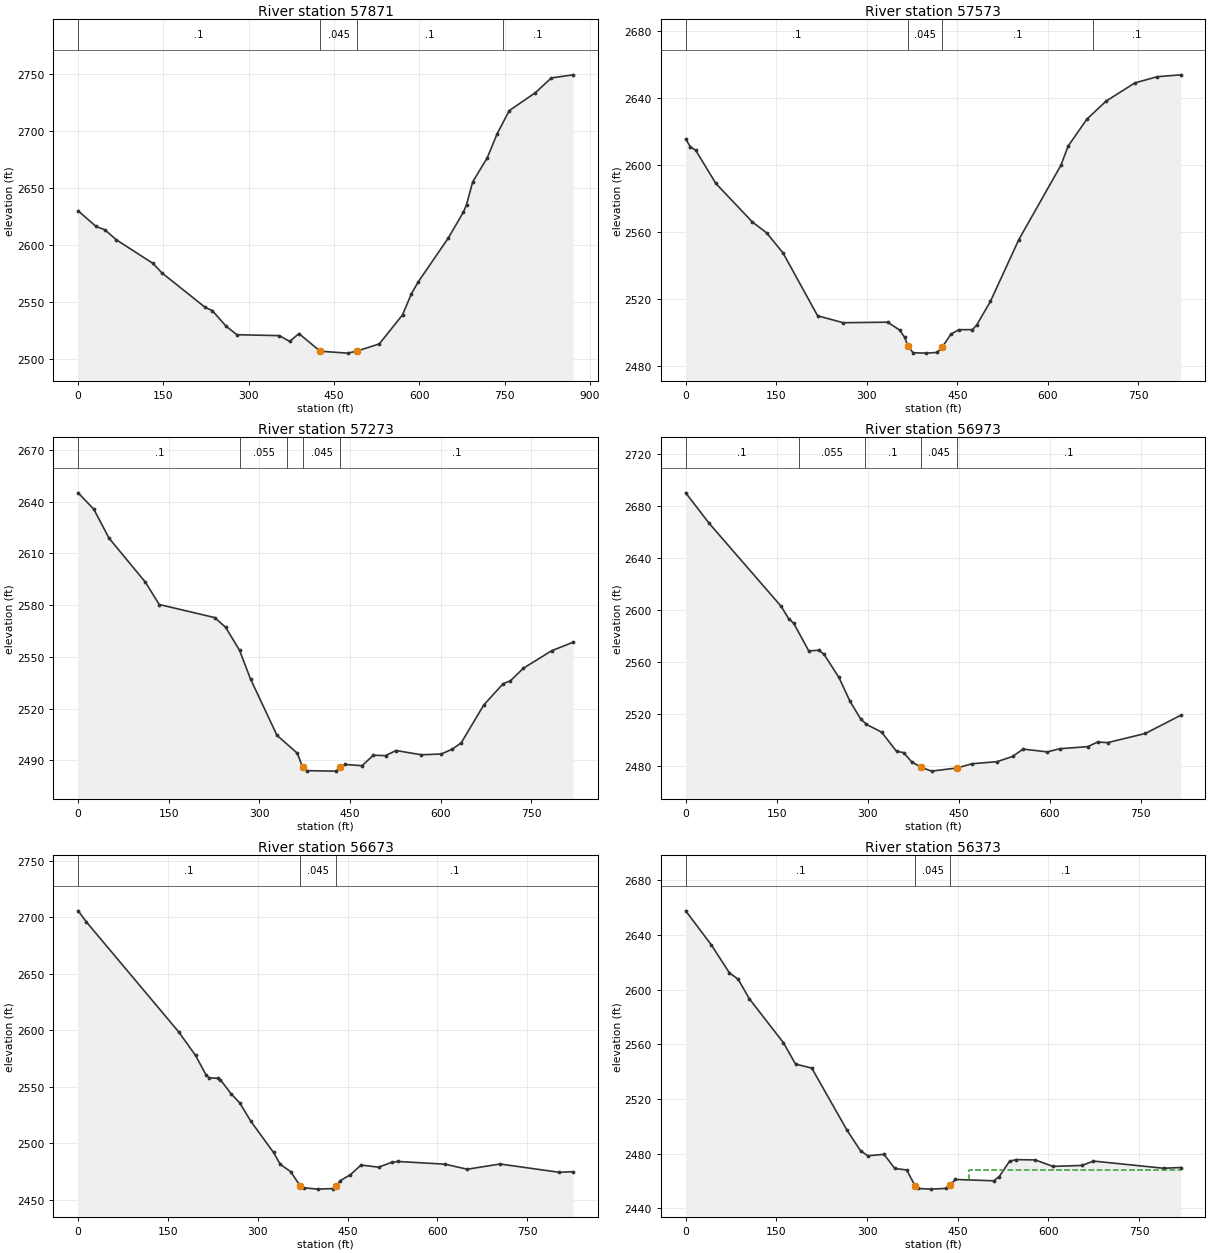
Type RM Length L Ch R = 1 ,57871   ,297.6,297.9,295.2
XS GIS Cut Line= 3
     2398623.371      664664.0152398913.59365464664661.915545071
     2399346.618      665048.455
#Sta/Elev= 30
       0 2630.13    31.4  2616.5    47.4 2613.38    66.7 2604.88   131.4 2584.06
   147.4 2575.66   223.4 2545.36     236 2542.49   260.1 2528.89   279.4 2521.33
   354.1 2520.52   372.2 2515.39   388.3 2522.35   425.8 2506.82   474.1 2505.16
   490.2 2506.93   529.7 2513.23   570.6 2538.78     586 2557.07     598 2567.58
     651 2606.21   677.8 2629.16   683.2 2635.65   694.1 2655.69   719.5 2676.61
   736.8 2697.58   758.3 2718.22   804.5 2734.03   832.3 2746.92   870.7 2749.67
#Mann= 4 ,-1 , 0
       0      .1       0   425.8    .045       0   490.2      .1       0
  747.05      .1       0
Bank Sta=425.8,490.2
XS Rating Curve= 0 ,0
Exp/Cntr=0.3,0.1

Type RM Length L Ch R = 1 ,57573   ,306.3,300,295.4
XS GIS Cut Line= 3
     2398569.045      664757.155     2398880.358      665024.844
     2399200.449      665279.944
#Sta/Elev= 30
       0 2615.41     7.5 2610.74    16.6 2608.61    49.7 2588.96   110.2 2565.93
   134.1 2559.35   161.3 2547.36   218.5 2509.93   260.7  2505.8   334.6 2506.11
   354.2 2501.45   362.7 2497.06   368.3 2491.62   376.8 2487.88   397.9 2487.66
   416.6 2488.07   425.1 2491.34   439.3 2498.97   452.4 2501.63     475 2501.66
     482 2504.41   504.8 2518.55   551.7 2555.29   621.5 2599.67   633.6 2611.18
   664.6 2627.21   696.3 2637.92   743.9 2648.78   780.9 2652.49   819.9 2653.62
#Mann= 4 ,-1 , 0
       0      .1       0   368.3    .045       0   425.1      .1       0
  674.85      .1       0
Bank Sta=368.3,425.1
XS Rating Curve= 0 ,0
Exp/Cntr=0.3,0.1

Type RM Length L Ch R = 1 ,57273   ,308.2,300,291.9
XS GIS Cut Line= 3
     2398321.581       665042.32     2398678.993      665242.064
     2399029.121      665455.088
#Sta/Elev= 30
       0 2645.07    25.8 2635.61    51.2 2618.74   111.3 2593.27   134.2 2580.33
   225.9 2572.76   244.2 2567.09   267.1  2553.8   285.4 2537.05   329.1 2504.51
   362.8 2494.09   371.7 2485.88   378.3 2484.01   426.4 2483.74   434.1 2485.88
   441.9  2487.6     470 2486.89   488.5 2492.96   508.8 2492.73   526.2 2495.69
   568.3 2493.21   601.1 2493.67   619.5 2496.52   634.2 2500.21   671.4 2522.08
   703.5 2534.45   715.5  2536.1   736.9 2543.36   783.7 2553.52   819.3 2558.46
#Mann= 5 ,-1 , 0
       0      .1       0  268.62    .055       0  345.82      .1       0
   371.7    .045       0   434.1      .1       0
Bank Sta=371.7,434.1
XS Rating Curve= 0 ,0
Exp/Cntr=0.3,0.1

Type RM Length L Ch R = 1 ,56973   ,285.5,300,314.4
XS GIS Cut Line= 3
     2398182.528      665415.969     2398579.646      665520.683
2398971.02066574665627.000224689
#Sta/Elev= 30
       0 2690.23    38.6 2666.77   157.4 2602.78   169.8 2593.23   178.1 2589.75
   202.9 2568.48   219.5 2568.97   227.7  2566.1   252.6 2548.06     271 2529.57
   288.3 2516.23   298.1 2511.83   322.9 2505.95   347.7 2491.08   359.4 2490.14
   372.5 2483.02   388.8 2478.67   405.6 2475.85   447.6  2478.3   471.9 2481.52
   513.4 2483.14   538.9 2487.13   556.4 2492.82   596.3 2490.67     617 2493.11
   663.2 2494.73   679.2 2498.26   695.8 2497.81   757.9 2504.85   816.2 2518.86
#Mann= 5 ,-1 , 0
       0      .1       0  186.17    .055       0  294.87      .1       0
   388.8    .045       0   447.6      .1       0
Bank Sta=388.8,447.6
XS Rating Curve= 0 ,0
Exp/Cntr=0.3,0.1

Type RM Length L Ch R = 1 ,56673   ,310.4,300,293.3
XS GIS Cut Line= 3
     2398135.265      665497.428     2398435.227      665775.786
2398739.78385021666061.066002775
#Sta/Elev= 30
       0  2705.7    13.9 2695.77   167.7 2598.63     196 2577.68   213.8  2560.2
   218.6 2557.92   232.8 2557.46   237.4 2556.22   255.4 2543.71   269.6  2535.8
   288.5 2519.26   326.2 2491.83   337.3 2481.36     355 2474.71   370.4 2462.44
   377.1 2460.49   399.8 2459.32     425 2459.81   431.3 2461.84   437.2 2466.67
   454.7 2472.13   472.3 2480.65   501.7 2478.75   523.7 2483.06   534.6 2483.79
   612.7  2481.4   649.7 2476.93   704.5 2481.56   803.2 2474.23   826.5 2474.76
#Mann= 3 ,-1 , 0
       0      .1       0   370.4    .045       0   431.3      .1       0
Bank Sta=370.4,431.3
XS Rating Curve= 0 ,0
Exp/Cntr=0.3,0.1

Type RM Length L Ch R = 1 ,56373   ,308,300,292.6
XS GIS Cut Line= 3
     2397924.812      665851.567     2398289.766      666037.303
     2398655.663      666221.192
#Sta/Elev= 30
       0 2657.71    42.6 2632.63    72.3 2612.33    86.7  2607.7   105.4 2593.28
   161.6 2561.26   181.7 2545.62   208.6 2542.61     267 2497.12   289.4 2482.05
   301.4 2478.45   328.1 2479.57     346 2469.17   365.7  2468.1   379.2 2456.67
   383.7 2454.56   405.5 2454.07   430.9 2454.59   437.5  2457.2   446.4 2461.13
   509.7 2460.17   518.7 2463.18   535.9 2474.52   546.7 2475.65   578.3 2475.45
   607.6  2470.7   655.7  2471.4   674.7 2474.59   791.1 2469.34     819 2469.88
#Mann= 3 ,-1 , 0
       0      .1       0   379.2    .045       0   437.5      .1       0
#XS Ineff= 2 , 0
                          469.03         2468.11
Permanent Ineff=
       F       F
Bank Sta=379.2,437.5
XS Rating Curve= 0 ,0
Exp/Cntr=0.3,0.1