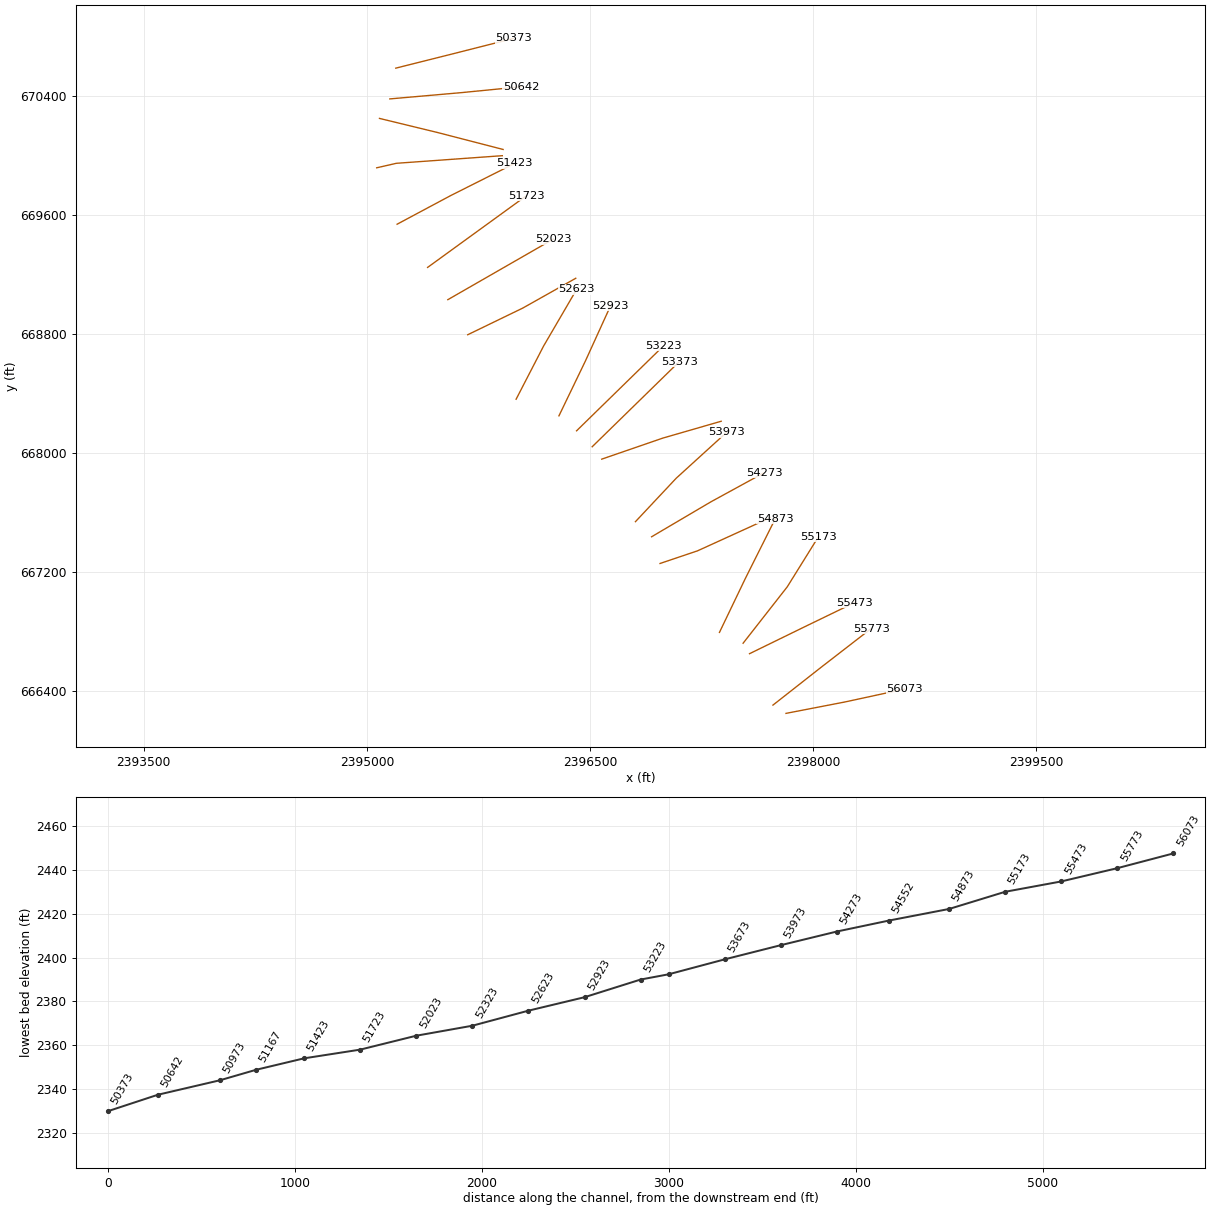
HEC-RAS study SENECACK.prj: SENECACK

--- SENECACK.g03 (geometry) --- (continued)

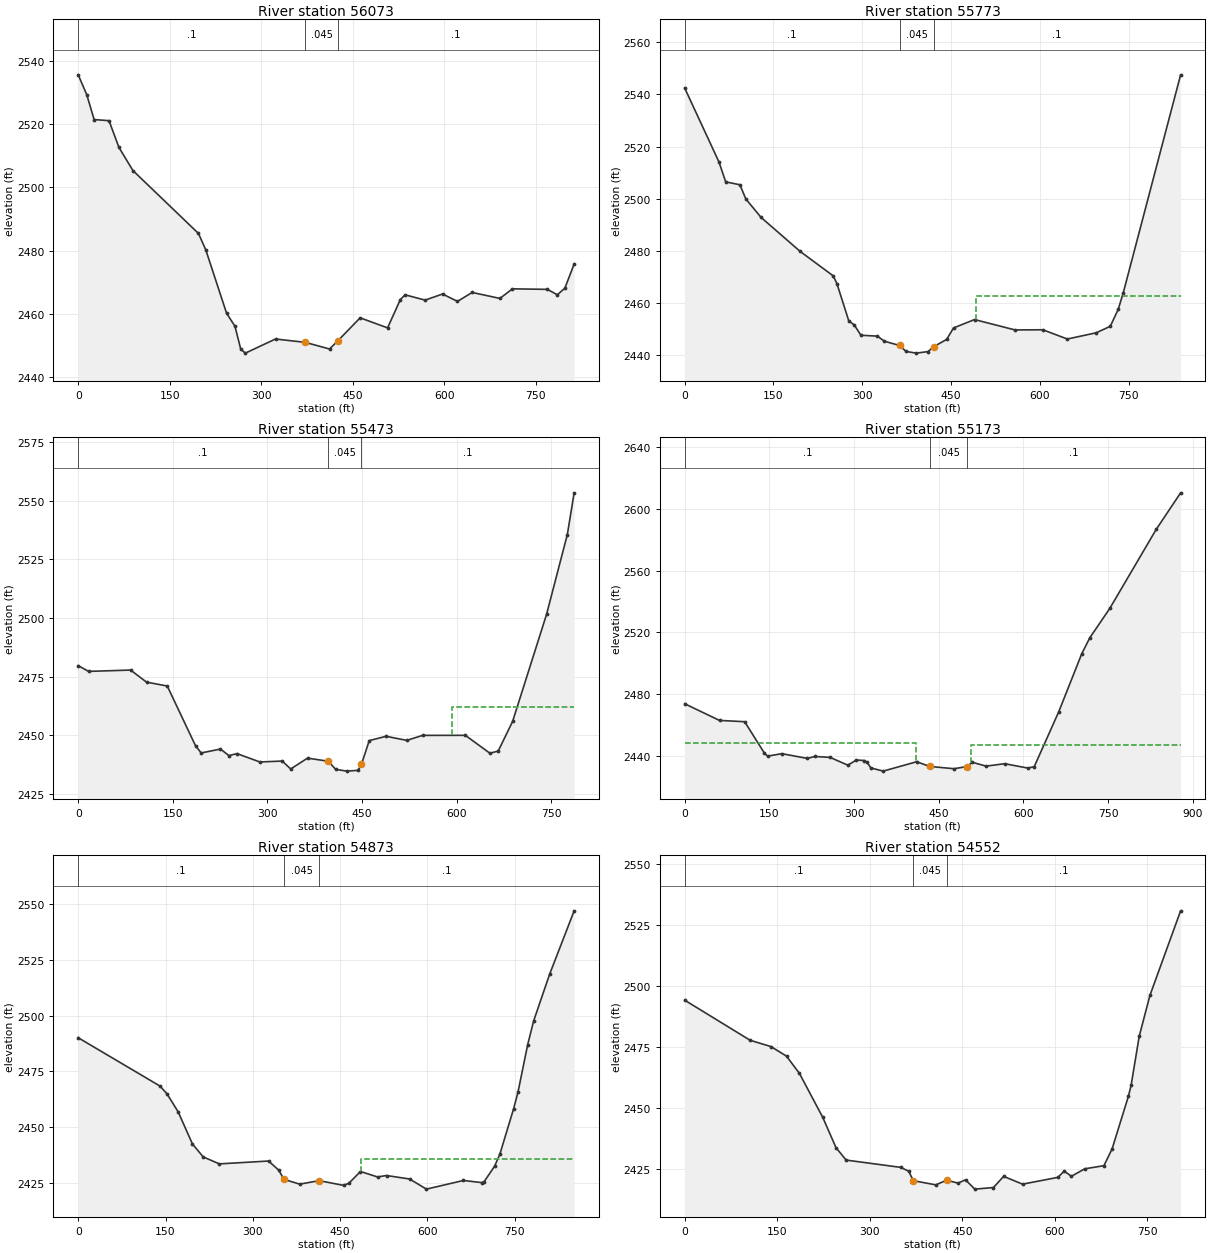
Type RM Length L Ch R = 1 ,56073   ,281.6,300,307.6
XS GIS Cut Line= 3
2397817.14070319666247.334080447     2398215.126      666324.384
     2398613.675      666410.824
#Sta/Elev= 30
       0 2535.71    13.9 2529.47    26.1 2521.53    50.5 2521.18    66.8  2512.7
    89.7 2505.37   197.2 2485.43   209.2 2480.22   243.3 2460.13     257 2456.02
   266.5 2448.77   274.1  2447.5   323.5 2451.98   372.4 2450.91   412.1 2448.81
   425.5 2451.36   462.3 2458.69   507.3  2455.5   528.2 2464.48     536 2465.98
   568.9  2464.3   597.4 2466.24   621.9  2463.9     646 2466.73   691.5 2464.84
     712 2467.88   769.3 2467.71   785.6    2466   797.9 2468.05   813.2 2475.75
#Mann= 3 ,-1 , 0
       0      .1       0   372.4    .045       0   425.5      .1       0
Bank Sta=372.4,425.5
XS Rating Curve= 0 ,0
Exp/Cntr=0.3,0.1

Type RM Length L Ch R = 1 ,55773   ,311.9,300,298.8
XS GIS Cut Line= 3
      2397729.42      666302.964      2398048.23      666553.501
     2398390.057      666818.177
#Sta/Elev= 30
       0 2542.47    57.9 2514.12    69.3 2506.48    93.3 2505.36   103.4 2499.88
   129.1 2492.83     195 2479.81     251  2470.4   257.3 2467.36   277.2 2453.17
   286.6 2451.55   297.7 2447.63   325.6 2447.29   337.4 2445.33   362.9 2443.71
   374.1 2441.41   391.2 2440.77   411.1 2441.36   420.8 2443.27   442.5 2446.01
   454.2 2450.43   489.6 2453.65     558 2449.67     605 2449.73   646.4 2446.18
   695.2 2448.57     719 2451.07   732.4 2457.58     741 2463.98   837.8 2547.54
#Mann= 3 ,-1 , 0
       0      .1       0   362.9    .045       0   420.8      .1       0
#XS Ineff= 2 , 0
                          491.79         2462.66
Permanent Ineff=
       F       F
Bank Sta=362.9,420.8
XS Rating Curve= 0 ,0
Exp/Cntr=0.3,0.1

Type RM Length L Ch R = 1 ,55473   ,276.9,300,309.5
XS GIS Cut Line= 3
     2397572.045       666648.77     2397949.551      666833.302
2398279.10025381666992.897077672
#Sta/Elev= 30
       0 2479.68    16.4 2477.23    83.1 2477.79   108.3 2472.65   141.2 2470.99
     186 2445.54     195 2442.46   225.6 2444.12     239 2441.33   251.8 2442.18
     288 2438.61   323.6    2439   336.9 2435.62   363.6 2440.25   396.5 2438.93
   408.2 2435.47     426 2434.71   443.7 2435.04   449.2 2437.66   461.5 2447.73
   488.2 2449.56   521.1 2447.81     546 2449.95   613.9 2449.97   652.8 2442.34
     666 2443.28   688.8 2455.89   742.7 2501.59   775.6 2535.58   786.4 2553.35
#Mann= 3 ,-1 , 0
       0      .1       0   396.5    .045       0   449.2      .1       0
#XS Ineff= 2 , 0
                           592.2         2461.89
Permanent Ineff=
       F       F
Bank Sta=396.5,449.2
XS Rating Curve= 0 ,0
Exp/Cntr=0.3,0.1

Type RM Length L Ch R = 1 ,55173   ,284.7,300,301.4
XS GIS Cut Line= 3
     2397528.708      666719.161     2397825.718      667098.757
     2398035.192      667435.652
#Sta/Elev= 30
       0  2473.7    61.7  2462.9   106.3 2462.05   140.9 2441.87   146.9 2439.71
   172.1 2441.32   217.5 2438.23   230.5  2439.5   257.7  2438.9     289 2433.86
   304.4 2437.21   317.5 2436.88   323.2 2435.71   329.8 2432.09   351.7 2429.99
     411 2436.08   434.4 2433.02   477.1 2431.56     501 2432.99     509 2435.78
     534 2433.23   567.1 2434.81   607.7 2431.98   619.3 2432.85   662.9 2468.61
   703.5 2506.11   717.6 2516.38   753.2 2535.59   835.4 2586.81   878.7 2610.57
#Mann= 3 ,-1 , 0
       0      .1       0   434.4    .045       0     501      .1       0
#XS Ineff= 2 , 0
          409.57 2448.11  507.14         2446.82
Permanent Ineff=
       F       F
Bank Sta=434.4,501
XS Rating Curve= 0 ,0
Exp/Cntr=0.3,0.1

Type RM Length L Ch R = 1 ,54873   ,347,321,307.6
XS GIS Cut Line= 3
     2397369.804       666792.11      2397542.16      667151.235
2397745.21510637667556.972808514
#Sta/Elev= 30
       0 2490.04   140.7 2468.34   152.7 2464.83   171.7 2456.81   196.3 2442.39
   214.8 2436.59   242.5 2433.47     327 2434.75   344.6 2430.64   353.5 2426.53
   380.5 2424.39   414.2 2425.94   456.1 2423.82   465.1  2424.8     485 2430.05
   514.3 2427.61   529.7 2428.26   569.5 2426.68   598.3 2422.15   661.9 2426.03
   693.2 2425.08   697.6 2425.55   715.5 2432.47   724.5 2437.86   748.2 2458.28
   755.8  2465.9   772.3 2486.98   782.6 2497.67   809.9 2518.49   852.1 2546.96
#Mann= 3 ,-1 , 0
       0      .1       0   353.5    .045       0   414.2      .1       0
#XS Ineff= 2 , 0
                          485.38         2435.49
Permanent Ineff=
       F       F
Bank Sta=353.5,414.2
XS Rating Curve= 0 ,0
Exp/Cntr=0.3,0.1

Type RM Length L Ch R = 1 ,54552   ,273.5,279,277.8
XS GIS Cut Line= 3
      2396970.34      667255.6222397222.61785102667340.737872329
2397711.80772339667563.748765944
#Sta/Elev= 30
       0 2494.33     106  2477.9   139.7 2475.32   165.1 2471.38     186 2464.31
   223.9 2446.25   245.3 2433.87   261.7 2428.78   349.9  2425.8   363.1 2424.23
   370.6 2420.33   407.1 2418.62   424.6 2420.53   443.1 2419.33   455.2 2420.69
   470.3 2416.87   500.5 2417.52     517  2422.1   547.7 2418.91   604.9 2421.69
   615.2 2424.24   626.9 2422.14   648.4 2425.19   679.6 2426.49   692.8 2433.34
   719.2 2454.88   723.6 2459.36   736.8 2479.53   754.1 2496.25   803.9 2530.95
#Mann= 3 ,-1 , 0
       0      .1       0   370.6    .045       0   424.6      .1       0
Bank Sta=370.6,424.6
XS Rating Curve= 0 ,0
Exp/Cntr=0.3,0.1

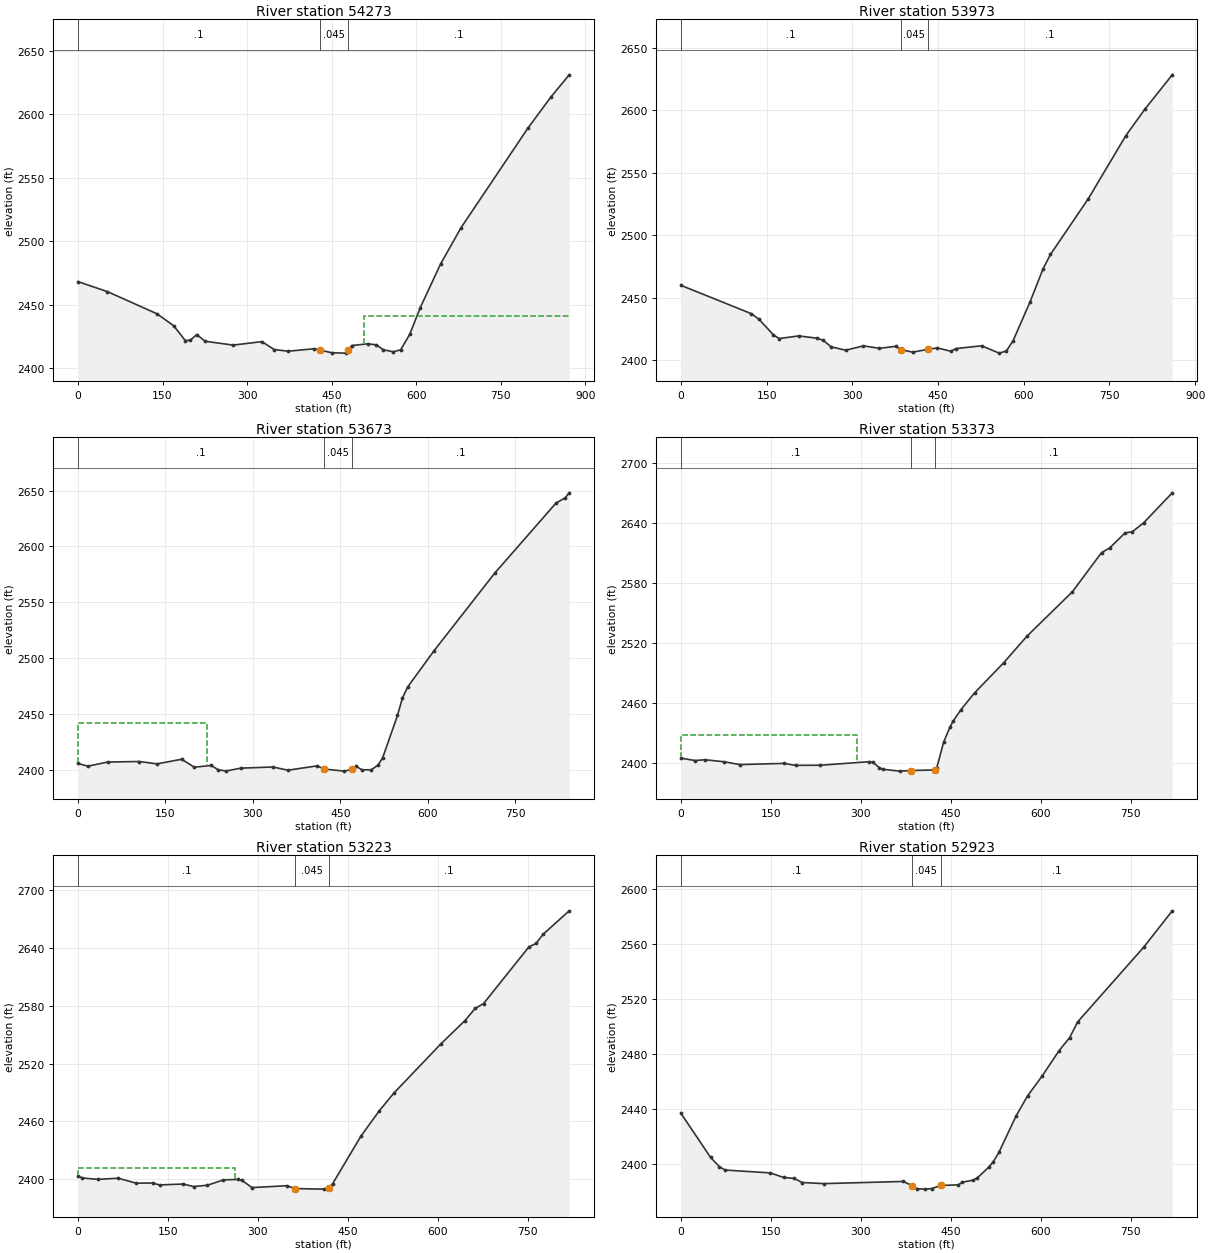
Type RM Length L Ch R = 1 ,54273   ,284.2,300,297.5
XS GIS Cut Line= 3
     2396913.667       667435.26     2397311.552      667669.864
2397670.86459574667866.476574478
#Sta/Elev= 30
       0 2468.16    52.3 2460.29   140.6 2442.75   169.9 2433.37   190.4 2421.75
   199.2 2422.02   210.8 2426.52   225.4 2421.23   275.2 2418.18   326.3 2420.91
   348.1 2414.69   372.7 2413.37   419.2 2415.32   428.5 2414.36   450.4 2412.14
   474.7 2411.86   479.7 2414.01   485.6 2417.83     514  2419.2   529.4 2418.41
   541.6 2414.53   559.3 2412.92   572.4 2414.46   588.7 2426.73   606.9 2447.36
   643.4 2482.18   679.8 2510.78     798  2588.9   839.4 2613.77   871.5 2631.03
#Mann= 3 ,-1 , 0
       0      .1       0   428.5    .045       0   479.7      .1       0
#XS Ineff= 2 , 0
                          508.21         2440.72
Permanent Ineff=
       F       F
Bank Sta=428.5,479.7
XS Rating Curve= 0 ,0
Exp/Cntr=0.3,0.1

Type RM Length L Ch R = 1 ,53973   ,306.7,300,282.2
XS GIS Cut Line= 3
     2396805.205      667536.921     2397079.261      667829.203
     2397418.768      668138.432
#Sta/Elev= 30
       0 2459.89   123.3 2437.18   136.8 2432.59   161.7 2420.27   171.8 2417.32
   206.2 2419.42   237.4 2417.63   248.7 2415.93   262.8  2410.7   288.3 2407.93
   319.4 2411.47   347.3 2409.46   376.5 2411.12   384.5 2408.46   405.4 2406.43
   432.6 2408.67   448.7  2409.8   472.3 2407.12   481.1 2409.27   526.1 2411.49
   556.9 2405.63   569.5  2407.3   581.4 2415.67     611 2446.71   633.7  2473.1
   646.7 2484.62     713 2529.32   778.7 2579.83   812.1 2601.05   859.9 2628.48
#Mann= 3 ,-1 , 0
       0      .1       0   384.5    .045       0   432.6      .1       0
Bank Sta=384.5,432.6
XS Rating Curve= 0 ,0
Exp/Cntr=0.3,0.1

Type RM Length L Ch R = 1 ,53673   ,293.2,300,315.6
XS GIS Cut Line= 3
     2396578.535      667957.418     2396989.062      668098.962
     2397381.505      668212.373
#Sta/Elev= 30
       0 2406.02    17.1 2403.59      51 2407.29   105.2 2407.76   135.6 2405.65
   177.9 2409.77   199.5 2402.65   228.7 2404.25   240.4 2400.39   254.1 2399.28
   279.5 2401.83   334.5 2402.86     360 2399.99   410.6 2403.87   421.8 2401.04
   456.8 2399.16   469.3 2400.66   477.5 2403.44   487.2 2400.24   503.4 2400.42
   515.1 2404.72   522.8 2411.24   548.1 2448.92   556.7 2464.62   565.6 2474.43
   610.9 2506.83     715 2576.21   819.9 2638.71   836.1 2643.61   842.7 2647.96
#Mann= 3 ,-1 , 0
       0      .1       0   421.8    .045       0   469.3      .1       0
#XS Ineff= 2 , 0
           221.6 2442.05
Permanent Ineff=
       F       F
Bank Sta=421.8,469.3
XS Rating Curve= 0 ,0
Exp/Cntr=0.3,0.1

Type RM Length L Ch R = 1 ,53373   ,151.7,150,150.1
XS GIS Cut Line= 3
     2396514.236      668040.742     2396807.038      668327.024
      2397099.84      668613.305
#Sta/Elev= 30
       0 2405.31    23.1 2402.94    39.9  2403.7    71.7 2401.68    98.1 2398.87
   171.6 2400.05   190.9 2398.08   231.9 2398.22     314 2401.76   319.6 2401.32
   330.8 2395.67   336.4 2394.21   364.3 2392.34   383.7 2392.94   423.3 2393.53
   426.2 2395.25   437.9 2421.39   448.2 2436.04   453.8  2442.4   466.5 2453.55
   489.4 2470.44   537.8 2500.42   576.9 2527.13   652.5 2571.37   701.1 2610.45
   714.7 2615.12   740.1 2630.01   752.6 2631.36   771.3  2640.2     819 2670.12
#Mann= 3 ,-1 , 0
       0      .1       0   383.7    .045       0   423.3      .1       0
#XS Ineff= 2 , 0
          292.61 2428.88
Permanent Ineff=
       F       F
Bank Sta=383.7,423.3
XS Rating Curve= 0 ,0
Exp/Cntr=0.3,0.1

Type RM Length L Ch R = 1 ,53223   ,289.2,300,307.1
XS GIS Cut Line= 3
     2396409.371      668147.996     2396702.173      668434.277
     2396994.975      668720.559
#Sta/Elev= 30
       0 2403.45     7.5 2401.49    32.7 2400.03    67.1 2401.25      97  2396.1
   124.3 2396.29     136 2394.27   175.3 2395.24     193  2392.6   215.8 2393.96
   242.5 2399.52   266.1 2399.97   273.1 2399.08   290.2 2391.56   348.1 2393.46
   362.3 2390.49   410.3 2389.94   418.8 2391.29   424.5 2395.48   471.8 2444.86
   501.9 2470.68   526.3 2489.13   604.9 2540.28     645 2564.34   662.1 2577.02
   676.2 2582.09   751.5 2640.59   763.9 2644.46   775.2 2653.71     819 2678.15
#Mann= 3 ,-1 , 0
       0      .1       0   362.3    .045       0   418.8      .1       0
#XS Ineff= 2 , 0
          262.54  2411.4
Permanent Ineff=
       F       F
Bank Sta=362.3,418.8
XS Rating Curve= 0 ,0
Exp/Cntr=0.3,0.1

Type RM Length L Ch R = 1 ,52923   ,302.7,300,296.3
XS GIS Cut Line= 3
     2396291.009      668248.866     2396468.882      668617.851
     2396638.563      668990.519
#Sta/Elev= 30
       0 2436.83    49.3 2404.91    63.9 2398.22    73.3 2395.75   148.8 2393.66
     171 2390.35   188.7 2389.66     202 2386.69   237.6 2385.88   370.8 2387.45
   384.8 2384.45     393 2382.14   406.3 2381.88   417.9 2382.22   432.7 2384.53
   462.4    2385   469.2 2386.94   487.3 2388.41   494.3 2390.11   512.9  2397.7
   520.6 2401.74     530 2408.53   558.9 2435.19   577.9 2449.63   602.1 2463.96
   630.5 2482.49   648.1 2491.93   661.3 2503.28   771.2 2557.38   819.1 2583.94
#Mann= 3 ,-1 , 0
       0      .1       0   384.8    .045       0   432.7      .1       0
Bank Sta=384.8,432.7
XS Rating Curve= 0 ,0
Exp/Cntr=0.3,0.1

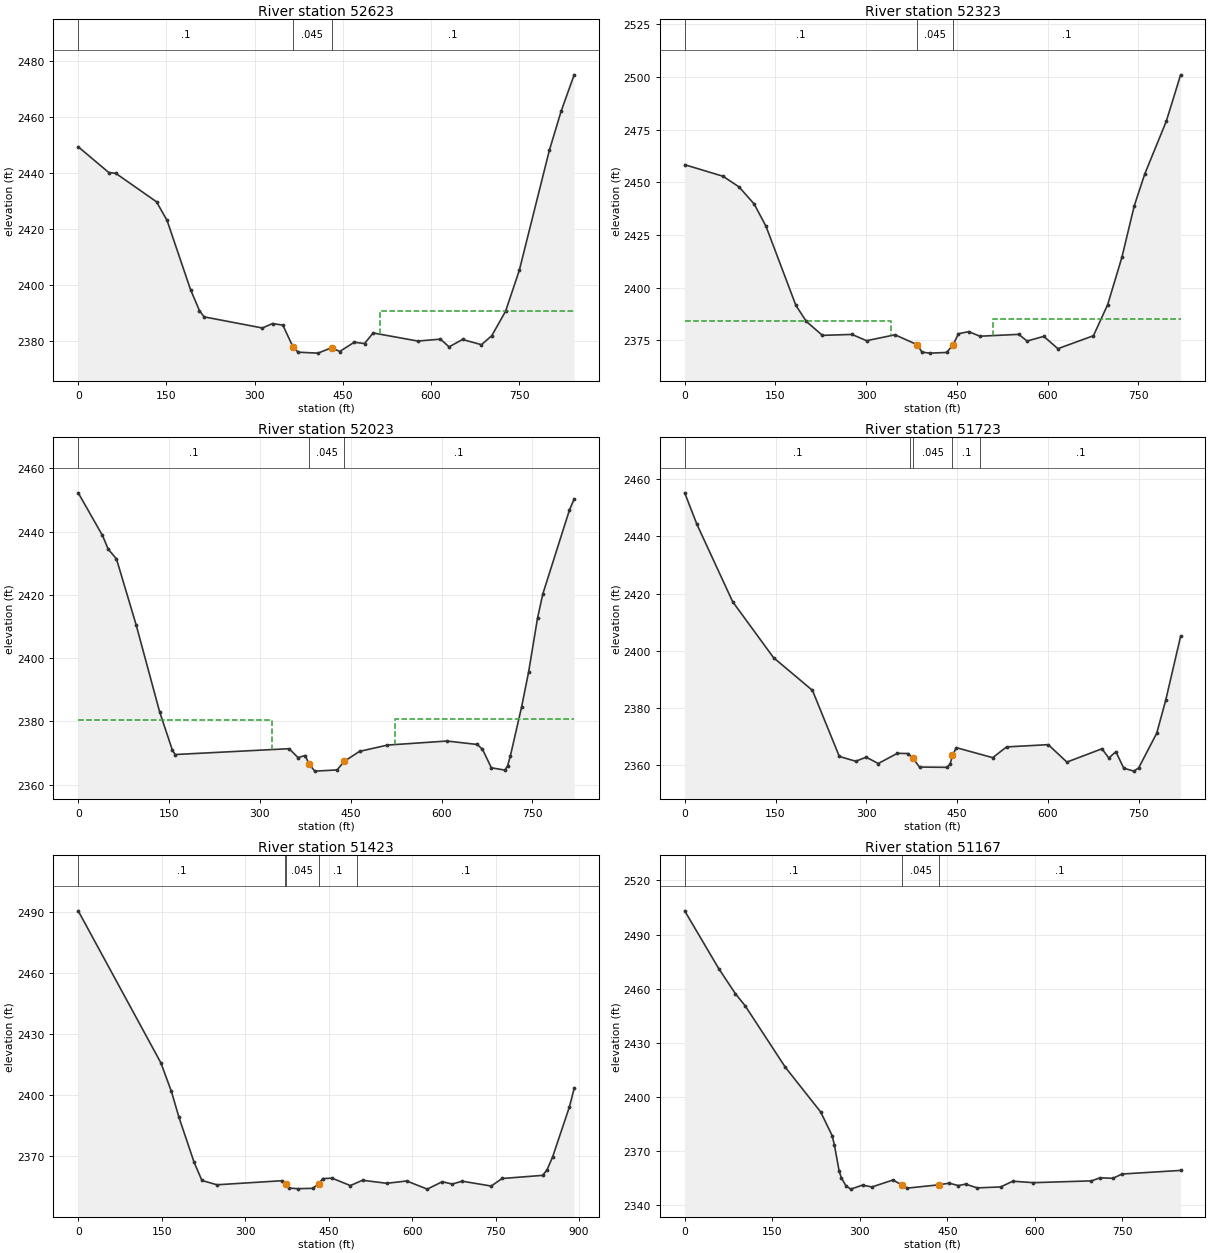
Type RM Length L Ch R = 1 ,52623   ,322.6,300,283.7
XS GIS Cut Line= 3
     2396003.055      668360.572     2396187.999      668718.739
 2396409.9222825669099.365332265
#Sta/Elev= 30
       0 2449.41    52.1 2440.21    63.8 2439.95   133.2 2429.77   151.2  2423.1
   191.1 2398.41   206.3  2390.9   214.2 2388.69   313.2 2384.72   330.6  2386.3
   348.1 2385.73   365.5 2377.91   374.2 2376.07   407.9 2375.74   431.1 2377.67
   444.9 2376.32   469.6 2379.63   487.1 2379.16   501.7 2382.94   577.8 2380.05
   616.3 2380.74   630.9 2377.98   653.8 2380.61     686 2378.75   703.6 2381.97
     727 2390.68   750.4 2405.31   801.5 2448.13   821.5 2462.08   843.7  2475.1
#Mann= 3 ,-1 , 0
       0      .1       0   365.5    .045       0   431.1      .1       0
#XS Ineff= 2 , 0
                          513.13         2390.85
Permanent Ineff=
       F       F
Bank Sta=365.5,431.1
XS Rating Curve= 0 ,0
Exp/Cntr=0.3,0.1

Type RM Length L Ch R = 1 ,52323   ,298.2,300,300.3
XS GIS Cut Line= 3
     2395677.799      668794.286     2396047.169      668973.247
     2396403.891      669174.005
#Sta/Elev= 30
       0 2458.32    63.3 2452.85    89.9 2447.77   114.9 2439.66   134.4 2429.11
   183.8 2391.56   201.1 2383.92   227.7  2377.3   276.6 2377.75   300.6 2374.77
   347.7 2377.57   384.4 2372.87   392.2 2369.33   405.4 2368.87   432.9 2369.18
   443.6 2372.73   452.5 2378.07   469.6 2379.08     488  2376.9   552.2 2377.78
     566 2374.61   593.6 2376.83   616.9 2370.98   675.7 2377.13   699.2 2391.89
   722.7 2414.32   743.2 2438.85   760.8 2454.13   796.1 2478.93   819.8 2500.99
#Mann= 3 ,-1 , 0
       0      .1       0   384.4    .045       0   443.6      .1       0
#XS Ineff= 2 , 0
          340.57    2384  508.91         2384.93
Permanent Ineff=
       F       F
Bank Sta=384.4,443.6
XS Rating Curve= 0 ,0
Exp/Cntr=0.3,0.1

Type RM Length L Ch R = 1 ,52023   ,296.7,300,303.3
XS GIS Cut Line= 3
     2395543.987      669030.041     2395899.017      669234.109
     2396254.047      669438.178
#Sta/Elev= 30
       0 2452.23    40.1 2438.75    49.5 2434.45    63.2 2431.34    95.5 2410.63
   134.5 2383.02   155.4    2371     160 2369.55   348.3  2371.4     363 2368.59
   374.7 2369.24   381.5 2366.49   390.7 2364.31   427.5 2364.69   439.2 2367.38
   464.6 2370.55   510.7 2372.54   609.1 2373.82   658.9 2372.73   667.6 2371.21
   682.3 2365.36   704.5 2364.64   709.1 2365.99   713.7 2369.15   732.2 2384.57
   743.9 2395.75   758.5 2412.62   767.3 2420.31   811.2 2446.78     819 2450.26
#Mann= 3 ,-1 , 0
       0      .1       0   381.5    .045       0   439.2      .1       0
#XS Ineff= 2 , 0
           319.3 2380.39  523.61         2380.82
Permanent Ineff=
       F       F
Bank Sta=381.5,439.2
XS Rating Curve= 0 ,0
Exp/Cntr=0.3,0.1

Type RM Length L Ch R = 1 ,51723   ,304.7,300,296.2
XS GIS Cut Line= 3
     2395408.047      669247.026     2395739.395      669487.647
     2396070.743      669728.269
#Sta/Elev= 30
       0 2455.18    20.2 2444.19    79.2 2417.16   146.7 2397.61     211 2386.17
   255.4 2363.09   282.5 2361.41   299.7 2362.84   319.7 2360.62   351.2 2364.18
   368.4 2364.11     377 2362.43   387.8 2359.38   433.4 2359.28   438.4  2360.5
   442.2 2363.44   448.6 2366.15   508.7 2362.67   531.6 2366.42   600.4 2367.21
   631.2 2361.12   689.1 2365.77   700.4 2362.55   712.1 2364.75   725.1 2358.99
   741.8 2357.96   749.8 2359.11   779.5 2371.19   794.3 2382.65     819 2405.09
#Mann= 5 ,-1 , 0
       0      .1       0  371.81      .1       0     377    .045       0
   442.2      .1       0  487.94      .1       0
Bank Sta=377,442.2
XS Rating Curve= 0 ,0
Exp/Cntr=0.3,0.1

Type RM Length L Ch R = 1 ,51423   ,270.3,256.8,245.3
XS GIS Cut Line= 3
     2395203.035      669537.685     2395563.073      669730.225
2395994.42604168669947.284650202
#Sta/Elev= 30
       0 2490.41   148.5 2415.91   167.5 2401.87   181.1 2389.13   208.3 2367.11
   222.3 2358.25   249.2 2356.12   367.1 2358.13   373.1 2356.47     379 2354.51
   394.3 2354.21   421.4 2354.38   432.4 2356.65   439.3 2359.15   456.2 2359.36
     489 2355.73   510.9 2358.34   554.5 2356.85   590.3 2357.98   627.3 2353.99
   654.2 2357.63   672.1 2356.47     690 2357.88   742.2  2355.5   761.7  2359.2
   834.5 2360.73   842.3 2363.35   852.4 2369.73   882.6 2394.22   891.2 2403.38
#Mann= 5 ,-1 , 0
       0      .1       0   370.8      .1       0   373.1    .045       0
   432.4      .1       0  500.18      .1       0
Bank Sta=373.1,432.4
XS Rating Curve= 0 ,0
Exp/Cntr=0.3,0.1

Type RM Length L Ch R = 1 ,51167   ,201.3,193.2,184.1
XS GIS Cut Line= 3
     2395065.902      669917.151 2395198.1876918669947.476282502
     2395910.357      669998.633
#Sta/Elev= 30
       0 2503.14    58.3 2471.12      87 2457.14   103.5 2450.53   172.4 2416.38
     233 2391.57   252.6 2378.49   256.6 2373.12   264.6 2358.89   268.6 2354.86
   276.6 2350.51   284.7 2348.76   304.7 2350.99   320.7 2349.96   356.8 2353.81
   372.9 2350.96   380.9 2349.31     435 2351.14   453.1 2352.06   469.1 2350.72
   481.2 2351.55   501.2 2349.45   541.3 2349.98   562.2 2353.15   597.5 2352.34
   696.9 2353.35   711.9 2355.04   733.8 2354.77   749.3 2357.14   849.7 2359.14
#Mann= 3 ,-1 , 0
       0      .1       0   372.9    .045       0     435      .1       0
Bank Sta=372.9,435
XS Rating Curve= 0 ,0
Exp/Cntr=0.3,0.1

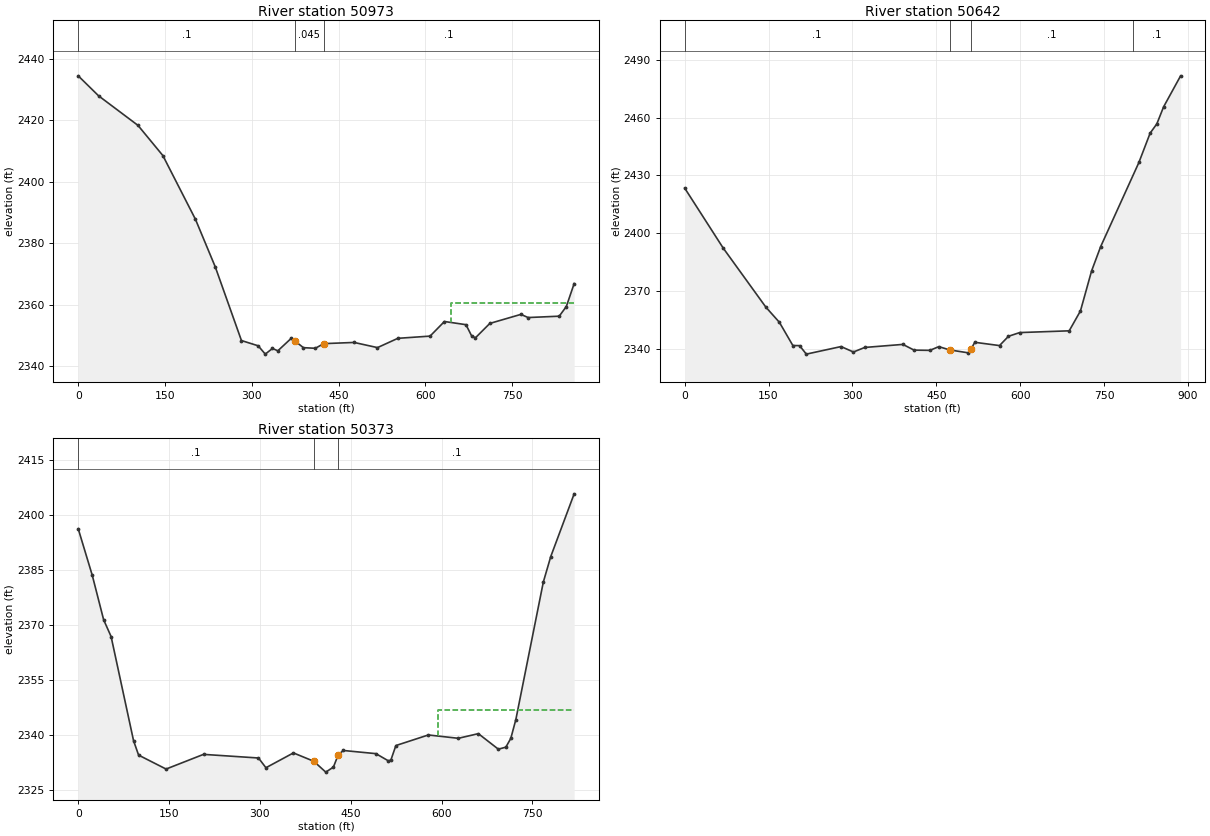
Type RM Length L Ch R = 1 ,50973   ,328.2,331.3,336.3
XS GIS Cut Line= 3
     2395084.566      670249.455     2395474.552      670154.666
     2395915.758      670040.512
#Sta/Elev= 30
       0  2434.5    35.2    2428   103.3 2418.38   146.3 2408.56   202.6 2387.84
   236.9 2372.34   282.1  2348.4     311 2346.69   323.3 2343.98   335.7 2345.83
     345 2345.06   368.2 2349.13   374.7 2348.23   389.2 2346.08   409.8 2345.88
   424.3 2347.39   476.8 2347.78   517.2  2346.1   552.4 2349.12   608.1 2349.84
   632.9 2354.59   670.1 2353.56   680.3 2349.78   686.6 2349.31   711.4 2353.97
   765.1 2356.91   777.5 2355.88   831.3 2356.32   843.6 2359.47   857.1 2366.93
#Mann= 3 ,-1 , 0
       0      .1       0   374.7    .045       0   424.3      .1       0
#XS Ineff= 2 , 0
                          644.72          2360.5
Permanent Ineff=
       F       F
Bank Sta=374.7,424.3
XS Rating Curve= 0 ,0
Exp/Cntr=0.3,0.1

Type RM Length L Ch R = 1 ,50642   ,266,268.7,272
XS GIS Cut Line= 3
2395154.10886986670380.5797629962395638.02203531670423.056858749
2396037.06403531670462.358858749
#Sta/Elev= 30
       0 2423.45    68.9 2392.34   145.2 2361.72   169.3  2353.9   193.4 2341.86
   205.4 2341.79   217.5 2337.39   279.6 2341.31   301.7 2338.49   321.9 2340.85
   390.1 2342.43   410.2 2339.46   438.3 2339.34   454.4 2341.27   473.5 2339.59
   506.6 2338.08   511.9 2340.02   518.7 2343.52   562.9 2341.82   578.9 2346.63
     599 2348.56   687.5 2349.47   707.6 2359.77   727.5 2380.49   743.7 2393.08
   812.1 2436.72   832.2 2451.93   844.2 2456.73   856.3 2465.57   886.7 2481.63
#Mann= 4 ,-1 , 0
       0      .1       0   473.5    .045       0   511.9      .1       0
  801.34      .1       0
Bank Sta=473.5,511.9
XS Rating Curve= 0 ,0
Exp/Cntr=0.3,0.1

Type RM Length L Ch R = 1 ,50373   ,304.5,300,295
XS GIS Cut Line= 3
      2395194.05      670587.492      2395591.22      670687.233
     2395988.116      670788.047
#Sta/Elev= 30
       0 2396.33    23.2 2383.62      42 2371.46    54.3 2366.89    91.4 2338.43
    99.7  2334.5   145.1 2330.69   206.9  2334.7   297.7 2333.71     310 2331.05
   355.4  2335.1   389.1 2332.81   408.8 2329.85   421.4 2331.22   429.6 2334.66
   437.9 2335.76   491.6  2334.9   512.2 2332.93   516.3 2333.13   524.6 2337.11
   578.2    2340   627.7 2339.09   660.8 2340.36   693.8 2336.12   706.2 2336.67
   714.4 2339.07   722.7  2344.2   768.1 2381.78   780.4 2388.75     819 2405.87
#Mann= 3 ,-1 , 0
       0      .1       0   389.1    .045       0   429.6      .1       0
#XS Ineff= 2 , 0
                          594.46         2346.89
Permanent Ineff=
       F       F
Bank Sta=389.1,429.6
XS Rating Curve= 0 ,0
Exp/Cntr=0.3,0.1