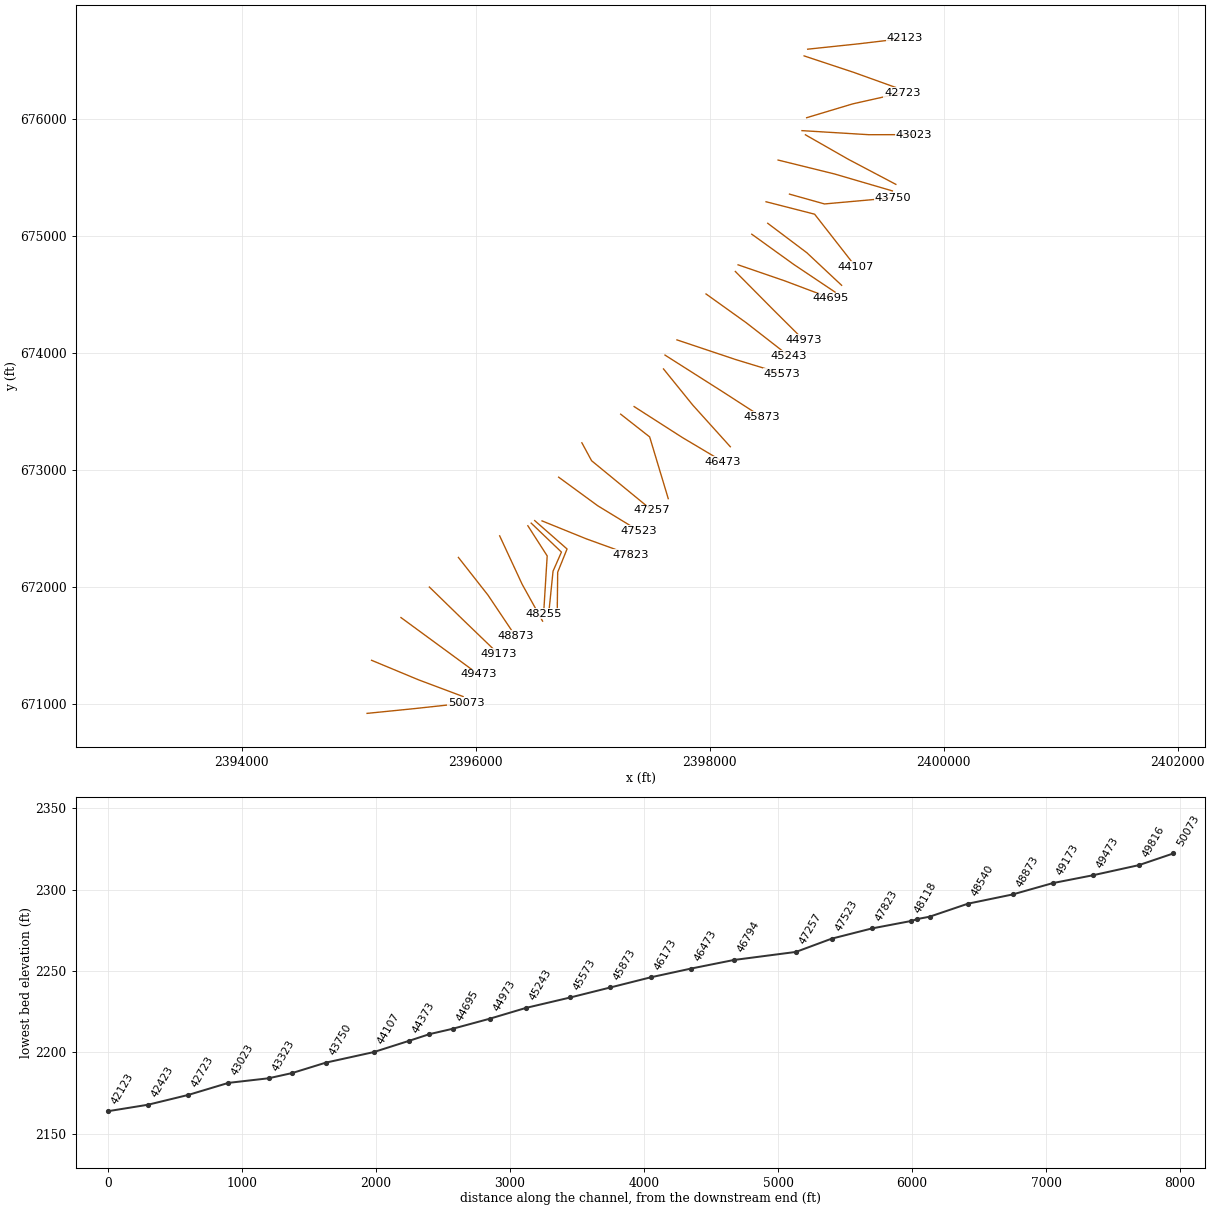
HEC-RAS study SENECACK.prj: SENECACK

--- SENECACK.g03 (geometry) --- (continued)

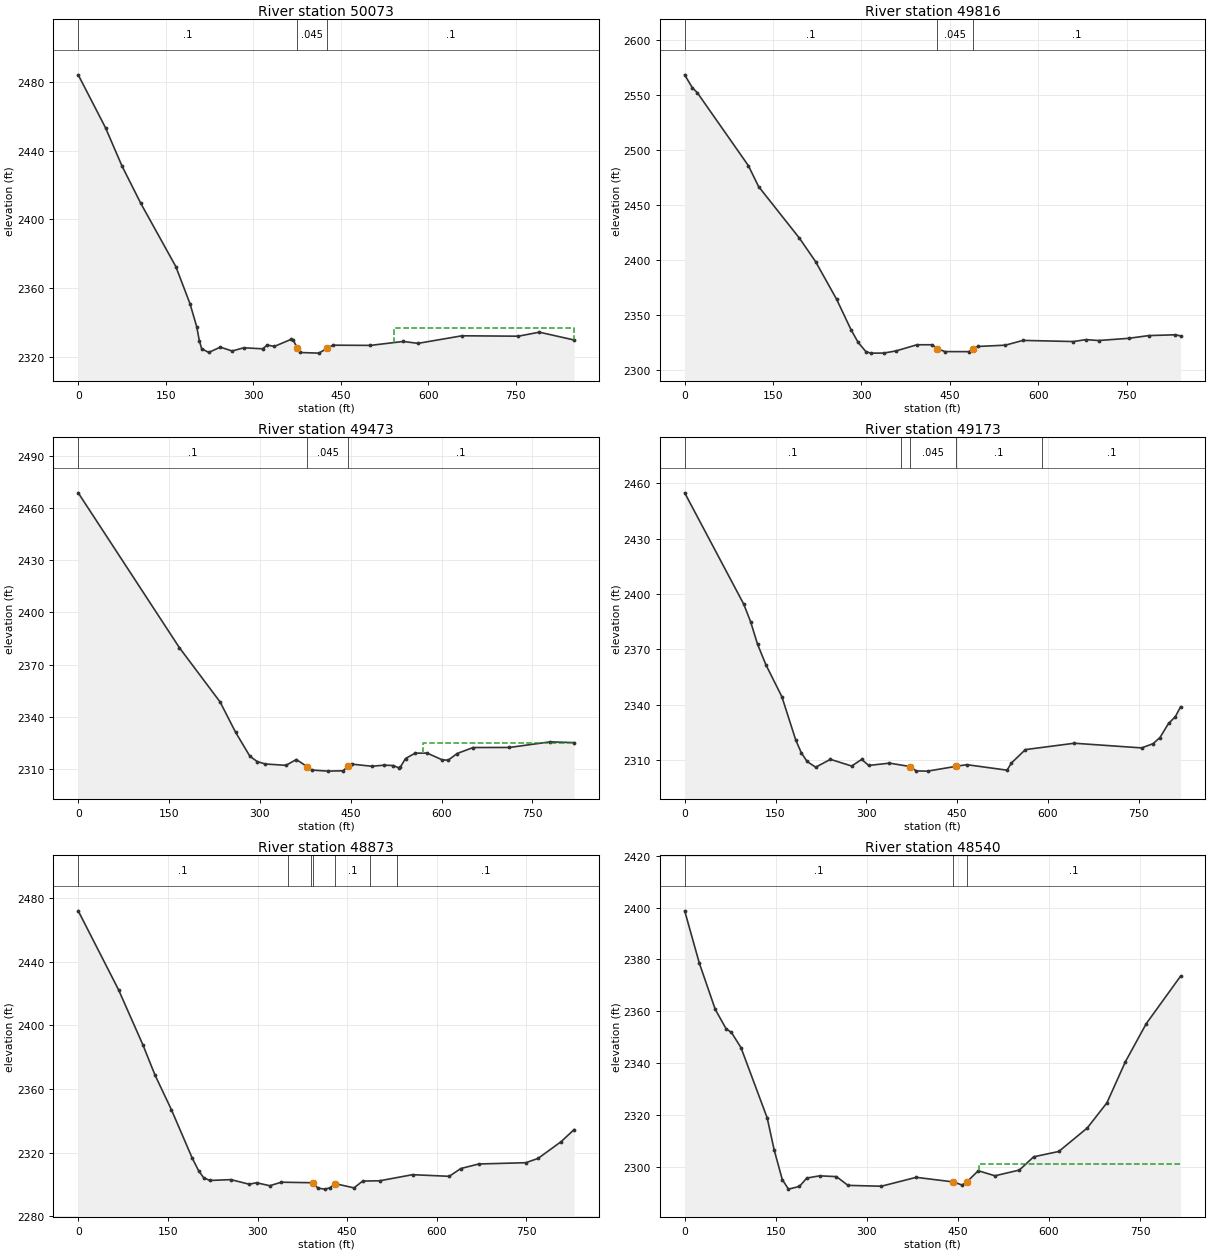
Type RM Length L Ch R = 1 ,50073   ,268.4,257.9,244.2
XS GIS Cut Line= 3
2395072.15048128670918.206890431     2395473.103      670958.537
     2395918.044        671006.7
#Sta/Elev= 30
       0 2484.04    46.8 2453.28      75 2431.09   107.1 2409.45   167.4 2372.57
   191.6 2351.07   203.3 2337.53   207.7 2329.45   211.7 2324.84   223.7 2322.65
   243.8 2325.72   263.9 2323.48     284 2325.35   316.2 2324.75   324.2 2326.96
   336.3 2326.13   364.6 2330.18   368.7 2329.82   375.92325.141   380.5 2322.61
   412.7 2322.24   426.6 2324.95   436.8 2326.86   501.2 2326.74   557.5 2329.03
   582.7 2327.92   658.1 2332.32   754.7 2332.09   790.9 2334.42   850.5 2329.86
#Mann= 3 ,-1 , 0
       0      .1       0   375.9    .045       0   426.6      .1       0
#XS Ineff= 2 , 0
                          541.07          2336.7
Permanent Ineff=
       F       F
Bank Sta=375.9,426.6
XS Rating Curve= 0 ,0
Exp/Cntr=0.3,0.1

Type RM Length L Ch R = 1 ,49816   ,349,342.1,330.8
XS GIS Cut Line= 3
2395110.94078317671372.2365461522395510.49582339671205.901548928
2395893.14782339671062.141548928
#Sta/Elev= 30
       0 2568.52    12.8 2556.94    21.5 2552.18     108 2485.87   125.4 2466.78
   194.8  2419.7   222.1 2398.43   257.9 2364.02   282.3 2336.37   294.4 2324.77
   307.4  2316.5   315.7 2315.04   337.7 2315.08   358.8 2317.07   394.1 2322.66
   419.8 2322.67   428.7 2319.21   441.5 2316.44   481.9 2316.38   489.7 2318.51
   497.4 2321.11   544.2 2322.28   574.1 2326.64   659.5 2325.59   680.9 2327.33
   702.3 2326.53   753.5 2328.53   787.7 2331.03   832.9 2331.74   841.6 2330.71
#Mann= 3 ,-1 , 0
       0      .1       0   428.7    .045       0   489.7      .1       0
Bank Sta=428.7,489.7
XS Rating Curve= 0 ,0
Exp/Cntr=0.3,0.1

Type RM Length L Ch R = 1 ,49473   ,304.4,300,295
XS GIS Cut Line= 3
     2395362.096      671737.687     2395692.304      671495.503
     2396022.511      671253.319
#Sta/Elev= 30
       0 2468.63   167.1 2379.71   234.3 2348.55     260 2331.08   283.6 2317.34
   295.6 2314.34   308.7 2312.94   343.1 2312.16   360.2 2315.49   377.8 2311.48
   385.9 2309.45   412.5 2308.83   437.3 2309.03     446 2311.81   451.7 2312.86
   484.9 2311.62   505.2 2312.26   520.4 2312.05     529 2310.77   531.9 2311.12
   540.5 2316.06   556.4 2319.15   576.2 2319.19     601 2315.33   610.9 2315.11
   625.8 2318.95   652.1 2322.38   712.2 2322.42   779.6 2325.65     819 2325.19
#Mann= 3 ,-1 , 0
       0      .1       0   377.8    .045       0     446      .1       0
#XS Ineff= 2 , 0
                          569.13         2324.94
Permanent Ineff=
       F       F
Bank Sta=377.8,446
XS Rating Curve= 0 ,0
Exp/Cntr=0.3,0.1

Type RM Length L Ch R = 1 ,49173   ,302.8,300,296.6
XS GIS Cut Line= 3
     2395604.905      671998.858     2395898.245      671713.113
     2396193.093      671428.945
#Sta/Elev= 30
       0 2454.88    97.5 2394.55   108.9    2385   120.3 2372.82   134.2 2361.63
   160.5 2344.35   183.4  2320.9   192.4 2314.07   202.1 2309.26   216.3 2306.14
   240.7  2310.4   275.7 2306.78   292.3 2310.36   303.9 2307.08   338.2 2308.34
   372.6 2306.48   382.3 2304.13   401.2 2304.01   447.3 2306.56   465.8 2307.51
   532.4 2304.53   539.5 2308.37   562.6 2315.68   643.5 2319.13   754.6  2316.6
   773.5  2318.9   784.9 2322.22   799.1 2329.89   810.2 2333.47     819 2338.94
#Mann= 5 ,-1 , 0
       0      .1       0  356.63      .1       0   372.6    .045       0
   447.3      .1       0  590.71      .1       0
Bank Sta=372.6,447.3
XS Rating Curve= 0 ,0
Exp/Cntr=0.3,0.1

Type RM Length L Ch R = 1 ,48873   ,335.9,333.5,327.7
XS GIS Cut Line= 3
2395852.98106384672252.019063835     2396105.959      671929.416
     2396339.747      671580.705
#Sta/Elev= 30
       0 2471.83    67.6 2422.16   108.2 2387.68   128.5 2368.67   155.9 2346.95
   190.8 2316.48   201.5 2308.58   209.8 2304.26     220 2302.47   255.6    2303
   286.1 2300.11   298.4 2301.05   320.5 2299.17   339.9 2301.38   392.8 2301.04
   400.9 2297.68   412.4 2297.03     421 2297.82   429.6 2300.51   461.4 2297.82
     476 2302.09   504.5 2302.28   559.4  2306.1   620.9 2305.08   640.1 2309.96
     670 2312.81     749 2313.63   769.4 2316.32   807.9 2326.82   829.8 2334.48
#Mann= 7 ,-1 , 0
       0      .1       0  350.94      .1       0  389.45      .1       0
   392.8    .045       0   429.6      .1       0  487.81      .1       0
  533.37      .1       0
Bank Sta=392.8,429.6
XS Rating Curve= 0 ,0
Exp/Cntr=0.3,0.1

Type RM Length L Ch R = 1 ,48540   ,303.8,285.3,273.8
XS GIS Cut Line= 3
     2396205.535       672436.732396397.62257448672022.754106386
 2396572.2253192671707.275170241
#Sta/Elev= 30
       0 2398.74    24.1 2378.58    50.4 2360.69    68.2 2353.25      77 2351.81
    92.7 2345.99   135.9 2318.86   147.5 2306.42   160.8 2295.02     171 2291.36
     189  2292.4   201.1 2295.63   222.2 2296.49     250 2296.19     269 2292.81
   323.9 2292.48   381.3 2295.91   442.1 2294.15   457.1 2292.94   465.4  2294.3
   483.6 2298.45   511.1 2296.51   551.3 2298.72   574.8 2303.83   616.2 2305.89
   663.1 2314.95   695.5 2324.66   725.9 2340.49   760.2 2355.17   816.9 2373.56
#Mann= 3 ,-1 , 0
       0      .1       0   442.1    .045       0   465.4      .1       0
#XS Ineff= 2 , 0
                          485.36         2300.91
Permanent Ineff=
       F       F
Bank Sta=442.1,465.4
XS Rating Curve= 0 ,0
Exp/Cntr=0.3,0.1

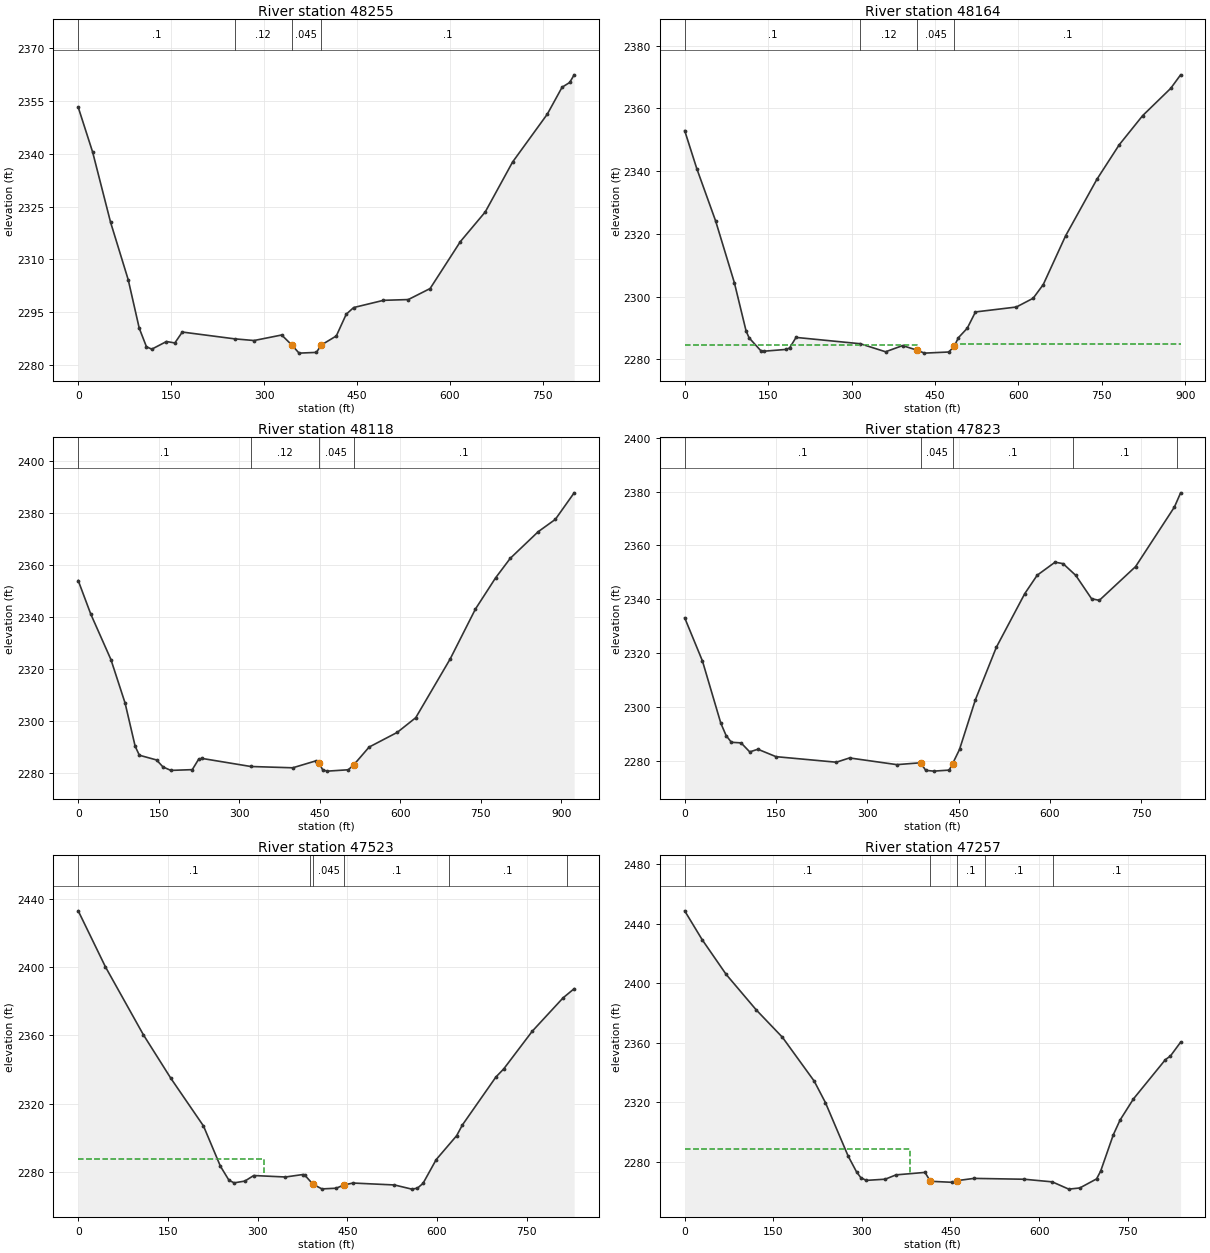
Type RM Length L Ch R = 1 ,48255   ,101.3,91,76.4
XS GIS Cut Line= 3
2396446.57819787672522.8570896112396611.73860502672265.217198074
2396581.33349826671771.718926739
#Sta/Elev= 30
       0 2353.25    23.3 2340.49    52.2 2320.58    80.7 2304.24    98.5 2290.47
   110.1 2285.21   118.7  2284.5   142.5 2286.68     156 2286.27     168 2289.37
   252.3 2287.44   283.8 2286.96   328.4 2288.53   344.4 2285.76   356.5 2283.38
   384.5 2283.59   392.2 2285.67   416.6 2288.26   432.6 2294.43   444.6 2296.33
   492.7 2298.38   532.8  2298.6     568 2301.73   616.9 2315.08     657 2323.49
   701.1 2337.67   757.2 2351.29     781 2358.92   793.3 2360.28   800.5 2362.45
#Mann= 4 ,-1 , 0
       0      .1       0   252.3     .12       0   344.4    .045       0
   392.2      .1       0
Bank Sta=344.4,392.2
XS Rating Curve= 0 ,0
Exp/Cntr(USF)=0,0
Exp/Cntr=0.5,0.3

Type RM Length L Ch R = 1 ,48164   ,42.8,46,45.1
XS GIS Cut Line= 4
 2396475.0437877672545.424817921 2396733.5142091672297.706184038
2396661.85119144672134.5378766422396625.84624293671781.113485486
#Sta/Elev= 30
       0  2352.9    21.7 2340.81    55.7 2324.05    89.3 2304.42   110.4    2289
   115.9  2286.8   136.6 2282.77   142.4 2282.56   182.9 2283.14   188.7 2283.63
   200.2 2286.96   315.8 2284.94   361.1 2282.38   391.7 2284.35   417.9 2282.88
     431 2281.95   474.7 2282.31   484.3 2284.07   492.1 2286.88     508  2289.9
   522.7 2295.08   596.2 2296.65   626.4 2299.44   644.6 2303.82   684.6  2319.3
   740.9 2337.34   781.1 2348.37   823.3 2357.68   873.6 2366.35   891.5 2370.68
#Mann= 4 ,-1 , 0
       0      .1       0   315.8     .12       0   417.9    .045       0
   484.3      .1       0
#XS Ineff= 2 , 0
           417.9  2284.5   484.3            2285
Permanent Ineff=
       F       F
Bank Sta=417.9,484.3
XS Rating Curve= 0 ,0
Exp/Cntr=0.5,0.3

Type RM Length L Ch R = 1 ,48118   ,256.3,294.2,345.1
XS GIS Cut Line= 4
2396505.12289188672567.0516555182396781.56317308672324.375113506
2396701.46982775672125.3757453752396697.69366046671783.864627589
#Sta/Elev= 30
       0 2353.99    23.4 2341.09    60.9 2323.65    87.3 2306.93   106.1 2290.31
   113.9 2286.87   145.9 2285.05   157.9 2282.38   172.5 2281.04   212.5 2281.33
   224.6 2285.42   230.6 2285.64   321.5 2282.54   399.6 2282.04   442.7  2284.7
     448 2284.04   455.7 2281.19   464.3 2280.76   503.1 2281.28   513.3 2283.17
   541.9    2290   594.3 2295.64   628.8 2301.29   692.9 2323.85   739.9    2343
   777.4 2354.98   804.9 2362.53   856.9 2372.75   888.9  2377.5   923.9 2387.69
#Mann= 4 ,-1 , 0
       0      .1       0   321.5     .12       0     448    .045       0
   513.3      .1       0
Bank Sta=448,513.3
XS Rating Curve= 0 ,0
Exp/Cntr(USF)=0,0
Exp/Cntr=0.5,0.3

Type RM Length L Ch R = 1 ,47823   ,305.2,300,293.8
XS GIS Cut Line= 3
2396567.66459085672564.551732312     2396945.645       672411.25
2397328.34518447672272.645737863
#Sta/Elev= 30
       0 2333.12    29.2 2317.07    59.4 2293.95    68.1 2289.37    76.7 2286.88
    92.7 2286.65   106.9  2283.3   120.3 2284.29   150.1 2281.53   249.2 2279.47
   270.9 2281.06   348.6 2278.57   387.6 2279.26   396.1 2276.45   409.1 2276.16
   434.6 2276.54   440.3 2278.95   451.6 2284.22   477.7 2302.69   512.1 2322.16
   558.9 2342.12   579.2 2348.92   608.6 2353.77   621.8 2353.22   642.6 2348.87
   668.6 2340.19   681.3 2339.59   740.9 2352.13   804.7 2374.25   814.9 2379.53
#Mann= 5 ,-1 , 0
       0      .1       0   387.6    .045       0   440.3      .1       0
  638.23      .1       0  809.24      .1       0
Bank Sta=387.6,440.3
XS Rating Curve= 0 ,0
Exp/Cntr=0.3,0.1

Type RM Length L Ch R = 1 ,47523   ,267.4,266.2,262.6
XS GIS Cut Line= 3
2396709.90859085672938.404628293     2397044.629      672693.418
     2397398.504      672477.604
#Sta/Elev= 30
       0 2432.96    45.6 2400.08     109 2360.32   154.9 2334.82   209.5 2306.87
   237.8 2283.29   252.1 2275.07   260.7 2273.56   278.6 2274.59   293.5 2277.85
   346.6 2276.99   375.2 2278.41   378.4 2278.26   392.6 2272.73   407.5 2270.01
   431.3 2270.41   444.4 2272.32   459.4 2273.45   528.8 2272.32   557.8 2269.88
   567.2 2270.43   576.6 2273.26   598.6 2287.18   632.8 2301.19   642.4 2307.47
   698.4 2335.55   711.6 2340.36   759.3 2362.43   810.8 2381.96   829.3 2387.33
#Mann= 6 ,-1 , 0
       0      .1       0  386.92      .1       0   392.6    .045       0
   444.4      .1       0  619.57      .1       0  816.95      .1       0
#XS Ineff= 2 , 0
          310.06 2287.61
Permanent Ineff=
       F       F
Bank Sta=392.6,444.4
XS Rating Curve= 0 ,0
Exp/Cntr=0.3,0.1

Type RM Length L Ch R = 1 ,47257   ,465.8,463.5,444.9
XS GIS Cut Line= 3
2396908.14659362673232.7201766092396991.17316504673079.418901532
2397505.03085298672656.876486826
#Sta/Elev= 30
       0 2448.58    29.4 2429.32    70.3 2405.86   121.3    2382   165.6 2363.64
   219.3 2334.25   238.2  2319.9   276.7 2283.99   290.9 2273.38   298.1 2269.48
   307.4 2267.62   339.5 2268.42   357.8 2271.32   406.8 2272.98     416 2267.01
   452.3 2266.34   461.4 2267.46   489.7 2268.96   575.1 2268.38   622.3 2266.63
   650.2 2261.75   668.9 2262.53   697.3 2268.61   704.2 2273.82   725.7 2298.29
   737.1 2308.13   759.8 2322.35   813.8 2348.66   822.4 2351.14   839.6  2360.4
#Mann= 5 ,-1 , 0
       0      .1       0     416    .045       0   461.4      .1       0
  508.03      .1       0  622.97      .1       0
#XS Ineff= 2 , 0
           380.9 2288.64
Permanent Ineff=
       F       F
Bank Sta=416,461.4
XS Rating Curve= 0 ,0
Exp/Cntr=0.3,0.1

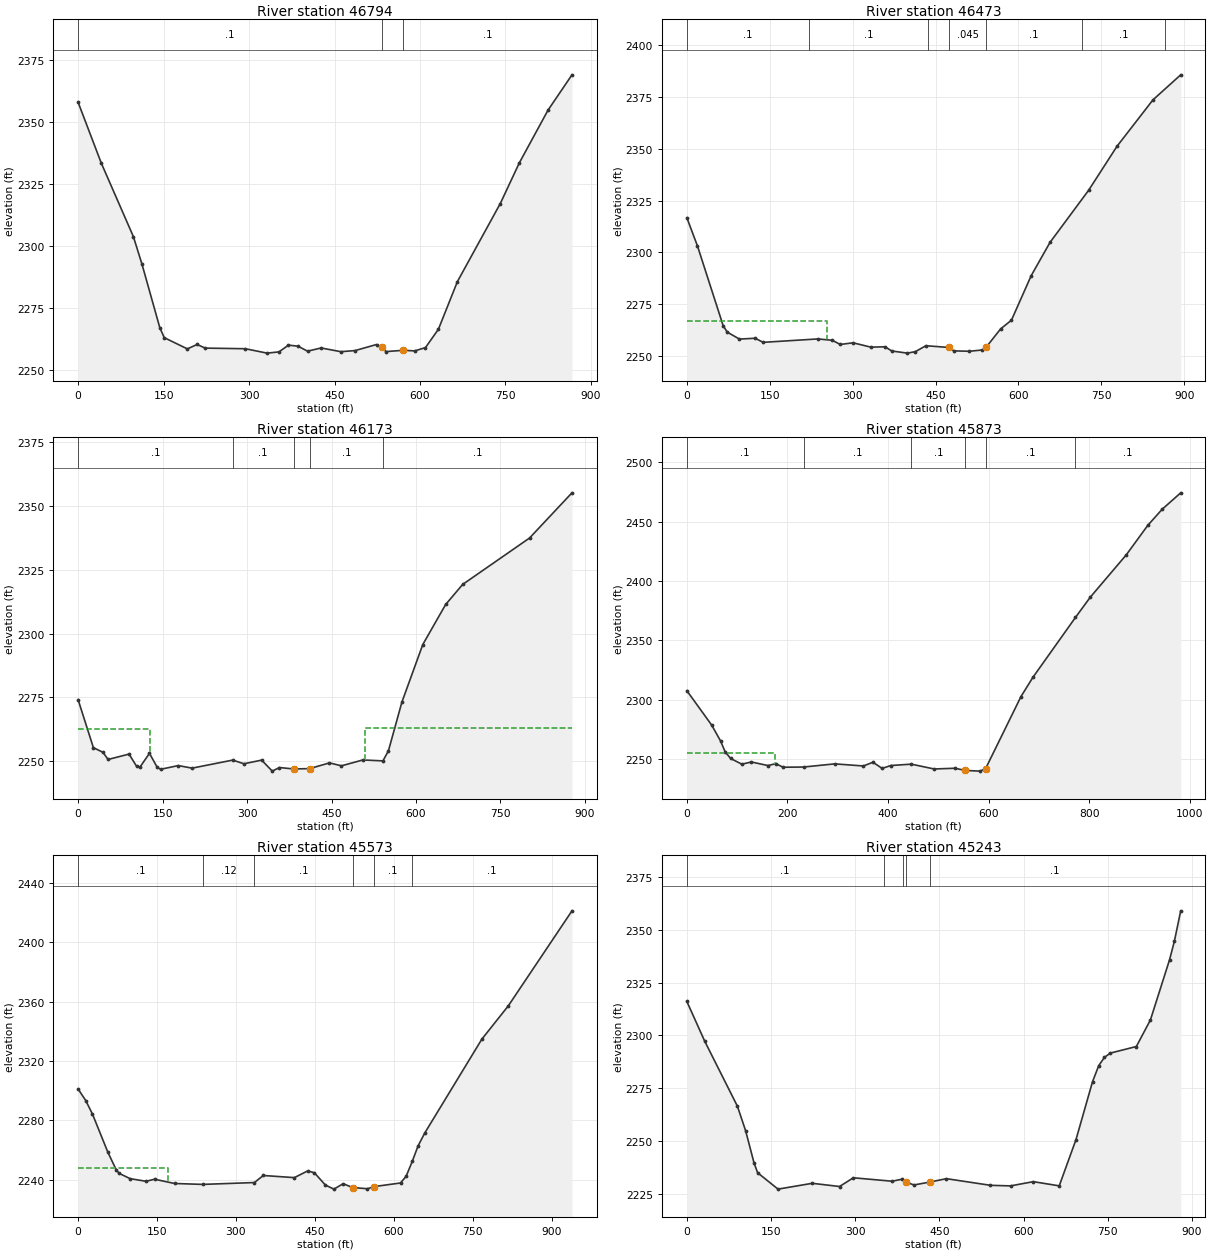
Type RM Length L Ch R = 1 ,46794   ,298.1,320.2,333.8
XS GIS Cut Line= 3
2397239.94816008673477.3284950232397487.74867824673282.664369366
2397646.58320558672754.480304141
#Sta/Elev= 30
       0 2357.79    40.8 2333.22      97 2303.71     112 2292.68   143.3 2267.09
   151.1 2263.03   191.7  2258.5   208.8 2260.27   223.1 2258.81   293.5 2258.56
   331.6 2256.79   352.5 2257.29   369.2 2260.01   385.9 2259.59   402.6 2257.58
   426.5 2258.87   461.1 2257.37   486.1 2257.82   523.7 2260.26   532.5 2259.06
   540.4 2257.41     571 2257.93   590.6 2257.68   609.6 2259.02   632.3 2266.41
   665.7 2285.62   740.9 2317.03   774.3  2333.4   824.5 2354.57   866.7 2368.85
#Mann= 3 ,-1 , 0
       0      .1       0   532.5    .045       0     571      .1       0
Bank Sta=532.5,571
XS Rating Curve= 0 ,0
Exp/Cntr=0.3,0.1

Type RM Length L Ch R = 1 ,46473   ,302.8,300,304.5
XS GIS Cut Line= 3
2397354.61465956673542.386148936     2397767.926      673277.214
     2398114.004      673071.333
#Sta/Elev= 30
       0 2316.76    19.2 2303.16    65.7 2264.75    73.1 2261.63    95.2 2258.28
   123.7 2258.68     138 2256.71   237.1 2258.35   263.2 2257.69   277.7 2255.68
   300.8 2256.49   332.8  2254.4   358.7 2254.56   370.8 2252.54   399.1 2251.51
   413.7 2252.24   432.6 2255.08   474.5 2254.23   483.2 2252.59   511.3 2252.41
   534.7 2253.03   541.5 2254.32   567.8 2263.19   587.4 2267.38   623.2 2288.88
   657.2 2304.88   727.1    2330   778.3 2351.14   843.4 2373.53   893.7 2385.61
#Mann= 7 ,-1 , 0
       0      .1       0  220.57      .1       0  437.12      .1       0
   474.5    .045       0   541.5      .1       0  715.33      .1       0
  864.96      .1       0
#XS Ineff= 2 , 0
          253.59 2266.97
Permanent Ineff=
       F       F
Bank Sta=474.5,541.5
XS Rating Curve= 0 ,0
Exp/Cntr=0.3,0.1

Type RM Length L Ch R = 1 ,46173   ,282.9,300,302
XS GIS Cut Line= 3
     2397605.908      673864.232      2397856.55      673554.425
2398176.90881276673198.972351054
#Sta/Elev= 30
       0 2274.11    27.1 2255.35    44.2  2253.5    53.2 2250.71    90.4 2252.82
   103.9 2248.03   109.8  2247.7   126.7 2253.12   140.6 2247.59   146.6 2246.87
   177.9 2248.32   202.4 2247.32   274.6 2250.47   294.5 2249.03   325.9 2250.46
   344.8 2246.15   357.5 2247.56   382.5    2247   411.1 2247.13   446.3 2249.37
   467.7 2248.23   505.6 2250.52   541.3 2250.16   551.1 2254.13     575 2273.18
   612.1 2295.71   652.7 2311.38   682.9 2319.23   801.7  2337.4     877 2355.08
#Mann= 5 ,-1 , 0
       0      .1       0   274.6      .1       0   382.5    .045       0
   411.1      .1       0   541.3      .1       0
#XS Ineff= 2 , 0
          128.34 2262.73   509.3            2263
Permanent Ineff=
       F       F
Bank Sta=382.5,411.1
XS Rating Curve= 0 ,0
Exp/Cntr=0.3,0.1

Type RM Length L Ch R = 1 ,45873   ,294.5,300,304.7
XS GIS Cut Line= 3
2397618.44783186 673982.81940638     2398107.906      673671.574
     2398445.685      673453.224
#Sta/Elev= 30
       0 2307.65    49.4 2278.67      67 2265.37    76.2 2256.17    87.1 2250.58
   109.4 2245.79   128.3 2247.64   161.5 2244.62   176.9 2246.25   191.4 2243.21
     232 2243.39   294.2 2246.05   351.1 2244.28   370.1 2247.41   388.4 2242.25
   405.8 2244.66   446.4 2245.81   491.9 2241.75   533.3 2242.36   553.6 2240.52
   583.4 2239.94   594.2  2242.1   664.4 2302.61   688.2 2318.87   772.9 2369.32
   802.4 2386.36     874 2422.02   916.8 2446.83   945.4 2460.38   982.2 2474.17
#Mann= 6 ,-1 , 0
       0      .1       0     232      .1       0   446.4      .1       0
   553.6    .045       0   594.2      .1       0   772.9      .1       0
#XS Ineff= 2 , 0
           175.7    2255
Permanent Ineff=
       F       F
Bank Sta=553.6,594.2
XS Rating Curve= 0 ,0
Exp/Cntr=0.3,0.1

Type RM Length L Ch R = 1 ,45573   ,340.7,330,326.4
XS GIS Cut Line= 3
2397720.97091486674112.779531928     2398222.986       673944.44
      2398614.53      673824.902
#Sta/Elev= 30
       0 2301.14    14.5 2293.36    27.2 2284.34    56.7 2258.49    72.4 2246.81
    77.8 2244.43    98.9  2240.8   129.3 2239.04   145.3 2240.44   183.3 2237.57
   236.7 2236.95   335.2  2238.2     352 2242.94   411.1 2241.51   436.4 2246.01
   449.1  2244.8   470.2 2236.49   486.3 2233.77   503.9 2237.41   521.8 2234.84
   550.1 2234.03   562.7 2235.47   612.9 2237.91   623.5 2242.35   635.2 2252.37
   646.3 2262.86   659.2 2271.64   767.6 2334.69   817.8 2357.06   938.9 2421.01
#Mann= 6 ,-1 , 0
       0      .1       0   236.7     .12       0   335.2      .1       0
   521.8    .045       0   562.7      .1       0   635.2      .1       0
#XS Ineff= 2 , 0
           170.6    2248
Permanent Ineff=
       F       F
Bank Sta=521.8,562.7
XS Rating Curve= 0 ,0
Exp/Cntr=0.3,0.1

Type RM Length L Ch R = 1 ,45243   ,280.9,270,266.6
XS GIS Cut Line= 3
2397969.52102129674505.5563617272398313.29906384674259.261468092
2398674.00106384673978.277468092
#Sta/Elev= 30
       0 2316.08      32 2297.21    90.1 2266.57   104.8 2254.91   119.6  2239.9
   126.1 2235.13   162.5 2227.38   223.5 2230.13   272.1 2228.62   296.7 2232.74
   365.6 2231.12   384.1 2232.09   390.2 2230.68     405 2229.36   432.9 2230.72
   462.6 2232.32   541.1 2229.18   576.8 2228.91   617.4 2230.91   663.6 2228.93
   693.5 2250.81   722.9 2278.12     734 2285.75   744.2 2289.67   754.8 2291.68
     801 2294.78   826.1 2307.34   860.3 2335.87   868.8 2344.53   880.1 2358.91
#Mann= 5 ,-1 , 0
       0      .1       0  350.57     .12       0  385.64      .1       0
   390.2    .045       0   432.9      .1       0
Bank Sta=390.2,432.9
XS Rating Curve= 0 ,0
Exp/Cntr=0.3,0.1

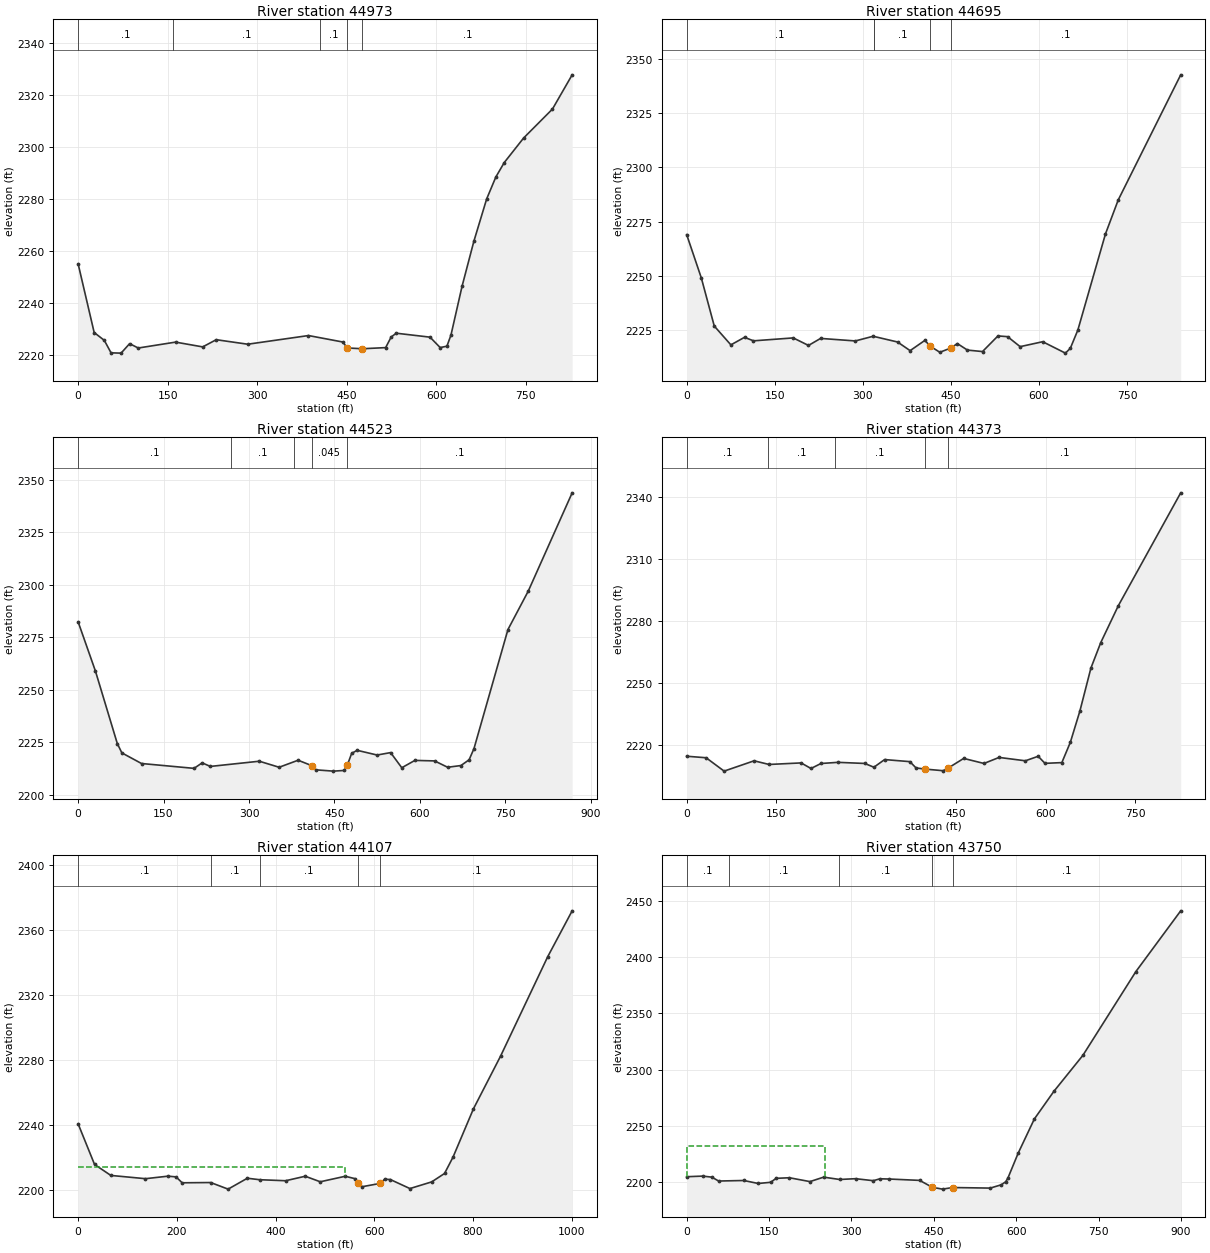
Type RM Length L Ch R = 1 ,44973   ,270,278.2,281.6
XS GIS Cut Line= 3
     2398219.796      674698.017       2398545.9      674368.828
2398804.30923406674111.617361727
#Sta/Elev= 30
       0 2255.14    26.9 2228.69    43.9 2225.66    55.2 2220.86      72 2220.75
    86.3 2224.39   100.8 2222.72   163.3 2224.99   208.8 2223.15   231.5 2225.92
   284.3 2224.18   386.1 2227.52   443.6 2225.03   451.2 2222.73   476.6 2222.44
   515.4 2222.87   524.7 2226.97   533.2 2228.42   589.8  2226.9   606.8 2222.89
   618.1 2223.42   624.9 2227.71   643.5 2246.52   663.3 2263.85   684.7 2280.12
   700.1 2288.57   714.2 2294.14   746.7  2303.6     795 2314.74     828 2327.92
#Mann= 5 ,-1 , 0
       0      .1       0  159.75      .1       0  405.46      .1       0
   451.2    .045       0   476.6      .1       0
Bank Sta=451.2,476.6
XS Rating Curve= 0 ,0
Exp/Cntr=0.3,0.1

Type RM Length L Ch R = 1 ,44695   ,176.6,171.8,165.2
XS GIS Cut Line= 3
2398243.09110957674754.9473689312398640.91310957674618.051368931
2399034.69510957674469.879368931
#Sta/Elev= 30
       0 2269.08      25  2249.1      47    2227    75.3 2218.34    98.5 2221.81
   113.8  2220.2   181.5 2221.54   207.5 2218.08   228.1 2221.31   287.3 2220.15
   317.6  2222.3   359.2 2219.66   380.6 2215.68   405.7  2220.4   415.2 2217.67
   431.2 2214.94   449.4 2216.83   461.1 2218.93   478.2 2215.94   503.9 2215.26
   530.2 2222.45   546.6 2222.12     568 2217.52   606.4 2219.79   645.1 2214.54
   653.5 2216.77   666.3 2225.17   713.3 2269.37   735.1 2285.05   841.5 2342.61
#Mann= 5 ,-1 , 0
       0      .1       0  318.52      .1       0  319.21      .1       0
   415.2    .045       0   449.4      .1       0
Bank Sta=415.2,449.4
XS Rating Curve= 0 ,0
Exp/Cntr=0.3,0.1

Type RM Length L Ch R = 1 ,44523   ,153.5,150,144.6
XS GIS Cut Line= 3
2398360.44021878675016.634512197     2398719.104       674758.22
     2399072.345      674521.481
#Sta/Elev= 30
       0 2282.42    30.4 2258.95    68.8  2224.4    76.8 2219.96   111.3  2214.9
   203.5 2212.59   217.8 2215.21   232.1 2213.51   318.1 2215.99   352.9 2213.11
   386.2 2216.46   409.8 2213.93     417 2211.89     448 2211.27   467.3 2211.59
   472.4 2213.96   480.2 2219.73   489.8 2221.19   524.9 2218.94   548.6  2220.1
   568.2 2212.88   591.2 2216.38   625.8 2216.14   648.7 2213.11     672 2213.93
   686.4 2216.67     695 2222.05   754.6 2278.75   790.2 2297.04   867.3 2343.89
#Mann= 5 ,-1 , 0
       0      .1       0  268.26      .1       0  379.29      .1       0
   409.8    .045       0   472.4      .1       0
Bank Sta=409.8,472.4
XS Rating Curve= 0 ,0
Exp/Cntr=0.3,0.1

Type RM Length L Ch R = 1 ,44373   ,272.7,266.6,263.3
XS GIS Cut Line= 3
     2398496.774       675110.01     2398830.473      674858.576
      2399128.28      674579.649
#Sta/Elev= 30
       0 2214.44    32.5  2213.7    62.6 2207.22   112.7 2212.22   137.7 2210.45
   191.3  2211.2   207.8  2208.5   224.5 2210.92   252.9 2211.48   297.7 2210.94
     313 2209.11   330.9 2212.82   373.1 2211.82   383.5 2208.76   398.1 2208.22
   429.1 2207.41   437.6 2208.79   463.1 2213.38     497 2210.94   522.3 2213.86
   566.2 2212.23   587.6 2214.41     599 2210.99   627.2 2211.35   641.4 2221.19
   657.3  2236.3   675.8 2257.18   692.2 2269.49   721.6 2287.39   825.9  2342.1
#Mann= 5 ,-1 , 0
       0      .1       0  135.99      .1       0  248.25      .1       0
   398.1    .045       0   437.6      .1       0
Bank Sta=398.1,437.6
XS Rating Curve= 0 ,0
Exp/Cntr=0.3,0.1

Type RM Length L Ch R = 1 ,44107   ,327.4,356.6,368.2
XS GIS Cut Line= 3
2398482.52222061675294.2791206582398897.40360385675188.033975606
      2399249.87       674736.62
#Sta/Elev= 30
       0 2240.46    33.3 2215.43    66.3 2208.67   136.5 2206.66   181.9 2208.21
   198.4 2207.78   210.8 2204.13   268.6 2204.29   303.9 2200.23   342.9 2206.94
   367.7 2206.03   420.4  2205.4   460.2 2208.17   490.6 2204.76   541.2 2208.15
   561.7 2206.63   566.7 2203.74   575.4 2201.71   612.4 2203.78   612.4 2203.79
     621 2206.34   632.7 2206.13   672.3 2200.58   716.4 2204.69   742.4 2209.86
   759.6 2219.93   800.9 2249.64     856 2282.19   951.5 2343.42    1001 2371.67
#Mann= 5 ,-1 , 0
       0      .1       0   268.6      .1       0   367.7      .1       0
   566.7    .045       0   612.4      .1       0
#XS Ineff= 2 , 0
           541.2    2214
Permanent Ineff=
       F       F
Bank Sta=566.7,612.4
XS Rating Curve= 0 ,0
Exp/Cntr=0.3,0.1

Type RM Length L Ch R = 1 ,43750   ,255.7,251.6,242.4
XS GIS Cut Line= 3
     2398682.687      675359.4292398981.87776275675275.548968219
     2399568.124      675328.059
#Sta/Elev= 30
       0 2204.81    29.1 2205.35    45.8 2204.43    58.2 2200.97   103.9 2201.45
   130.3 2198.79     153 2199.85   162.7 2203.36     187 2203.89   224.4 2200.47
   249.3 2204.43   278.4 2202.36   307.5 2203.05   339.7 2201.28   351.8 2202.95
   367.8 2202.77     424 2201.55   447.3 2195.38   465.7 2193.77   484.3 2195.19
   552.6 2194.69   572.7 2197.63   580.7 2200.33   584.7 2203.56   603.5 2225.82
   632.9  2256.2   668.4 2280.73   721.2 2312.74   817.6 2387.21   899.3  2441.3
#Mann= 5 ,-1 , 0
       0      .1       0   76.51      .1       0  276.41      .1       0
   447.3    .045       0   484.3      .1       0
#XS Ineff= 2 , 0
          252.57 2232.39
Permanent Ineff=
       F       F
Bank Sta=447.3,484.3
XS Rating Curve= 0 ,0
Exp/Cntr=0.3,0.1

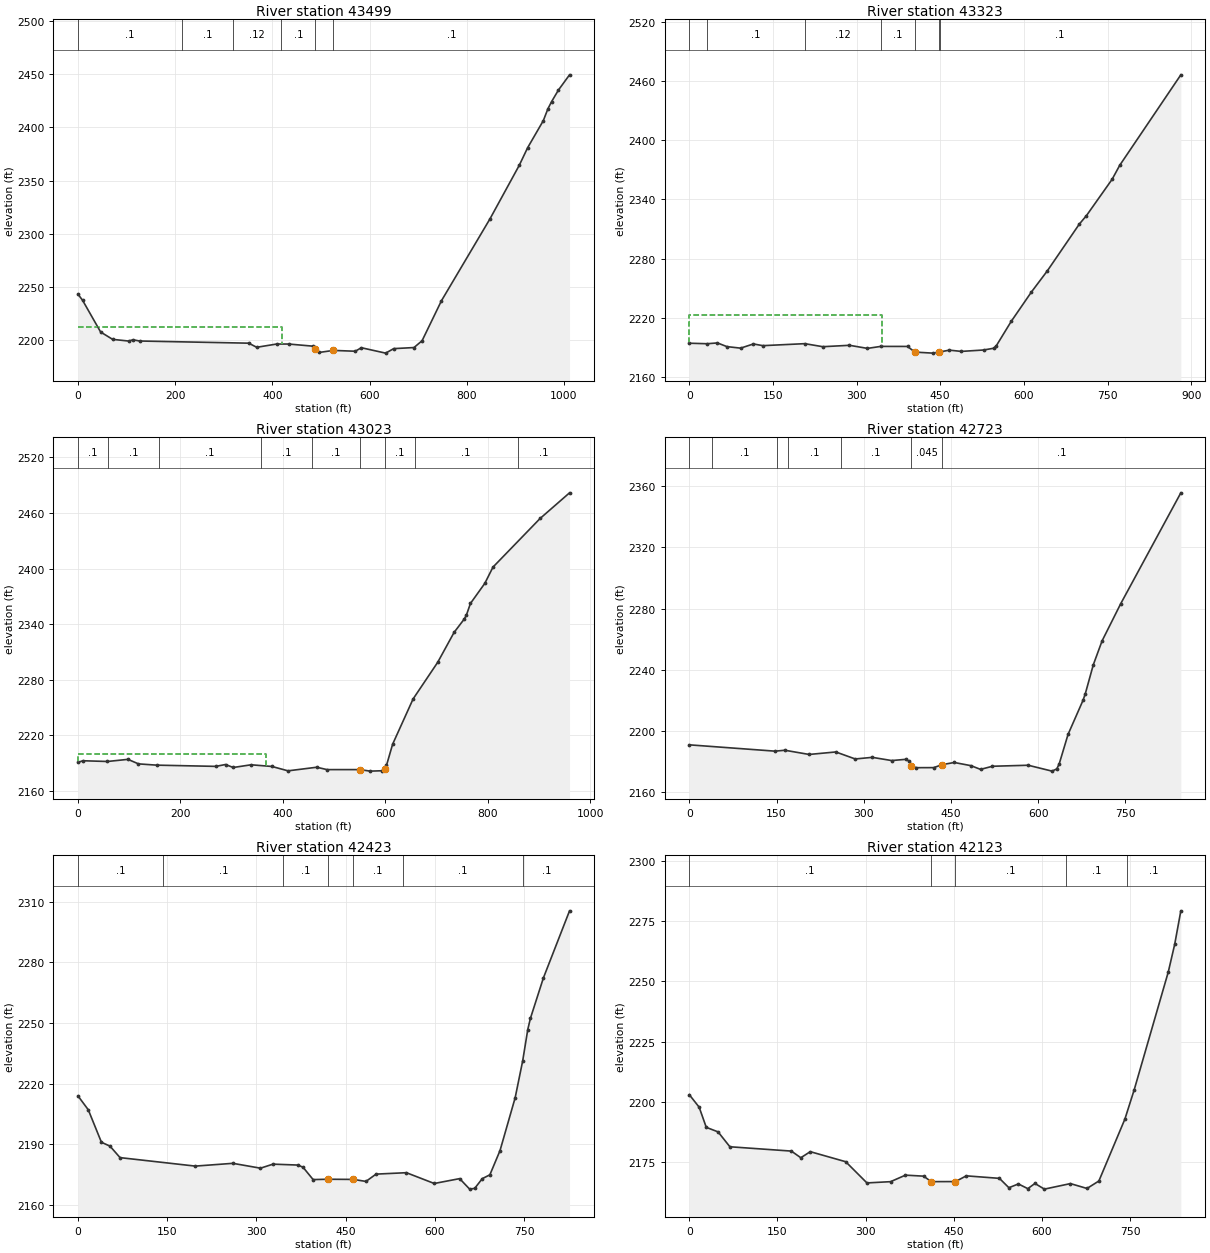
Type RM Length L Ch R = 1 ,43499   ,177.5,175.2,170.7
XS GIS Cut Line= 3
2398585.54005248675650.8796038472399066.96154767 675532.10135329
2399561.99154767 675387.13835329
#Sta/Elev= 30
       0  2242.9     9.5  2237.1    46.6 2207.26    71.3 2200.34   104.2 2198.75
   113.3 2199.95   126.6 2198.79   351.4 2196.75   367.8 2192.88   409.1 2195.95
   433.9 2195.93   483.3 2193.94   488.4 2191.14   496.7 2188.03   525.7 2189.93
   570.7 2189.15   583.2 2192.46   633.2 2187.37   649.8 2191.61   691.5 2192.62
   708.2 2199.05   748.1 2236.76   848.1 2314.01   908.3 2364.41   925.4 2380.85
   957.7  2406.4   967.3 2417.69   974.9 2424.42   988.8 2435.21  1011.7 2449.57
#Mann= 6 ,-1 , 0
       0      .1       0  214.61      .1       0  318.94     .12       0
  418.58      .1       0   488.4    .045       0   525.7      .1       0
#XS Ineff= 2 , 0
           420.7 2211.72
Permanent Ineff=
       F       F
Bank Sta=488.4,525.7
XS Rating Curve= 0 ,0
Exp/Cntr=0.3,0.1

Type RM Length L Ch R = 1 ,43323   ,285.7,300,309.6
XS GIS Cut Line= 3
     2398818.873       675866.96     2399185.089      675657.706
     2399591.682      675443.147
#Sta/Elev= 30
       0 2194.21    32.1 2193.69    50.5  2194.5    67.4 2190.78      92 2189.22
     115 2193.47   131.9 2191.74   207.2 2193.76   239.4 2190.68   287.3  2192.1
   319.5 2188.97   343.4 2190.99   391.4 2190.95   404.5  2185.2   436.9 2184.17
   447.7 2185.21   448.8 2185.35   466.5 2187.19   487.8 2185.92   527.7 2187.33
   545.8 2189.11   550.3 2191.37   577.4 2216.41   613.6 2246.15   642.1 2267.54
   699.5 2314.96   712.3 2323.55   758.3 2360.33   771.9 2374.48   881.5 2466.16
#Mann= 7 ,-1 , 0
       0      .1       0    32.1      .1       0   207.2     .12       0
   343.4      .1       0   404.5    .045       0   447.7      .1       0
   448.8      .1       0
#XS Ineff= 2 , 0
           345.9 2222.92
Permanent Ineff=
       F       F
Bank Sta=404.5,447.7
XS Rating Curve= 0 ,0
Exp/Cntr=0.3,0.1

Type RM Length L Ch R = 1 ,43023   ,292.2,300,305.1
XS GIS Cut Line= 3
2398789.27877014675902.498900962     2399362.134       675867.69
2399748.23451589 675868.51135329
#Sta/Elev= 30
       0 2190.77     9.5 2192.54    57.6 2191.75    97.6 2194.05   118.1 2189.17
   153.7 2187.79   269.2 2186.47   288.1 2188.48   303.2 2185.26   338.1 2188.18
   378.8 2186.37   410.2 2181.65   466.3 2185.54   486.4 2182.97   550.5 2182.99
   570.5 2181.34   594.5 2181.76   599.4 2183.83   602.5 2187.55   614.5 2210.42
   654.5 2259.29   702.5 2298.79   734.5 2331.08   754.5 2345.61   758.5 2349.67
   766.5 2362.36   794.5 2383.99   810.5 2401.57   902.5 2454.06     960 2481.74
#Mann= 9 ,-1 , 0
       0      .1       0   58.02      .1       0  157.83      .1       0
  357.46      .1       0  457.28      .1       0   550.5    .045       0
   599.4      .1       0   657.6      .1       0   858.9      .1       0
#XS Ineff= 2 , 0
          367.87 2200.18
Permanent Ineff=
       F       F
Bank Sta=550.5,599.4
XS Rating Curve= 0 ,0
Exp/Cntr=0.3,0.1

Type RM Length L Ch R = 1 ,42723   ,311.1,300,289.2
XS GIS Cut Line= 3
     2398829.392      676013.113     2399223.612       676131.56
2399646.86254767676226.559872874
#Sta/Elev= 30
       0  2191.1   147.6 2186.97   164.3 2187.57   206.1 2184.82     252 2186.45
   285.4 2181.87   314.7 2182.93   348.1 2180.83   373.1 2181.66   377.3 2180.56
   381.5 2177.44   381.5 2177.43   389.8 2176.18   420.4 2176.22   435.3  2178.2
   455.8 2179.57   484.5 2177.49   500.9 2175.07   521.4 2177.11   582.9 2177.77
   623.9 2173.93   632.1 2175.41   636.2 2178.65   651.4 2197.89   677.2  2220.2
     681 2224.36   694.9 2243.43     710 2259.03   741.8 2283.12   845.4 2355.68
#Mann= 7 ,-1 , 0
       0      .1       0   39.85      .1       0  150.28      .1       0
  170.38      .1       0  260.72      .1       0   381.5    .045       0
   435.3      .1       0
Bank Sta=381.5,435.3
XS Rating Curve= 0 ,0
Exp/Cntr=0.3,0.1

Type RM Length L Ch R = 1 ,42423   ,288.5,300,302.3
XS GIS Cut Line= 3
 2398807.6810851676541.690212771     2399230.835        676401.2
2399588.78244679676272.668595743
#Sta/Elev= 30
       0 2213.99    17.3 2207.13    39.4 2191.08    53.8 2189.16    70.7 2183.49
   197.1  2179.3   260.3 2180.67   306.7 2178.27   327.8 2180.27   369.9 2179.81
   378.3 2178.71   395.2 2172.64   420.5  2172.8   462.8 2172.72     484 2171.73
     501 2175.34     552 2176.04   598.8 2170.71   641.5 2173.11   658.3 2167.92
   666.8  2168.3   679.5  2173.1   692.3    2175   709.3 2186.94   734.8 2213.09
   747.5  2231.4     756 2246.81   760.4 2252.29   782.2 2272.26   826.2 2305.47
#Mann= 7 ,-1 , 0
       0      .1       0  143.69      .1       0  344.89      .1       0
   420.5    .045       0   462.8      .1       0  546.51      .1       0
  748.56      .1       0
Bank Sta=420.5,462.8
XS Rating Curve= 0 ,0
Exp/Cntr=0.3,0.1

Type RM Length L Ch R = 1 ,42123   ,319.4,292.2,222.9
XS GIS Cut Line= 3
     2398838.002      676599.228     2399271.904      676644.921
2399669.27421275 676692.01791492
#Sta/Elev= 30
       0 2203.04    16.8 2197.86    28.9 2189.51      49 2187.63    69.1 2181.47
   173.7 2179.68   189.8 2176.93   205.9 2179.44   266.2 2175.28   302.3  2166.5
   342.6 2167.02   367.9 2169.72   398.9  2169.3   411.6 2167.03     453 2167.06
   471.4 2169.43   527.8 2168.39   543.9 2164.51     560 2166.08   576.1 2164.13
   588.2 2166.28   604.3 2163.93   648.6 2166.22   676.8 2164.21     697 2167.29
   741.3 2192.93   757.2 2205.12   815.2 2253.91     826 2265.25   836.5 2279.17
#Mann= 5 ,-1 , 0
       0      .1       0   411.6    .045       0     453      .1       0
  640.93      .1       0  744.23      .1       0
Bank Sta=411.6,453
XS Rating Curve= 0 ,0
Exp/Cntr=0.3,0.1