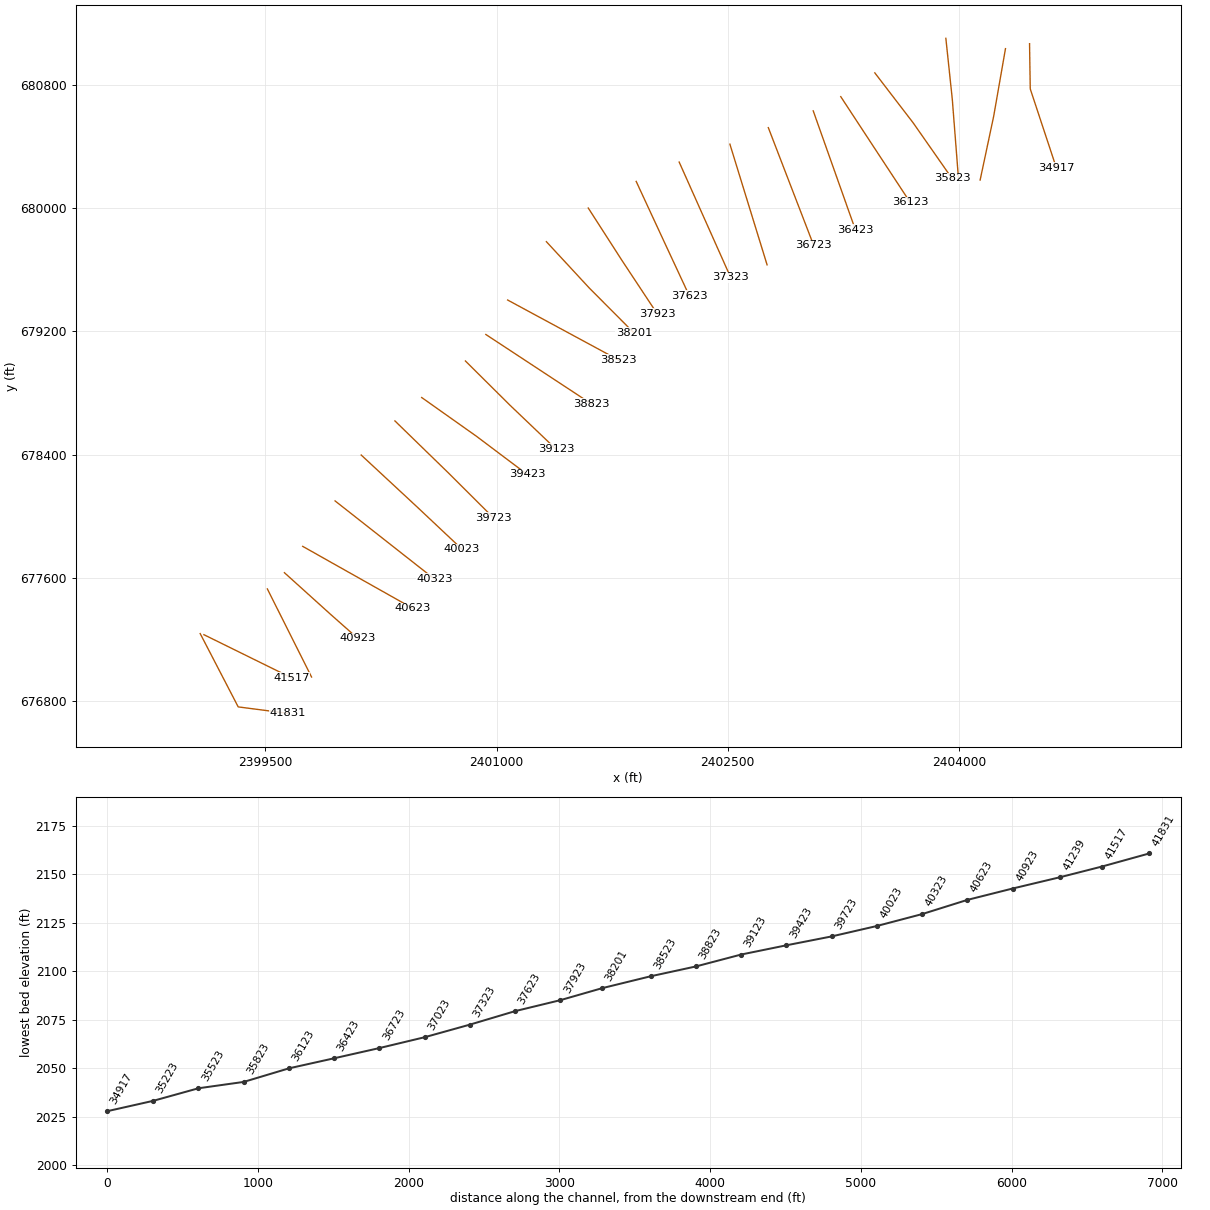
HEC-RAS study SENECACK.prj: SENECACK

--- SENECACK.g03 (geometry) --- (continued)

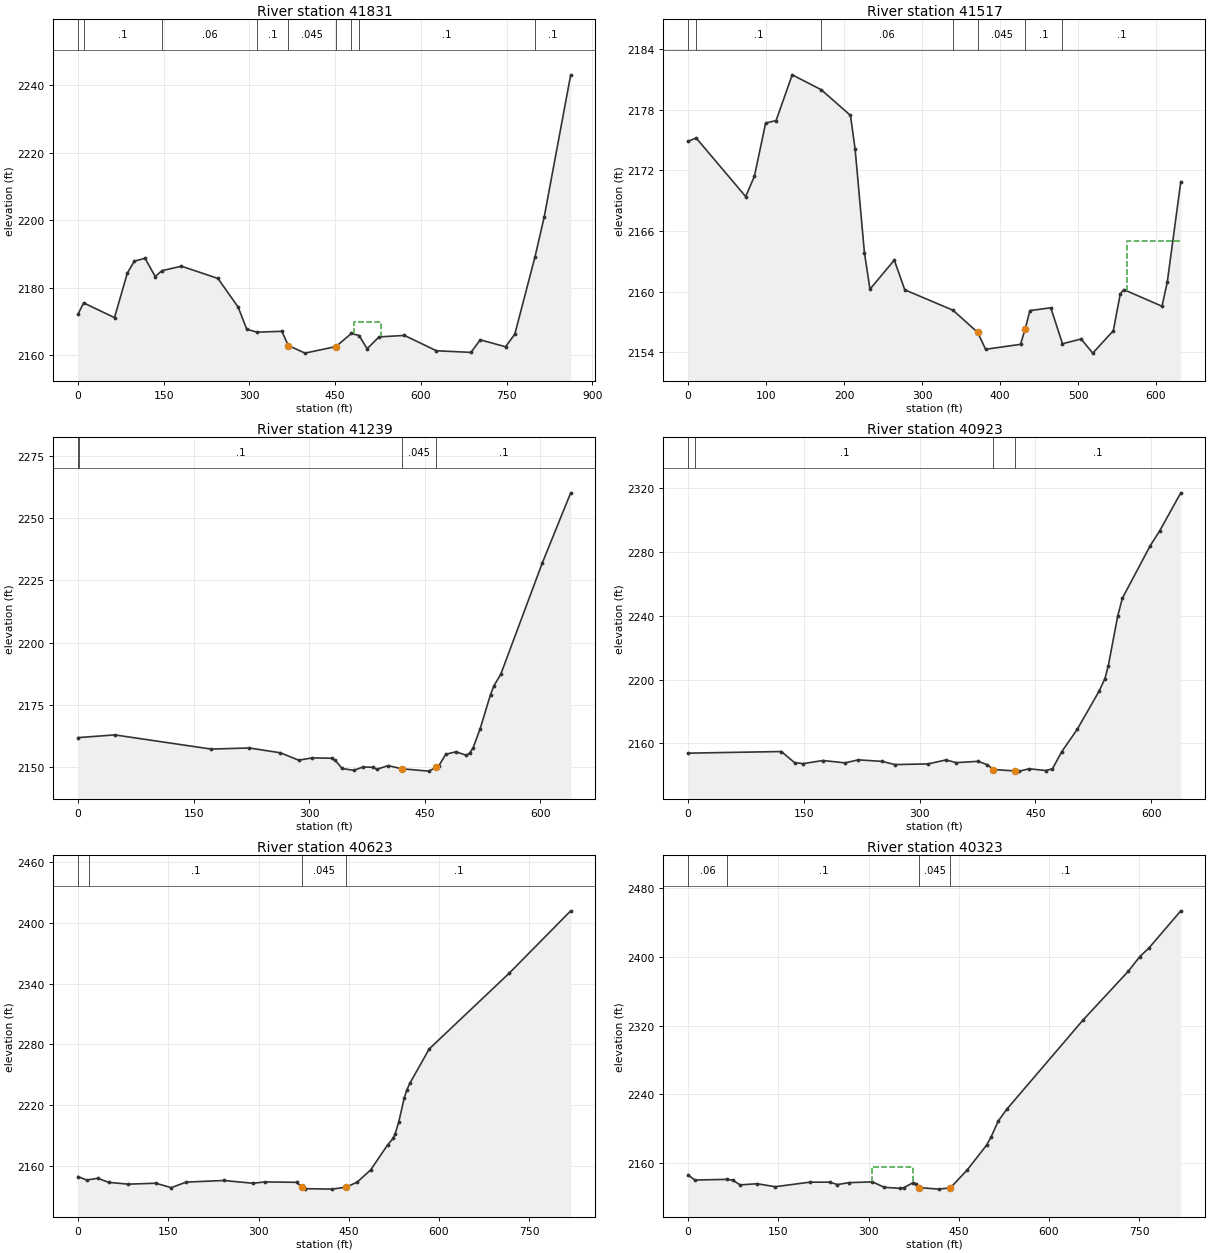
Type RM Length L Ch R = 1 ,41831   ,292.1,314.3,330.5
XS GIS Cut Line= 3
     2399077.356      677239.5052399323.98787185676763.942888621
2399647.80829251676721.941604441
#Sta/Elev= 30
       0 2172.22     9.7 2175.56    63.8 2171.19    86.3  2184.4    98.6 2187.93
   117.2 2188.77     135 2183.37   146.9  2185.1   180.9 2186.43   244.8  2182.8
   280.1 2174.34   295.2 2167.77     313 2166.88   356.7 2167.14   367.9 2162.93
   397.2 2160.67   451.3 2162.61   478.3  2166.5   491.8 2165.88   505.9 2161.97
   526.7 2165.47   571.2 2165.92   627.2 2161.37   687.7 2160.89   703.9 2164.61
   748.2 2162.56   764.4 2166.31   799.8 2189.26   815.8 2200.99   862.2 2243.13
#Mann= 9 ,-1 , 0
       0     .06       0     9.7      .1       0   146.9     .06       0
     313      .1       0   367.9    .045       0   451.3      .1       0
   478.3      .1       0   491.8      .1       0   799.8      .1       0
#XS Ineff= 1 ,-1
   482.8   529.6    2170
Permanent Ineff=
       F
Bank Sta=367.9,451.3
XS Rating Curve= 0 ,0
Exp/Cntr=0.3,0.1

Type RM Length L Ch R = 1 ,41517   ,301.4,278,257
XS GIS Cut Line= 2
2399101.53399722 677232.431827322399668.36278545676953.268891396
#Sta/Elev= 30
       0 2174.88    10.3 2175.21    73.8 2169.41      85 2171.42    99.4 2176.69
   112.8 2176.93   133.5 2181.46   170.8 2179.98   208.2 2177.44   214.2 2174.07
   226.1 2163.85   233.2 2160.24   264.4 2163.12   277.8 2160.18   339.6 2158.16
   371.4 2155.96   381.5 2154.29   426.3 2154.78   432.3 2156.31   438.3 2158.12
   465.1  2158.4   480.1 2154.84     504 2155.31   518.9 2153.91   545.3 2156.13
   554.2 2159.78   558.7  2160.2   607.7 2158.55   614.5 2160.95   631.8 2170.88
#Mann= 7 ,-1 , 0
       0     .06       0    10.3      .1       0   170.8     .06       0
   339.6      .1       0   371.4    .045       0   432.3      .1       0
   480.1      .1       0
#XS Ineff= 2 , 0
                           563.2            2165
Permanent Ineff=
       F       F
Bank Sta=371.4,432.3
XS Rating Curve= 0 ,0
Exp/Cntr=0.3,0.1

Type RM Length L Ch R = 1 ,41239   ,312,315.5,328.2
XS GIS Cut Line= 2
2399512.99799845677529.5276337452399799.84984895676957.829889745
#Sta/Elev= 30
       0 2161.87    47.7 2162.96     173 2157.26   222.2 2157.71   262.6 2155.78
   286.4 2152.81   304.2 2153.73   329.6  2153.6   334.1 2152.71   342.8 2149.47
   357.9 2148.73   369.9 2150.06   383.3 2149.96   387.8 2149.14   402.6 2150.62
   420.5 2149.35     455 2148.41   465.2  2149.9   468.4 2150.55   477.3 2155.16
   490.8 2156.19   504.2 2154.76   508.7 2155.79   512.9 2157.78   522.1 2165.51
   535.5 2179.18     540 2182.73   548.9  2187.4   602.6 2231.92   639.6 2260.19
#Mann= 4 ,-1 , 0
       0     .06       0    1.72      .1       0   420.5    .045       0
   465.2      .1       0
Bank Sta=420.5,465.2
XS Rating Curve= 0 ,0
Exp/Cntr(USF)=0,0
Exp/Cntr=0.3,0.1

Type RM Length L Ch R = 1 ,40923   ,295.6,300,305.8
XS GIS Cut Line= 3
     2399623.751      677634.688     2399927.839      677360.368
2400099.38587655677208.739233015
#Sta/Elev= 30
       0 2153.85   120.9 2154.85   137.9 2147.91     149 2147.26   174.7 2149.23
   203.4 2147.75   220.6 2149.64   251.2 2148.69   268.2 2146.68   311.1  2147.1
   334.1 2149.58   347.5 2147.89   375.8 2148.71   387.9 2146.55   395.6 2143.58
     424 2142.69   429.4 2142.57     442 2144.04   463.7 2142.95   472.2 2144.04
   484.2 2154.77   504.2 2168.68   532.6 2192.69   540.2 2200.58   544.6 2208.71
   556.7 2239.65   562.8 2250.99     599 2283.96   611.1 2293.14   638.5 2317.03
#Mann= 4 ,-1 , 0
       0     .06       0    9.32      .1       0   395.6    .045       0
     424      .1       0
Bank Sta=395.6,424
XS Rating Curve= 0 ,0
Exp/Cntr=0.3,0.1

Type RM Length L Ch R = 1 ,40623   ,305.5,300,294.7
XS GIS Cut Line= 3
     2399742.293      677805.666      2400099.09      677604.704
     2400455.888      677403.742
#Sta/Elev= 30
       0 2149.13    14.3 2145.69    32.7 2147.45      51 2143.42    83.2 2141.64
   129.1 2142.53   155.1 2138.18   179.6 2143.65     242 2145.26   290.9 2142.52
   310.7 2143.84   363.2 2143.44   372.4 2138.57   372.4 2138.56   372.4 2138.54
     377 2137.17   422.3 2136.71   445.9  2138.7   464.2 2143.68   486.6 2155.87
   514.7 2180.54   523.9 2187.02   527.3 2191.75   533.1 2203.12   542.2 2226.74
   546.8 2235.16   551.5 2241.36   583.8 2275.47   716.7 2350.34     819  2412.1
#Mann= 4 ,-1 , 0
       0     .06       0   18.64      .1       0   372.4    .045       0
   445.9      .1       0
Bank Sta=372.4,445.9
XS Rating Curve= 0 ,0
Exp/Cntr=0.3,0.1

Type RM Length L Ch R = 1 ,40323   ,302.1,300,297.6
XS GIS Cut Line= 3
     2399952.505      678100.321     2400274.459      677847.269
     2400596.414      677594.216
#Sta/Elev= 30
       0 2145.85    11.2    2140    65.3  2140.8    74.1 2139.79    86.5 2134.32
   114.8  2135.7   144.7  2132.2     202 2137.49   235.3 2137.53   248.3 2134.73
   267.5 2136.97   306.5 2137.82     326 2131.54   351.9 2130.33   358.7 2131.18
   374.2 2136.98   378.6  2135.7   384.2 2131.17   416.6  2129.4     436 2130.91
   464.1 2151.84   496.4 2180.91     504  2190.7   515.4 2208.62   529.6 2222.42
   656.1 2326.23   731.9 2383.53   750.7 2400.35   766.1 2410.54     819 2453.85
#Mann= 4 ,-1 , 0
       0     .06       0    65.3      .1       0   384.2    .045       0
     436      .1       0
#XS Ineff= 1 ,-1
   306.5   374.2    2155
Permanent Ineff=
       F
Bank Sta=384.2,436
XS Rating Curve= 0 ,0
Exp/Cntr=0.3,0.1

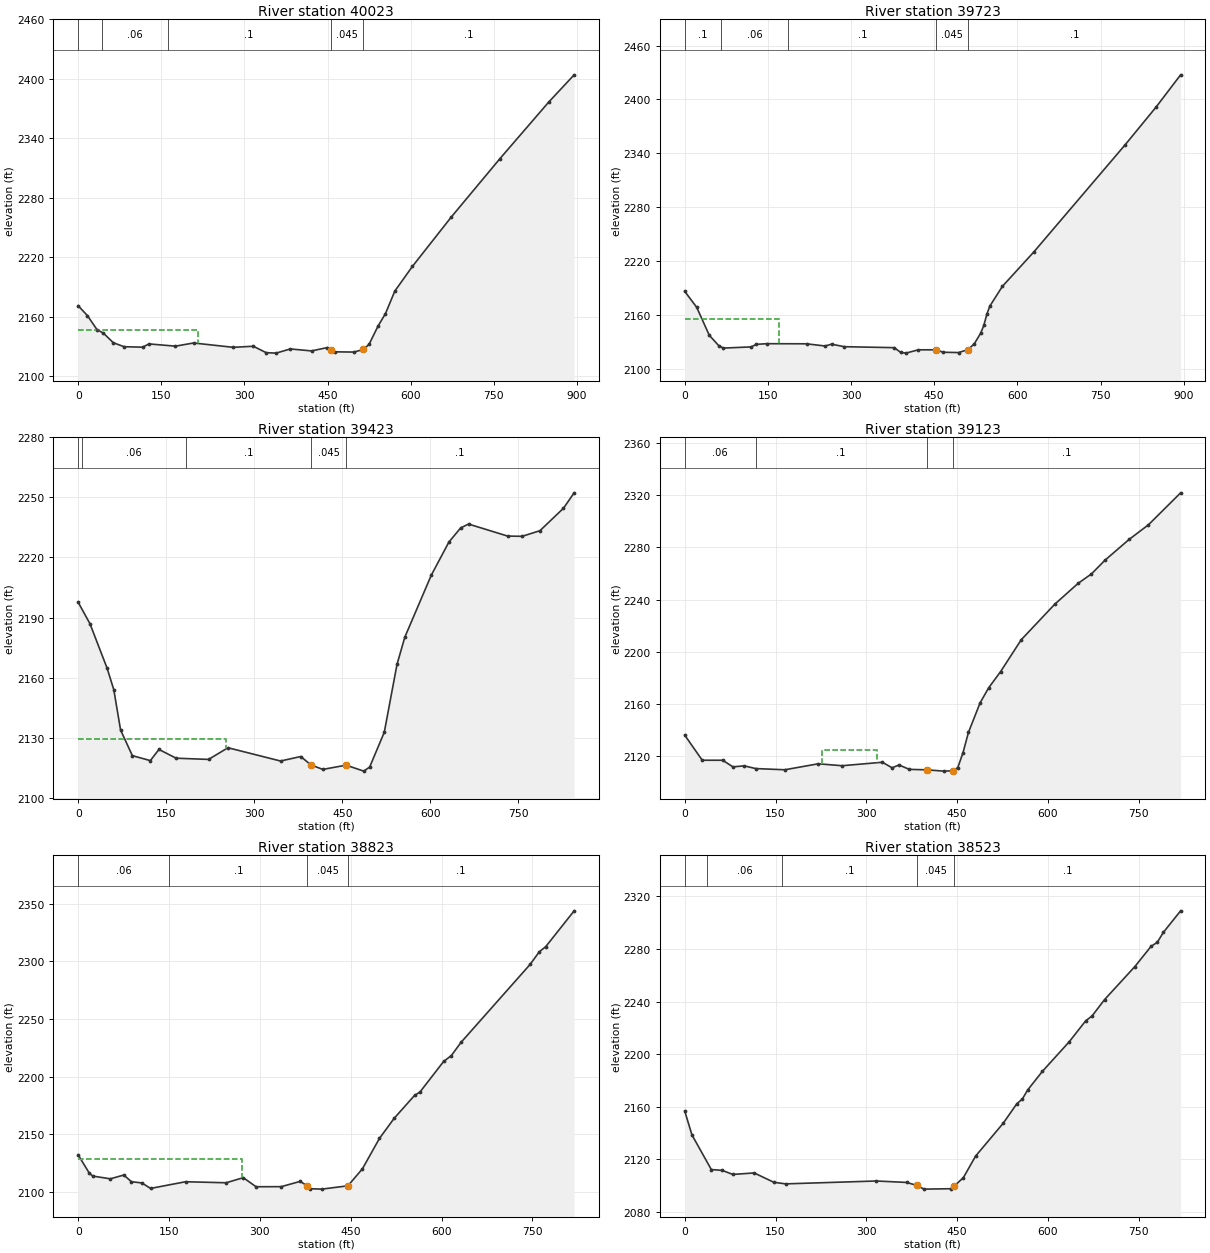
Type RM Length L Ch R = 1 ,40023   ,300.7,300,299.2
XS GIS Cut Line= 3
2400122.11877254 678397.89541193     2400478.082       678067.44
     2400776.299      677786.804
#Sta/Elev= 30
       0 2171.06    16.7 2161.08    33.8 2147.05    45.6 2143.37    63.2 2133.82
    82.7 2129.74   116.1 2129.29   127.9 2132.55   175.5  2130.3   208.3  2133.5
   279.9 2129.12     316 2130.22   339.2 2123.75   357.2 2123.27   382.9  2127.5
   421.1  2125.5   449.8 2128.89   455.4 2126.76     463 2124.58   497.9 2124.34
   514.9 2127.02   525.1 2132.24   541.5 2150.88   554.5 2162.95   571.5 2185.85
   603.2 2210.71   673.3 2260.46   761.2 2319.42   849.1 2376.37   895.2 2403.98
#Mann= 5 ,-1 , 0
       0      .1       0   42.41     .06       0  161.73      .1       0
   455.4    .045       0   514.9      .1       0
#XS Ineff= 2 , 0
          216.86 2146.14
Permanent Ineff=
       F       F
Bank Sta=455.4,514.9
XS Rating Curve= 0 ,0
Exp/Cntr=0.3,0.1

Type RM Length L Ch R = 1 ,39723   ,295,300,303.6
XS GIS Cut Line= 3
2400340.72535634678619.505643662     2400688.301      678281.435
     2400978.342       677992.37
#Sta/Elev= 30
       0 2186.68    21.7 2168.86    44.3 2137.83    61.3 2126.29    69.7 2123.51
     120 2124.82   129.2 2127.68   147.9 2128.39   219.7 2128.28   253.3 2125.81
   264.9 2127.88   287.7 2125.06   378.1 2123.98   389.4 2118.74     399  2117.9
   421.3 2121.59   454.1 2121.58   465.8 2118.88     494 2118.53   511.1 2121.86
   522.5 2128.44   533.7 2139.96   539.5 2148.71   545.1 2161.52   550.4 2170.28
     573  2192.2   629.5 2230.32   794.5 2349.73   849.8 2391.31   894.4 2427.44
#Mann= 5 ,-1 , 0
       0      .1       0   65.44     .06       0  186.68      .1       0
   454.1    .045       0   511.1      .1       0
#XS Ineff= 2 , 0
          170.43 2155.68
Permanent Ineff=
       F       F
Bank Sta=454.1,511.1
XS Rating Curve= 0 ,0
Exp/Cntr=0.3,0.1

Type RM Length L Ch R = 1 ,39423   ,309.9,300,298.2
XS GIS Cut Line= 3
2400514.44340638678771.264484051     2400869.145      678520.227
     2401197.407      678273.419
#Sta/Elev= 30
       0 2197.58      20 2186.93    49.4 2164.58    60.7  2153.9    72.2 2133.85
    92.3 2121.06   122.9 2118.58   137.6 2124.16   166.9 2119.78   222.2 2119.18
   255.2 2125.01   344.8 2118.38   379.3 2120.62   396.5 2116.44   416.9 2114.19
   456.6 2116.31   486.6 2113.33   496.7 2115.36   521.6 2132.72   543.3  2166.6
   556.6 2180.19   601.7 2211.13   631.7 2227.66   651.7 2234.73   665.2 2236.67
   731.8 2230.67   756.6 2230.55   786.9 2233.36   826.9 2244.53   845.2 2252.26
#Mann= 5 ,-1 , 0
       0      .1       0    6.39     .06       0  184.33      .1       0
   396.5    .045       0   456.6      .1       0
#XS Ineff= 2 , 0
          251.41 2129.51
Permanent Ineff=
       F       F
Bank Sta=396.5,456.6
XS Rating Curve= 0 ,0
Exp/Cntr=0.3,0.1

Type RM Length L Ch R = 1 ,39123   ,297.1,300,306
XS GIS Cut Line= 3
     2400798.182      679008.225     2401088.908      678719.702
     2401385.115      678436.969
#Sta/Elev= 30
       0 2136.19      29 2116.91    62.8  2116.9    79.7 2111.83    98.4 2112.61
   117.3 2110.53   165.4 2109.61   220.6 2114.19     260 2112.71   326.6 2115.37
   342.6 2111.11     354  2113.3     371 2109.91   399.4 2109.58   428.1 2108.57
   442.6 2108.83   451.1 2111.31   459.6 2122.57   468.7 2138.24   487.9 2160.85
     502 2172.33   521.8 2184.81   555.9 2209.21   611.2  2236.4   649.9 2252.44
   671.8  2259.6   694.1 2270.09     734 2286.03     766 2297.26   819.1 2321.73
#Mann= 4 ,-1 , 0
       0     .06       0   117.3      .1       0   399.4    .045       0
   442.6      .1       0
#XS Ineff= 1 ,-1
   226.2   318.1    2125
Permanent Ineff=
       F
Bank Sta=399.4,442.6
XS Rating Curve= 0 ,0
Exp/Cntr=0.3,0.1

Type RM Length L Ch R = 1 ,38823   ,297.7,300,303.1
XS GIS Cut Line= 3
     2400930.572      679180.265      2401272.72      678955.266
     2401614.869      678730.266
#Sta/Elev= 30
       0 2132.07    18.4 2116.22    24.1 2113.76    53.1 2111.38    75.3 2114.68
    87.8 2108.88   105.1 2107.82   119.5 2103.05   177.3 2108.85   244.4 2107.95
   272.6 2112.38   293.7 2104.51   335.3 2104.58   366.5 2109.14   378.4 2105.27
   383.2 2102.81   402.3 2102.44   445.4 2105.32   469.4  2120.1   497.5 2146.46
     522    2164   555.5 2183.75   564.3 2186.61   603.4 2213.13   616.3 2218.33
   632.1 2229.67   746.3 2297.33   761.4 2308.25   772.2 2312.82     819  2343.8
#Mann= 4 ,-1 , 0
       0     .06       0   150.7      .1       0   378.4    .045       0
   445.4      .1       0
#XS Ineff= 2 , 0
          271.05 2128.88
Permanent Ineff=
       F       F
Bank Sta=378.4,445.4
XS Rating Curve= 0 ,0
Exp/Cntr=0.3,0.1

Type RM Length L Ch R = 1 ,38523   ,330.8,322.9,315.4
XS GIS Cut Line= 3
     2401072.081      679403.809     2401432.354      679209.146
     2401792.627      679014.483
#Sta/Elev= 30
       0 2156.85    12.1 2138.52      44 2112.27    62.1 2111.63    79.4 2108.56
   114.8 2109.69   147.3 2102.58   166.7 2101.38   316.7 2103.57   366.8 2102.46
   383.4 2100.18   395.2 2097.38   439.5 2097.69   445.4 2099.88   460.2 2106.08
   480.4  2122.5   525.9 2147.43   548.6 2162.38   557.6  2165.9   566.4  2172.8
   590.9 2187.04     635 2209.44   662.3 2225.44   672.7 2229.05   693.3 2241.49
   743.5 2266.69   770.1    2282   780.5 2285.15   790.7 2292.79     819 2309.06
#Mann= 5 ,-1 , 0
       0      .1       0   37.33     .06       0  161.37      .1       0
   383.4    .045       0   445.4      .1       0
Bank Sta=383.4,445.4
XS Rating Curve= 0 ,0
Exp/Cntr=0.3,0.1

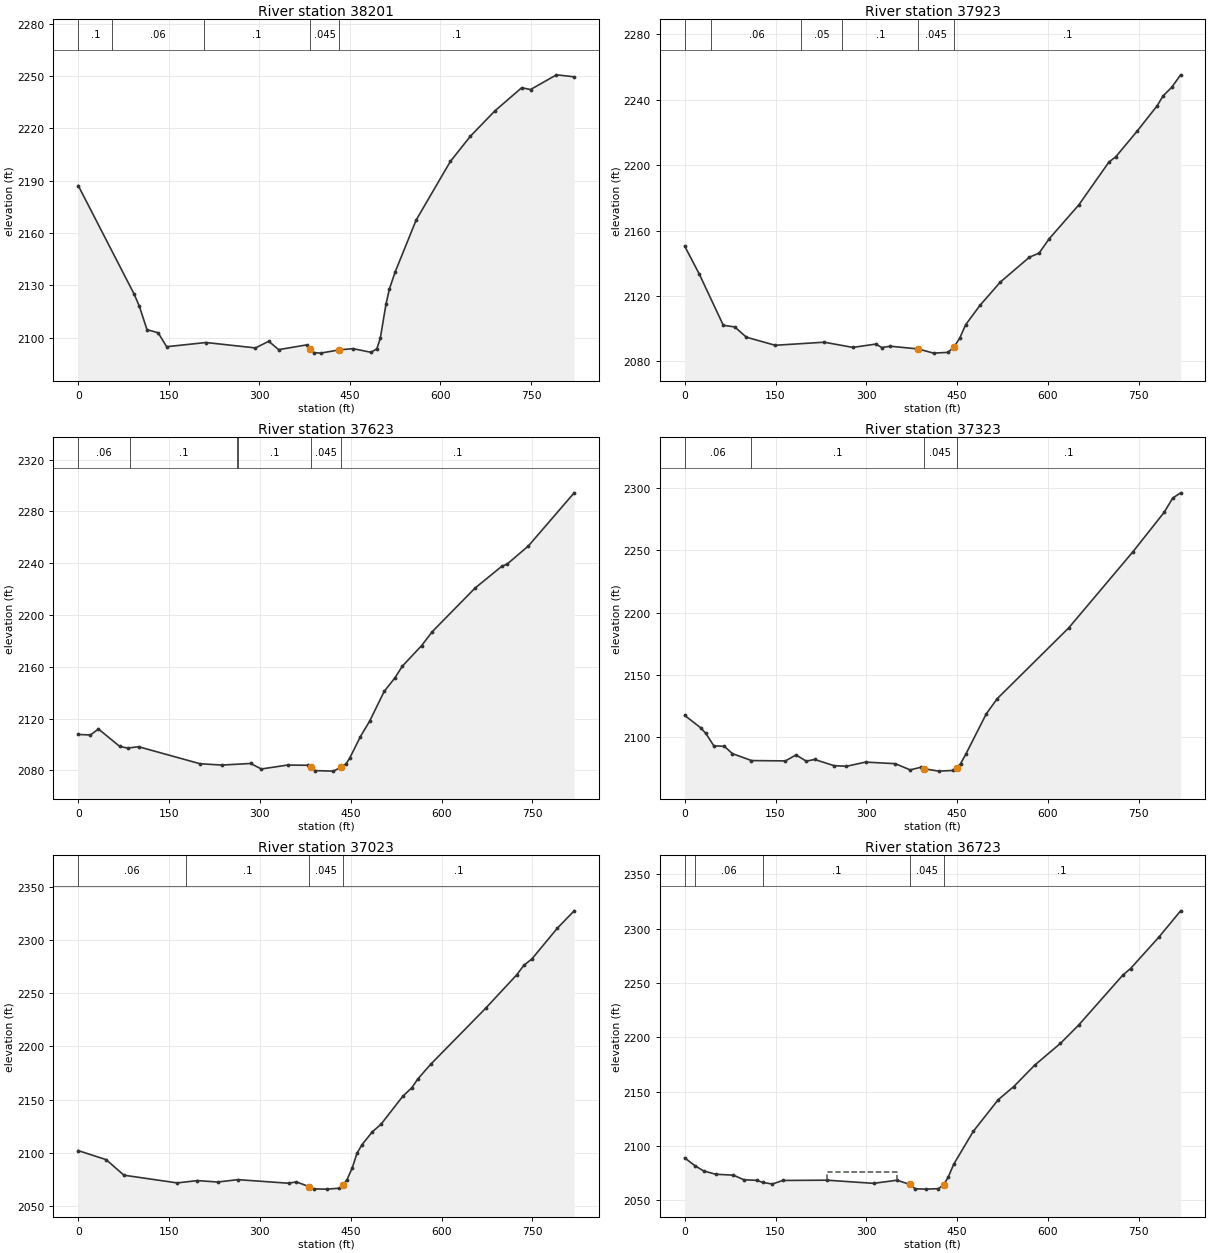
Type RM Length L Ch R = 1 ,38201   ,281.2,277.1,271.6
XS GIS Cut Line= 3
     2401323.229      679782.475 2401603.1389149679480.210659578
     2401892.049      679190.112
#Sta/Elev= 30
       0 2187.29    92.8 2124.95   101.3 2118.05   113.9  2104.7   132.4 2102.89
   146.5 2094.91   211.7 2097.32   293.6 2094.21   315.6 2098.03     332 2093.23
   378.7 2095.97   384.3 2093.69     390 2091.56   401.3 2091.23   432.4 2093.08
     455 2093.81   485.1 2091.69   494.6 2093.75   500.3 2099.71   509.8 2119.37
   515.4 2127.97   524.8 2137.63   559.7 2167.51   616.3 2201.09   649.5 2215.54
   689.8 2229.99   734.5 2243.36   749.2 2242.34   792.1 2250.76   821.4 2249.62
#Mann= 5 ,-1 , 0
       0      .1       0   56.52     .06       0  207.77      .1       0
   384.3    .045       0   432.4      .1       0
Bank Sta=384.3,432.4
XS Rating Curve= 0 ,0
Exp/Cntr=0.3,0.1

Type RM Length L Ch R = 1 ,37923   ,303.3,300,295.6
XS GIS Cut Line= 3
     2401595.152      680000.538     2401816.703      679656.155
     2402042.617      679314.562
#Sta/Elev= 30
       0  2150.5    24.1 2133.43    63.8 2102.06    82.8 2101.07   101.8 2094.82
   149.4 2089.85   230.3 2091.73   277.8 2088.55   315.9  2090.6   325.4 2088.48
   339.7 2089.27   385.8  2087.6     411 2085.05     435 2085.53   444.6 2088.78
   454.2 2094.18   463.8 2102.31   487.7 2114.29   521.3 2128.52   569.3 2143.74
   585.1 2146.16   601.7 2154.87   650.8 2175.68   700.5 2201.86   712.1 2205.21
   746.8 2220.63   780.3 2236.37     790 2242.38   804.3 2247.63     819 2255.26
#Mann= 6 ,-1 , 0
       0      .1       0   44.19     .06       0  192.72     .05       0
  260.43      .1       0   385.8    .045       0   444.6      .1       0
Bank Sta=385.8,444.6
XS Rating Curve= 0 ,0
Exp/Cntr=0.3,0.1

Type RM Length L Ch R = 1 ,37623   ,300.5,300,300
XS GIS Cut Line= 3
     2401906.064      680173.231     2402078.309      679801.738
     2402251.178      679430.494
#Sta/Elev= 30
       0 2107.73    20.2 2107.32    33.4 2111.95    68.7 2098.44    81.9 2097.22
    99.6 2098.26   201.1 2085.12   237.2 2084.08   284.8 2085.32   302.4 2081.06
   345.7 2084.09   378.8 2083.93   384.8 2082.24   391.5  2079.8   421.4  2079.4
   434.7 2082.52   442.1 2084.97   448.1 2089.22   466.1 2106.14   481.2 2117.95
   505.3 2141.01   522.9 2151.38   535.4 2160.56   567.1 2176.37   584.7 2187.13
   655.3 2220.78   699.4  2237.6   708.3  2239.3   743.6 2253.44     819 2294.38
#Mann= 6 ,-1 , 0
       0     .06       0   86.06      .1       0  262.18     .05       0
  263.28      .1       0   384.8    .045       0   434.7      .1       0
Bank Sta=384.8,434.7
XS Rating Curve= 0 ,0
Exp/Cntr=0.3,0.1

Type RM Length L Ch R = 1 ,37323   ,302.5,300,295.7
XS GIS Cut Line= 3
     2402184.926       680298.82     2402351.864      679924.893
     2402518.803      679550.965
#Sta/Elev= 30
       0 2117.27    26.2 2107.41      35 2102.75    48.1 2092.85    65.6 2092.36
    78.8 2086.53   110.3 2080.95   166.4 2080.67   183.9  2085.5   200.7 2080.48
   214.6 2081.82   246.6 2076.86   267.1 2076.34   298.8 2079.72   347.9 2078.44
   372.3 2073.45   389.8 2075.52     395 2074.38   419.3 2072.45   442.4 2072.98
   449.5 2075.34   455.5 2078.33   464.3 2086.12     498 2118.46   516.2 2130.76
   634.3  2187.7   740.4 2248.97   791.8 2280.59   805.9 2292.01     819 2296.27
#Mann= 4 ,-1 , 0
       0     .06       0  110.05      .1       0     395    .045       0
   449.5      .1       0
Bank Sta=395,449.5
XS Rating Curve= 0 ,0
Exp/Cntr=0.3,0.1

Type RM Length L Ch R = 1 ,37023   ,298.5,300,302.4
XS GIS Cut Line= 3
     2402514.045      680415.008     2402634.643      680023.669
      2402755.24      679632.329
#Sta/Elev= 30
       0 2102.14    46.2 2093.64    75.5 2079.05   163.4  2071.8   196.8 2073.98
   230.3 2072.64   263.8 2074.87   347.5 2071.49   360.1 2072.79     381 2068.36
   389.4 2066.11   410.2 2065.96   431.2 2066.78     437 2069.45   443.8 2074.77
   452.2 2085.38   460.5 2099.81   468.9 2107.86   485.7 2119.82   499.8 2126.75
   535.9 2153.09     551  2161.3     561 2169.54   581.9 2183.14   672.6  2235.7
   723.8 2267.03   735.8 2276.09   749.4 2282.29   791.2 2311.06     819 2327.37
#Mann= 4 ,-1 , 0
       0     .06       0  178.21      .1       0     381    .045       0
     437      .1       0
Bank Sta=381,437
XS Rating Curve= 0 ,0
Exp/Cntr=0.3,0.1

Type RM Length L Ch R = 1 ,36723   ,301,300,299.5
XS GIS Cut Line= 3
     2402763.444      680522.025     2402910.616      680139.886
     2403057.789      679757.747
#Sta/Elev= 30
       0 2089.13    17.4 2081.75    31.4  2077.1    51.4 2074.06    80.5 2073.24
    97.7 2069.01   119.1 2068.47   128.8 2066.57   144.8 2065.08     162 2068.36
   234.8 2068.61     312  2065.7   350.6 2068.57     372 2064.69   380.6 2060.71
   397.7 2060.38   419.1 2060.81   427.7 2064.54   435.1  2071.3   444.4 2083.41
   476.6 2113.54   517.7 2142.58   543.5 2154.76   577.7 2174.26   620.6 2194.49
   650.6 2211.26   723.5 2257.21   736.3 2263.29   783.5 2292.43     819 2316.38
#Mann= 5 ,-1 , 0
       0      .1       0    17.4     .06       0   128.8      .1       0
     372    .045       0   427.7      .1       0
#XS Ineff= 1 ,-1
   234.8   350.6    2076
Permanent Ineff=
       F
Bank Sta=372,427.7
XS Rating Curve= 0 ,0
Exp/Cntr=0.3,0.1

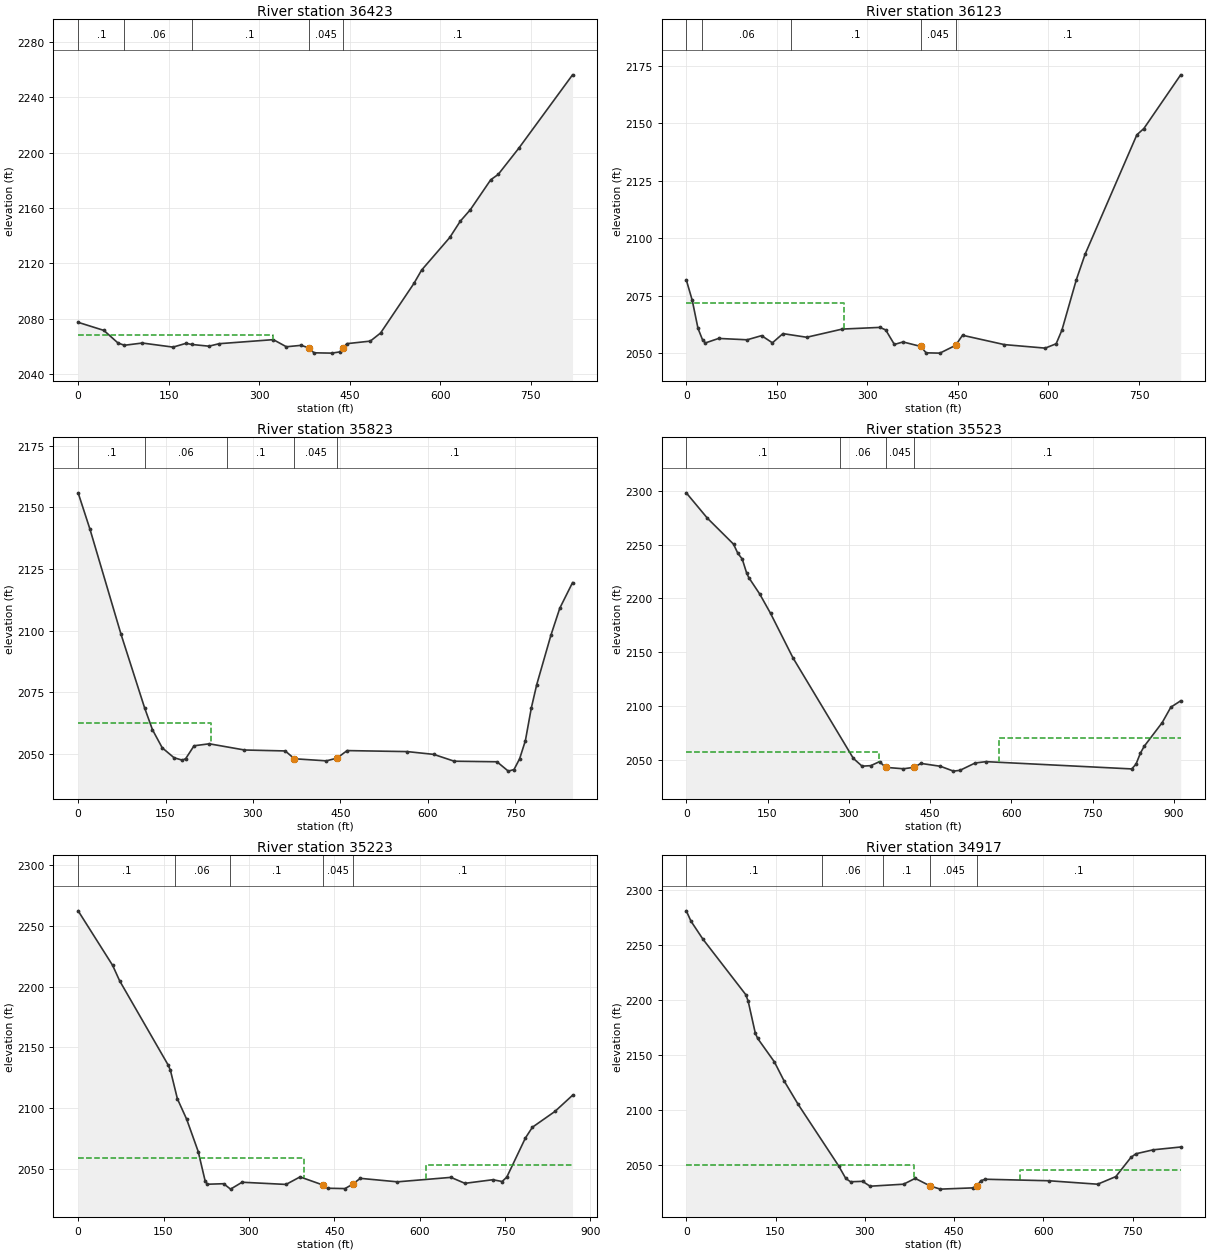
Type RM Length L Ch R = 1 ,36423   ,293.9,300,307.7
XS GIS Cut Line= 3
     2403054.648      680631.083     2403191.522      680245.135
     2403328.396      679859.188
#Sta/Elev= 30
       0 2077.39    42.6 2071.55      66 2062.46    76.6  2060.8   106.3 2062.42
   157.2 2059.47   178.8 2062.21   188.2 2061.38   216.7 2060.14   233.6 2061.94
   323.4 2064.87   344.9 2059.72   369.4 2060.75   381.6 2059.01   390.7 2055.35
     420 2055.12   433.1 2055.98   438.8 2058.79   445.1 2061.96     484 2063.81
     501 2069.66   556.2 2105.48   568.9 2115.12   615.6 2138.72   633.1 2150.55
   649.6 2158.77   683.5 2180.48   695.8  2184.3   730.2 2203.41     819 2256.33
#Mann= 5 ,-1 , 0
       0      .1       0    76.6     .06       0   188.2      .1       0
   381.6    .045       0   438.8      .1       0
#XS Ineff= 2 , 0
           322.4    2068
Permanent Ineff=
       F       F
Bank Sta=381.6,438.8
XS Rating Curve= 0 ,0
Exp/Cntr=0.3,0.1

Type RM Length L Ch R = 1 ,36123   ,298.2,300,301
XS GIS Cut Line= 3
      2403233.36       680723.15     2403457.921      680380.714
     2403682.855      680038.522
#Sta/Elev= 30
       0 2081.85     9.9 2072.89    19.4 2060.72    27.2 2055.55    31.7 2054.37
    53.6 2056.33   100.8 2055.74   124.7 2057.54   142.7 2054.42   160.1 2058.43
   199.5 2056.84   258.3  2060.4   320.8 2061.14   330.4 2060.02   344.7 2053.71
   359.1  2054.8   388.3 2052.85   397.3 2050.06   420.1 2049.93   446.1 2053.32
   457.6 2057.71   526.9 2053.64   594.6 2052.11   612.7 2054.01   622.3 2059.98
   646.2 2081.96   660.6 2092.97   746.4 2145.01     758 2147.74     819 2171.13
#Mann= 5 ,-1 , 0
       0      .1       0   26.44     .06       0  173.55      .1       0
   388.3    .045       0   446.1      .1       0
#XS Ineff= 2 , 0
          261.81 2071.55
Permanent Ineff=
       F       F
Bank Sta=388.3,446.1
XS Rating Curve= 0 ,0
Exp/Cntr=0.3,0.1

Type RM Length L Ch R = 1 ,35823   ,316.7,300,287.1
XS GIS Cut Line= 3
     2403454.329      680877.443     2403703.275      680553.006
 2403955.2838298680192.494744679
#Sta/Elev= 30
       0 2155.95    20.4  2141.1    73.4 2098.69   114.1 2068.64   127.6 2059.76
   144.4  2052.4   164.7 2048.37     179 2047.39   184.7 2048.03     199 2053.23
   225.1 2054.04   285.6 2051.52   355.5 2051.14   371.3 2047.96   426.2 2047.11
   444.5 2048.24   461.8 2051.28   565.2 2050.87   610.5 2049.74   645.6 2046.97
     719 2046.74   738.5 2042.94   748.3 2043.58     758    2048   767.8  2055.3
     778 2068.57   787.3 2078.08   811.7 2098.17   826.9 2109.11   848.8  2119.5
#Mann= 5 ,-1 , 0
       0      .1       0  114.14     .06       0  255.41      .1       0
   371.3    .045       0   444.5      .1       0
#XS Ineff= 2 , 0
          228.95  2062.5
Permanent Ineff=
       F       F
Bank Sta=371.3,444.5
XS Rating Curve= 0 ,0
Exp/Cntr=0.3,0.1

Type RM Length L Ch R = 1 ,35523   ,312.2,300,296.3
XS GIS Cut Line= 3
     2403915.192      681101.601     2403957.042      680705.342
2403997.01555319680192.722468072
#Sta/Elev= 30
       0 2298.08    38.9 2274.56    87.2 2250.44    95.2  2241.9   103.3 2236.58
   111.3 2223.81   115.3 2219.44   135.5 2204.17   155.6 2186.11   196.9 2144.89
   308.4 2051.49   324.5 2044.28   340.6 2044.75   356.7  2048.5   367.8 2043.17
   400.9 2041.86   420.4 2043.21     433 2046.84   469.1 2044.17   493.2 2039.67
   505.2 2040.41   533.3 2047.25   553.4 2048.47   822.2 2041.72   830.1 2046.12
   838.2 2056.35   845.2 2062.71   878.4  2084.7   894.4 2099.03   912.6 2104.97
#Mann= 4 ,-1 , 0
       0      .1       0  283.02     .06       0   367.8    .045       0
   420.4      .1       0
#XS Ineff= 2 , 0
          355.74 2057.44     577         2070.45
Permanent Ineff=
       F       F
Bank Sta=367.8,420.4
XS Rating Curve= 0 ,0
Exp/Cntr=0.3,0.1

Type RM Length L Ch R = 1 ,35223   ,296.1,306.1,323.6
XS GIS Cut Line= 3
     2404302.052      681034.721     2404225.533      680596.334
2404137.54529789680181.899872329
#Sta/Elev= 30
       0 2262.47    60.7 2217.46    72.9 2204.84   158.1 2135.49   162.2 2130.97
   174.4  2107.6   190.7 2090.77     211 2064.12   223.2 2039.86   227.2 2037.24
   255.6 2037.66   267.8  2033.2   288.1 2038.88   365.3 2037.07   389.9 2043.26
   430.2 2036.59   438.3 2033.92   468.8 2033.65   482.3 2037.19   495.6 2042.09
     561 2039.21     655 2042.89   679.6 2037.98   728.5 2040.94     745 2039.48
   753.2 2043.14   785.9 2075.35   798.2 2084.21   837.8 2097.22   868.7 2110.53
#Mann= 5 ,-1 , 0
       0      .1       0  169.37     .06       0  266.92      .1       0
   430.2    .045       0   482.3      .1       0
#XS Ineff= 2 , 0
          396.16 2058.56  610.66         2052.73
Permanent Ineff=
       F       F
Bank Sta=430.2,482.3
XS Rating Curve= 0 ,0
Exp/Cntr=0.3,0.1

Type RM Length L Ch R = 1 ,34917   ,163.7,157.8,150.3
XS GIS Cut Line= 3
2404458.19342953681066.8700347912404462.76369536 680773.50490812
2404631.48875265680263.384324902
#Sta/Elev= 30
       0 2281.02       8 2271.52      28 2255.21     100 2204.73     104 2198.81
     116 2169.65     120 2164.89     148 2143.63     164 2126.64     188 2104.92
     256 2048.97     268 2037.53     276 2034.54   296.2 2034.93   308.8 2030.49
   365.1 2032.33   384.6 2037.62   409.9 2030.69   426.8 2027.84   481.5 2028.98
   488.6 2030.98   494.9 2035.51   502.6 2036.83   608.9 2035.47   691.2 2032.32
   721.7 2039.25     747 2056.63   755.4 2059.99   784.9 2063.64   830.7 2066.16
#Mann= 5 ,-1 , 0
       0      .1       0  228.37     .06       0  330.98      .1       0
   409.9    .045       0   488.6      .1       0
#XS Ineff= 2 , 0
          381.93 2049.43  560.67         2045.33
Permanent Ineff=
       F       F
Bank Sta=409.9,488.6
XS Rating Curve= 0 ,0
Exp/Cntr=0.5,0.3