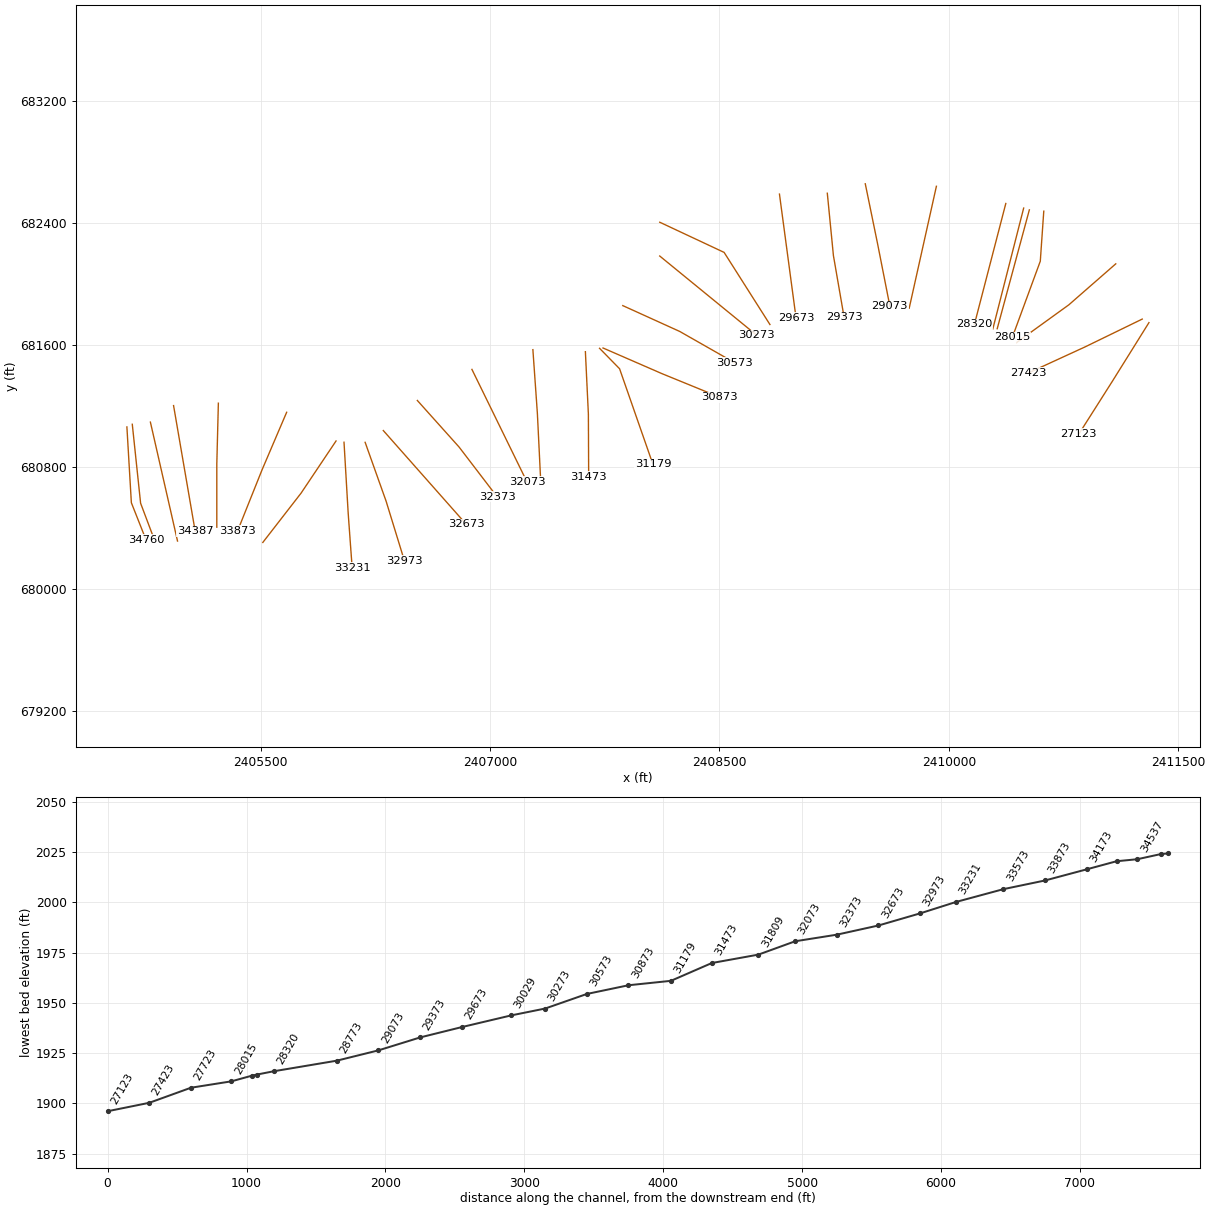
HEC-RAS study SENECACK.prj: SENECACK

--- SENECACK.g03 (geometry) --- (continued)

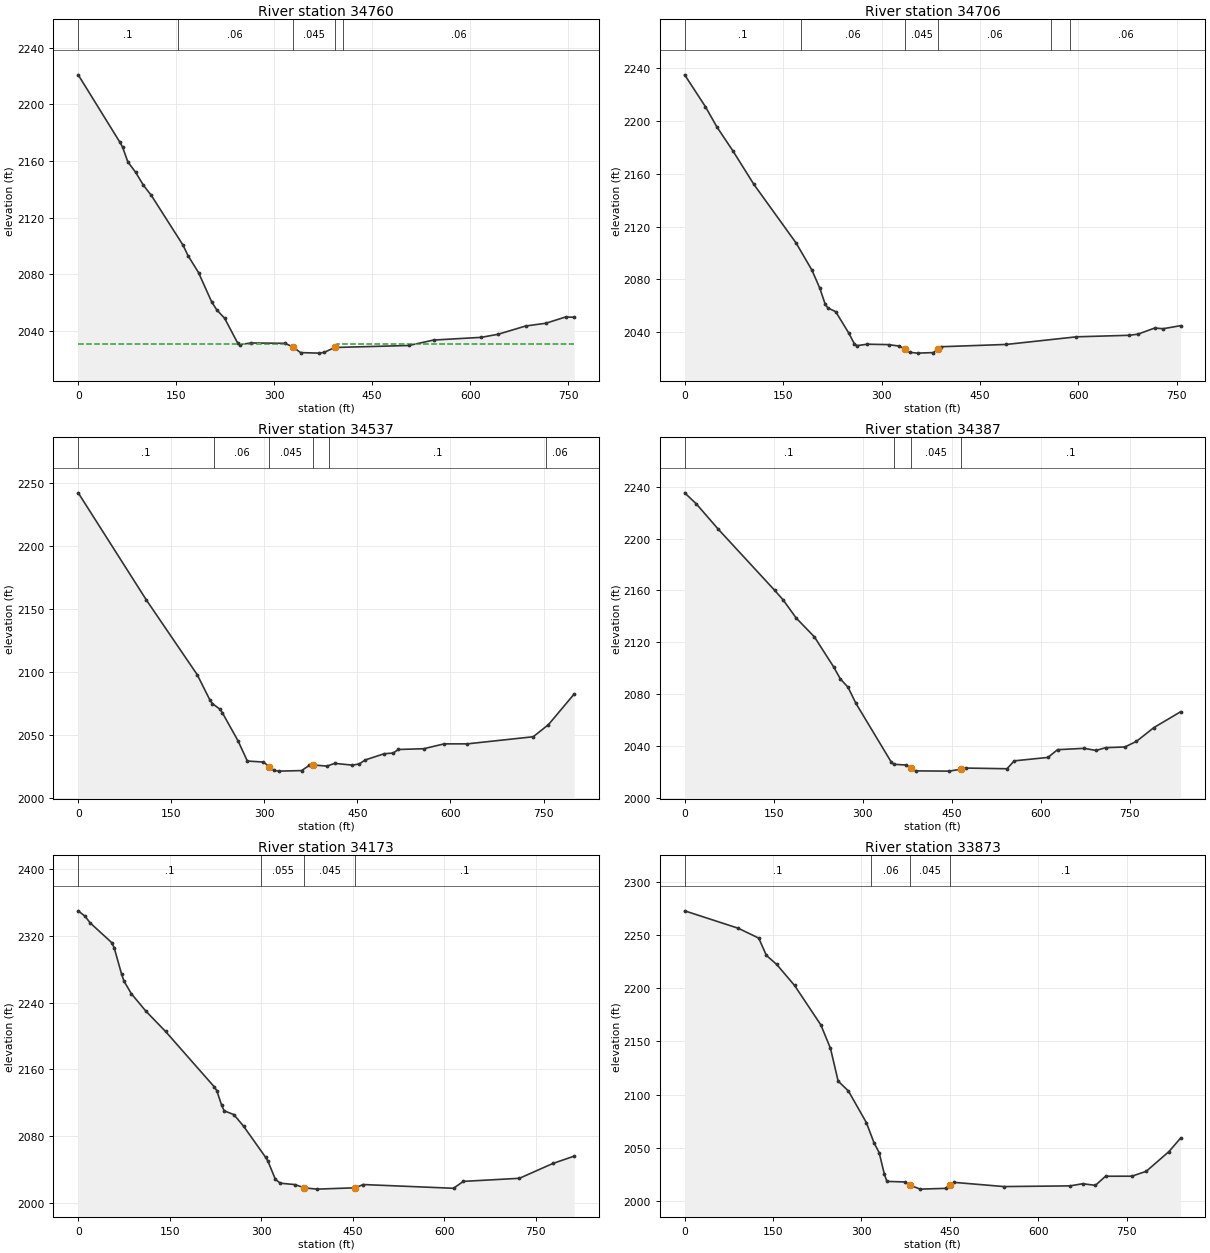
Type RM Length L Ch R = 1 ,34760   ,52.2,53.8,58.4
XS GIS Cut Line= 3
2404625.76553887681062.6391768942404655.01239188680565.442675748
2404750.76626366680322.720930357
#Sta/Elev= 30
       0 2220.79    63.9 2173.15    67.9 2169.78    75.9 2159.41    87.9 2152.01
    99.9 2142.81   111.9 2135.71   160.5 2100.54     168 2093.28   184.1 2081.29
   204.1 2060.73   212.1 2054.89     224 2049.09   244.2 2031.41   248.2 2030.48
   264.2 2031.59   316.3 2031.36   328.3 2028.89   340.3  2024.8   368.4 2024.43
   376.4 2024.94   392.4 2028.41     506 2029.82   543.8 2033.66   616.9 2035.57
   642.7 2037.75   684.8 2043.57   715.8 2045.52   745.9 2049.94     759 2049.74
#Mann= 5 ,-1 , 0
       0      .1       0  152.54     .06       0   328.3    .045       0
   392.4      .1       0   404.9     .06       0
#XS Ineff= 2 , 0
           318.5    2031   396.5            2031
Permanent Ineff=
       F       F
Bank Sta=328.3,392.4
XS Rating Curve= 0 ,0
Exp/Cntr(USF)=0,0
Exp/Cntr=0.5,0.3

Type RM Length L Ch R = 1 ,34706   ,160.8,168.7,166.5
XS GIS Cut Line= 3
2404661.02895679681079.8521510982404715.40085654680562.387578053
2404798.26212155680341.909653469
#Sta/Elev= 30
       0 2235.15    31.6    2211    49.2 2195.54    73.4 2177.56   105.5 2152.04
   169.9 2107.54     194 2086.97   206.1 2073.13   214.1 2061.21   218.2 2058.39
   230.2  2055.5   250.3 2039.12   258.4 2031.31   262.4 2029.76   278.5 2030.86
   310.7 2030.54   326.8 2029.43   336.2 2027.17   342.8 2024.69   354.9 2024.09
     379  2024.5   385.7 2027.16   391.1 2028.95   490.1 2030.68   597.1 2036.46
   677.6 2037.62   690.7 2038.46   716.3 2043.12   729.2 2042.61   755.8 2044.91
#Mann= 6 ,-1 , 0
       0      .1       0  177.44     .06       0   336.2    .045       0
   385.7     .06       0   558.4      .1       0  587.71     .06       0
Bank Sta=336.2,385.7
XS Rating Curve= 0 ,0
Exp/Cntr=0.5,0.3

Type RM Length L Ch R = 1 ,34537   ,151.4,149.6,147.7
XS GIS Cut Line= 2
2404779.45550544 681093.911382792404956.75162591680314.549977836
#Sta/Elev= 30
       0 2242.29   109.8 2157.32   191.8 2098.04   212.3  2077.9   216.4    2075
   228.7  2070.6   232.5 2067.68   257.4 2045.75   272.6 2029.55   298.5 2028.73
   307.82025.149   314.9 2022.21   323.1 2021.54     360 2021.97   372.3 2026.06
     3782026.457     401 2025.53   413.3 2027.71     442 2026.28   453.1 2027.27
   462.5 2030.39   493.2 2035.34   507.7 2035.88   515.9 2038.71   556.9 2039.31
   589.7 2043.16   626.9 2043.17   733.3 2048.81   757.9 2058.41   799.3 2082.68
#Mann= 6 ,-1 , 0
       0      .1       0  219.21     .06       0   307.8    .045       0
     378    .045       0   404.3      .1       0  754.41     .06       0
Bank Sta=307.8,378
XS Rating Curve= 0 ,0
Exp/Cntr=0.3,0.1

Type RM Length L Ch R = 1 ,34387   ,220.2,214,205.2
XS GIS Cut Line= 2
2404930.96827046681202.245638314   2405072.32806680378.459278565
#Sta/Elev= 30
       0 2235.32    19.6  2226.8    56.2 2207.46   151.7 2160.06   166.1 2152.61
   187.9 2138.69   218.5 2124.23     251 2101.01   262.5 2091.59   275.3 2085.29
   288.5 2072.91   348.4 2027.33   352.4 2025.82   373.4 2025.23   381.6 2022.79
     389 2020.73   445.8 2020.53   464.9 2021.98   474.2  2022.9   543.2 2022.37
   555.4 2028.46   612.2 2031.11   628.4 2037.09   673.1 2038.12   693.3 2036.49
   709.4 2038.62     742 2039.19   761.3 2043.49   790.7 2054.12   835.8 2066.36
#Mann= 4 ,-1 , 0
       0      .1       0  352.26     .06       0   381.6    .045       0
   464.9      .1       0
Bank Sta=381.6,464.9
XS Rating Curve= 0 ,0
Exp/Cntr(USF)=0,0
Exp/Cntr=0.3,0.1

Type RM Length L Ch R = 1 ,34173   ,310,300,282.7
XS GIS Cut Line= 3
2405223.89281796681217.963328603     2405213.628      680816.058
     2405213.804      680405.159
#Sta/Elev= 30
       0 2349.84    11.1 2343.42    19.7 2335.32    55.1 2311.66    59.1 2305.28
    71.1 2273.98    75.1 2265.53    87.1 2250.58   111.1 2229.55   143.1 2205.41
   223.1 2138.97   227.1  2134.6   235.1 2116.95   239.2 2110.38   255.2 2105.73
   271.2 2091.76   307.2 2054.59   311.2 2049.61   323.2 2028.26   331.2 2023.64
   355.2 2021.94   370.9 2018.05   391.2 2016.52   454.1 2018.11   467.2 2022.01
   615.2 2017.54   631.2  2025.8   723.2 2029.49   778.2 2047.31   812.9 2056.02
#Mann= 4 ,-1 , 0
       0      .1       0  299.37    .055       0   370.9    .045       0
   454.1      .1       0
Bank Sta=370.9,454.1
XS Rating Curve= 0 ,0
Exp/Cntr=0.3,0.1

Type RM Length L Ch R = 1 ,33873   ,305.6,300,289.2
XS GIS Cut Line= 3
     2405670.424      681158.452     2405509.989        680782.2
2405349.48380377680380.634160754
#Sta/Elev= 30
       0 2273.03      91 2256.61   125.6 2247.36   138.7 2231.01   156.1 2222.59
   186.5 2202.72   231.1 2165.55   247.4  2143.5   260.4  2112.7   277.8 2103.41
   308.3  2073.6   321.3 2054.56     330 2045.29   338.7 2025.32   343.1 2018.26
   373.5 2017.71   382.2  2014.7   399.6 2010.97   442.7 2011.69   450.1  2015.1
   457.2 2017.33   541.8 2013.38   653.8 2014.03   675.4 2016.05   696.9 2014.52
   714.1 2023.11   758.8 2023.16   783.1 2027.74   821.8 2046.38   841.5 2059.09
#Mann= 4 ,-1 , 0
       0      .1       0  316.42     .06       0   382.2    .045       0
   450.1      .1       0
Bank Sta=382.2,450.1
XS Rating Curve= 0 ,0
Exp/Cntr=0.3,0.1

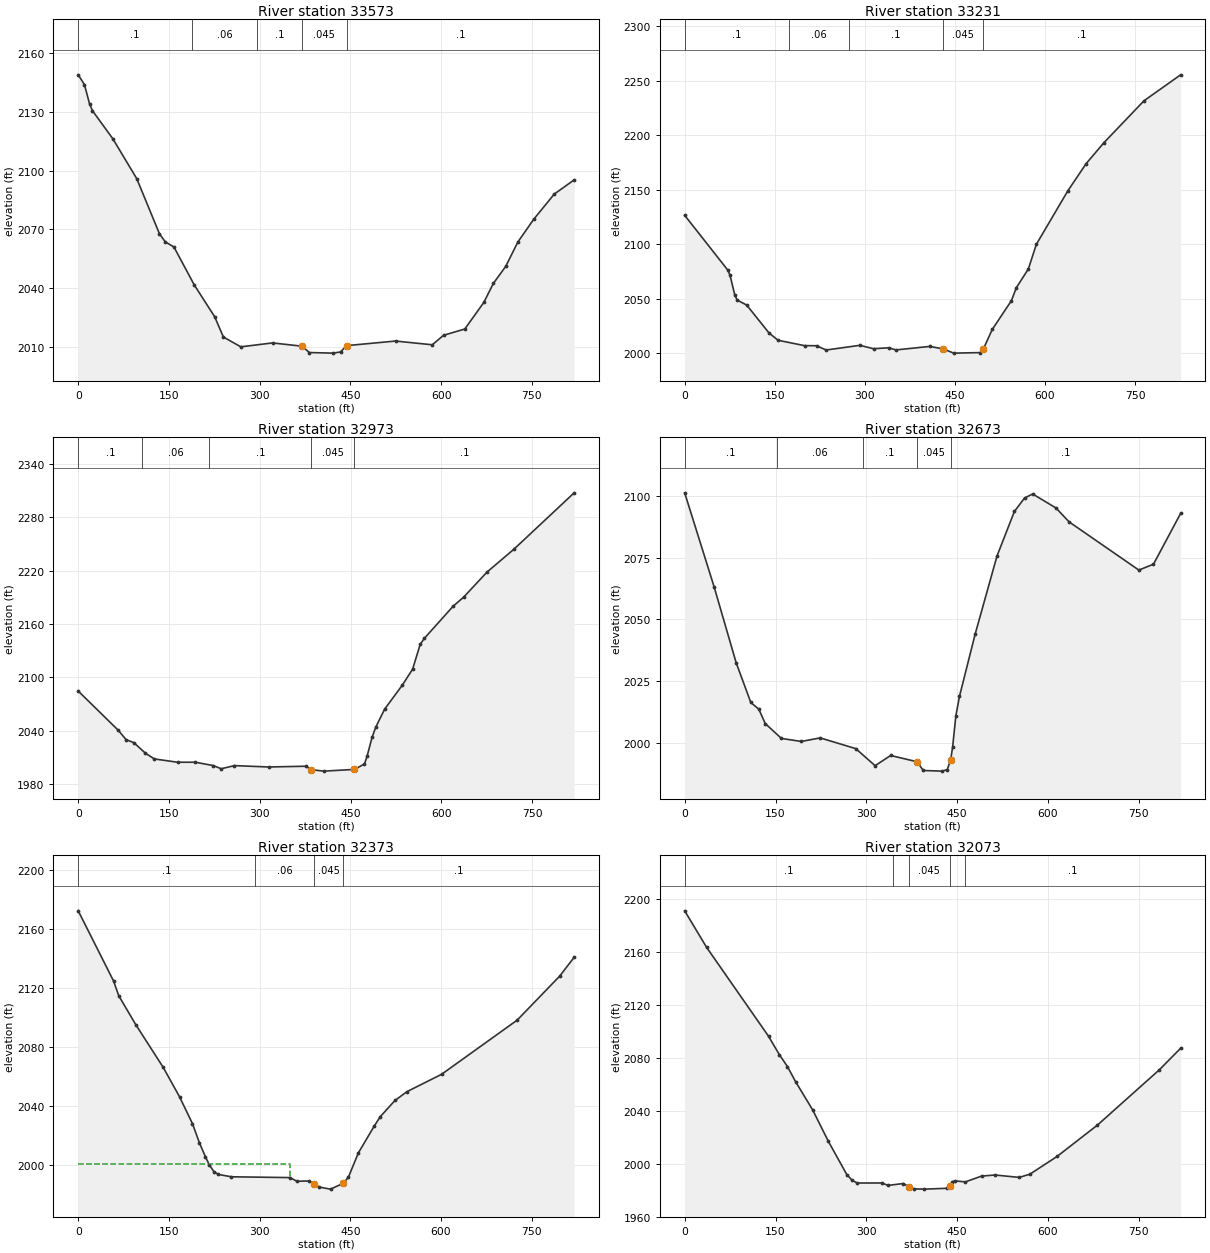
Type RM Length L Ch R = 1 ,33573   ,321.7,342,368.4
XS GIS Cut Line= 3
     2405993.413      680970.455     2405765.126      680629.057
     2405514.647      680305.362
#Sta/Elev= 30
       0 2149.03    10.3 2144.03    18.7 2134.24    23.5  2130.7    57.2 2116.34
    96.8  2095.9   134.3 2067.73   143.8 2063.61   158.3 2060.94   191.9 2041.52
   225.6 2025.27   240.1 2014.88   268.9 2009.87   321.4 2011.87     370  2010.2
   382.2 2006.95   421.1 2006.65   433.7 2007.25   443.8 2010.49   524.7 2012.83
   585.4 2010.92   604.1 2015.78   639.2 2018.98   670.6 2032.57   686.5 2042.36
   706.8 2051.01     727 2063.54   753.2 2075.15   787.1 2088.02     820 2095.29
#Mann= 5 ,-1 , 0
       0      .1       0  188.03     .06       0   295.6      .1       0
     370    .045       0   443.8      .1       0
Bank Sta=370,443.8
XS Rating Curve= 0 ,0
Exp/Cntr=0.3,0.1

Type RM Length L Ch R = 1 ,33231   ,251.1,258,267.8
XS GIS Cut Line= 3
2406045.51997871680962.0313191572406072.70153193680498.273297871
2406098.80743984680138.112696096
#Sta/Elev= 30
       0 2126.58    71.3 2076.68    75.3 2072.06    83.3 2053.86    87.3 2048.94
   103.3 2044.29   140.4 2018.75   155.5 2012.04   199.5 2007.12   219.5 2007.04
   235.5 2003.12   291.6  2007.4   314.5  2004.3   339.7 2005.15   351.7 2003.21
   407.8 2006.39   430.42004.143   447.9 2000.26     492 2000.75   497.32004.015
   512.1 2021.98   544.1 2048.43   552.2 2060.23   572.2 2077.41   585.5 2099.96
   637.9 2148.99   668.5    2174   697.7 2192.94   764.7 2231.53   825.7 2255.33
#Mann= 5 ,-1 , 0
       0      .1       0  174.11     .06       0   273.9      .1       0
   430.4    .045       0   497.3      .1       0
Bank Sta=430.4,497.3
XS Rating Curve= 0 ,0
Exp/Cntr=0.3,0.1

Type RM Length L Ch R = 1 ,32973   ,289.9,300,317.2
XS GIS Cut Line= 3
     2406183.657      680961.424     2406320.964      680575.116
     2406440.938      680183.674
#Sta/Elev= 30
       0 2084.63    66.4 2040.37    79.1 2030.02    92.1 2026.53     111 2014.77
   125.8 2008.31   164.1 2004.59   193.7 2004.56   223.4 2000.82   236.2 1997.25
   258.1  2000.8   314.5 1999.26   376.3 2000.09   384.8 1996.16     406 1994.59
   456.4 1996.51     473 2002.62   477.2  2011.1   485.5 2032.53   491.6 2043.99
   506.4 2064.41   535.7 2091.44   552.5 2109.23     565 2137.03   571.7 2143.72
   619.4 2179.96   636.9 2190.25   675.4 2218.38   719.8 2244.04   819.4 2307.49
#Mann= 5 ,-1 , 0
       0      .1       0  106.02     .06       0   216.9      .1       0
   384.8    .045       0   456.4      .1       0
Bank Sta=384.8,456.4
XS Rating Curve= 0 ,0
Exp/Cntr=0.3,0.1

Type RM Length L Ch R = 1 ,32673   ,299.9,300,297.9
XS GIS Cut Line= 3
     2406302.468      681038.667     2406573.433      680731.636
     2406844.397      680424.604
#Sta/Elev= 30
       0  2101.2    48.8    2063      85 2032.44   109.2 2016.34   122.4 2013.64
   133.1  2007.8   159.8 2001.79   192.7 2000.57   223.8 2002.01   282.5 1997.67
   314.5 1990.76   340.1 1994.89   383.8 1992.35     394 1988.82   425.1 1988.56
   433.6 1989.16   439.3 1993.14   442.5 1998.36   447.8 2010.87   453.8 2018.82
   479.8  2044.1   515.8 2075.64   544.5 2093.66   561.2 2099.08   574.7 2100.73
   613.2 2095.06   634.8 2089.45     750 2069.94   774.2 2072.31     819 2092.87
#Mann= 5 ,-1 , 0
       0      .1       0  152.12     .06       0  293.83      .1       0
   383.8    .045       0   439.3      .1       0
Bank Sta=383.8,439.3
XS Rating Curve= 0 ,0
Exp/Cntr=0.3,0.1

Type RM Length L Ch R = 1 ,32373   ,306.2,300,294
XS GIS Cut Line= 3
     2406525.018      681235.781     2406797.828      680930.749
     2407047.075      680603.923
#Sta/Elev= 30
       0 2172.52    58.5 2124.94      67 2115.03    95.3 2095.34   140.7 2066.39
   167.6 2046.54     189 2028.32   200.6 2015.25   210.5 2005.82   217.1 2000.27
   224.6 1995.76   231.9 1993.91   253.4 1992.34   350.6 1991.79   361.6 1989.29
   381.5 1989.51   389.9 1987.61   398.3 1985.39   417.3 1983.98   438.3  1987.9
   446.9 1992.08   463.5  2008.6   489.5 2026.61   499.6 2033.04   523.9 2044.04
   543.9 2050.05     601 2061.76     726 2098.45   796.4  2128.3   820.3 2141.06
#Mann= 4 ,-1 , 0
       0      .1       0  292.57     .06       0   389.9    .045       0
   438.3      .1       0
#XS Ineff= 2 , 0
          349.49    2001
Permanent Ineff=
       F       F
Bank Sta=389.9,438.3
XS Rating Curve= 0 ,0
Exp/Cntr=0.3,0.1

Type RM Length L Ch R = 1 ,32073   ,277,264.5,254.9
XS GIS Cut Line= 3
     2406882.012      681439.437     2407061.641      681071.437
     2407241.271      680703.438
#Sta/Elev= 30
       0 2190.91    36.2 2163.32   138.5 2096.16   156.4 2082.24   169.7  2073.3
   183.1 2061.89   211.4 2040.51   237.3 2016.78   267.7 1991.72   276.6 1987.33
   285.1  1985.3   325.5 1985.36     336 1983.51   361.1 1984.94     370 1982.56
     379 1980.86   395.8  1980.7   432.4 1981.31   437.7 1983.04   441.3 1985.97
   445.7 1986.97   463.5 1986.16   490.2 1990.55   512.5 1991.37   552.5 1989.56
   570.3 1992.04   614.9 2005.37   681.6 2029.05     784 2070.89     819  2087.1
#Mann= 5 ,-1 , 0
       0      .1       0  344.48     .06       0     370    .045       0
   437.7     .06       0  463.34      .1       0
Bank Sta=370,437.7
XS Rating Curve= 0 ,0
Exp/Cntr=0.3,0.1

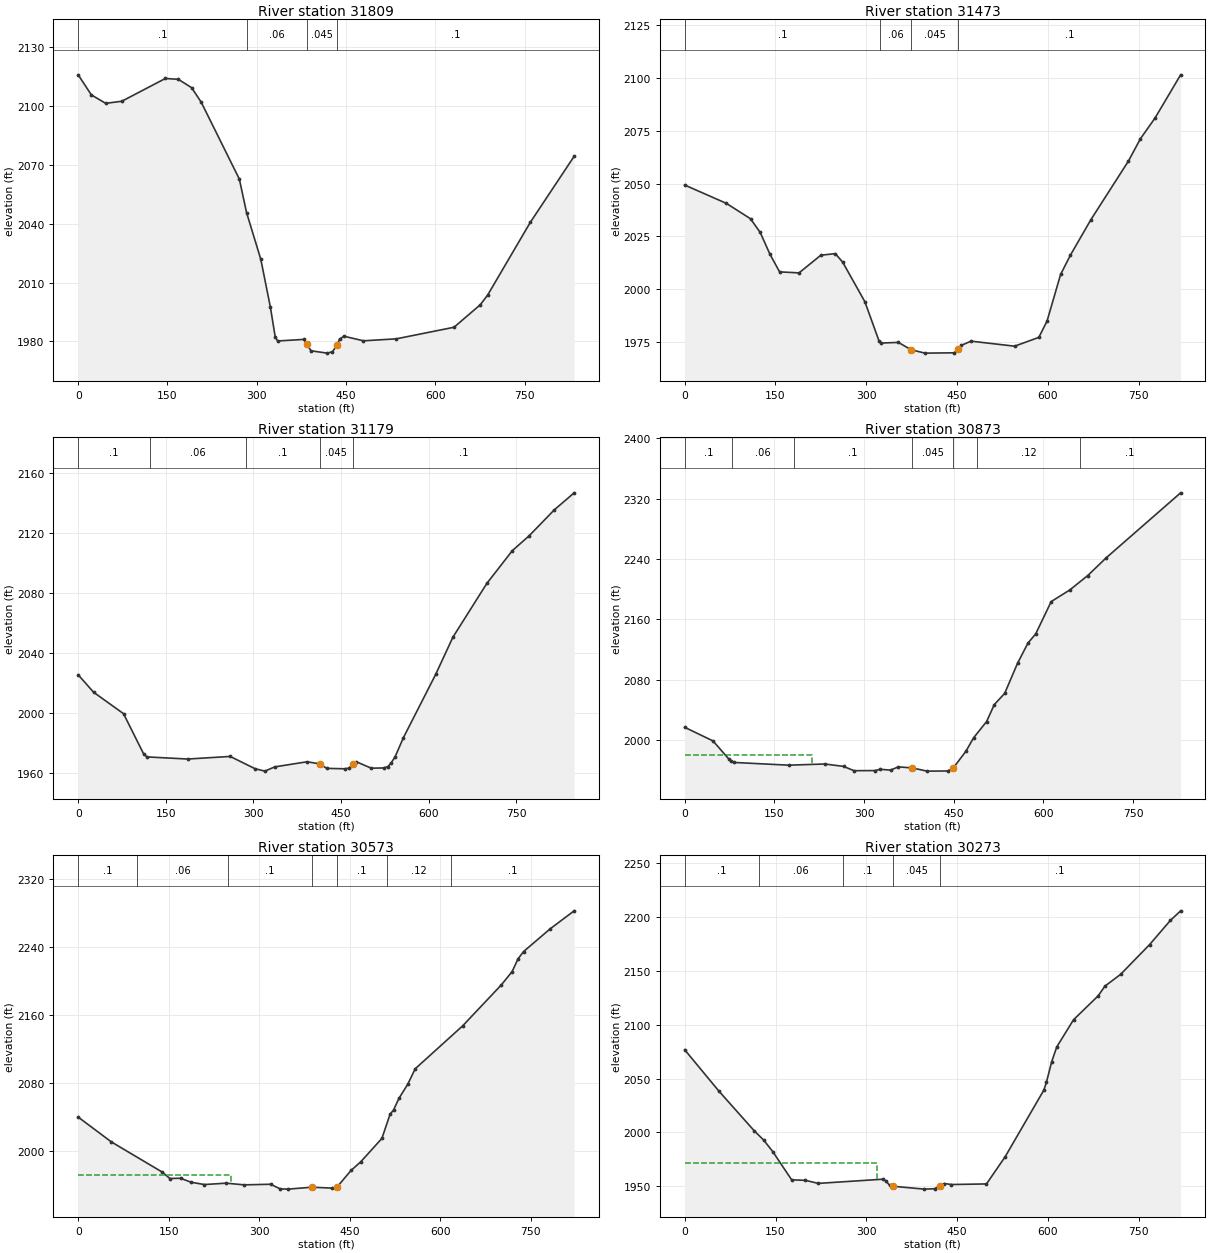
Type RM Length L Ch R = 1 ,31809   ,335,335.5,335.9
XS GIS Cut Line= 3
2407280.56285159681568.9595636122407309.90515891681151.443052969
2407330.20815891680737.295052969
#Sta/Elev= 30
       0    2116    22.1 2105.76    46.2 2101.46    73.2 2102.52   146.4 2114.13
   168.1 2113.72   190.5 2109.45   206.6 2102.07   270.7 2062.84   282.8 2045.78
   306.8 2021.86   322.9 1997.44   330.9 1982.48   334.9 1980.26   378.6 1981.05
   383.7 1978.92     391 1975.24   418.5 1974.06   427.1 1974.77   435.1 1978.14
   435.1 1978.15   439.1 1981.24   446.6 1982.68   479.2 1980.34   534.4 1981.35
   631.4 1987.26   675.4 1998.71   687.8 2003.63   759.6  2040.8   833.2 2074.45
#Mann= 4 ,-1 , 0
       0      .1       0  283.92     .06       0   383.7    .045       0
   435.1      .1       0
Bank Sta=383.7,435.1
XS Rating Curve= 0 ,0
Exp/Cntr=0.3,0.1

Type RM Length L Ch R = 1 ,31473   ,284.8,294.5,306.4
XS GIS Cut Line= 3
     2407623.882      681555.551     2407643.423      681146.057
     2407645.337      680736.642
#Sta/Elev= 30
       0 2049.31    68.7 2040.68   108.8 2033.36   124.8 2026.89     141 2016.55
   156.8 2008.27   188.9 2007.79   224.9 2016.13   248.9  2016.9     261 2012.89
   297.7 1994.18     321  1975.7     325 1974.63   353.1 1974.94   374.1 1971.46
   397.1 1969.87   445.1 1970.02   452.3 1971.66   457.1 1973.54   473.1 1975.53
   545.1 1973.15   585.1 1977.31   598.7 1985.01   621.1 2007.03   637.1 2016.07
   671.2 2032.97   733.1  2060.6   753.1 2071.24   777.1 2080.96   819.4 2101.39
#Mann= 4 ,-1 , 0
       0      .1       0  322.84     .06       0   374.1    .045       0
   452.3      .1       0
Bank Sta=374.1,452.3
XS Rating Curve= 0 ,0
Exp/Cntr=0.3,0.1

Type RM Length L Ch R = 1 ,31179   ,275.4,305.5,326.6
XS GIS Cut Line= 3
     2407716.528      681577.7032407847.49853189681443.690383053
     2408064.922      680818.915
#Sta/Elev= 30
       0 2025.21    26.3 2013.64    77.6 1999.31   111.9 1972.55   117.6 1970.49
   187.4 1969.08   260.2 1970.81   302.6 1962.64   319.4 1961.01   336.5 1963.84
   391.6 1967.25   413.6 1965.86   425.4 1962.86   456.2 1962.57   463.5 1962.98
   470.2 1965.61   476.2 1967.24   501.6 1962.97   522.8 1963.13   529.9 1963.97
   535.5 1966.38   542.5 1970.66   556.7 1983.37   611.8 2025.47   641.4 2050.37
   699.5 2086.23   743.1 2108.04   771.8 2117.94   815.1 2135.32   848.9 2146.61
#Mann= 5 ,-1 , 0
       0      .1       0  123.27     .06       0  287.78      .1       0
   413.6    .045       0   470.2      .1       0
Bank Sta=413.6,470.2
XS Rating Curve= 0 ,0
Exp/Cntr=0.3,0.1

Type RM Length L Ch R = 1 ,30873   ,300.7,300,297.3
XS GIS Cut Line= 3
2407739.16272339681579.770106365     2408125.485      681411.265
     2408503.098      681256.609
#Sta/Elev= 30
       0 2016.89    47.5 1998.77    73.7 1974.92    78.1 1971.57    82.5 1970.31
   174.1 1966.69   234.3 1968.26   265.7 1965.09   283.2 1959.38   318.1 1959.55
   326.8  1961.2   344.3 1960.19   357.4 1964.44   380.2  1963.1   405.4 1958.81
   440.1 1958.99   448.8 1962.54   470.4 1985.18   483.3 2003.05     505  2024.5
   517.9 2047.01   535.2 2061.78   556.8 2101.79   574.1 2128.36   587.1 2140.62
     613 2183.43   644.1 2198.83   674.2 2217.95   704.8 2241.27   829.5 2327.52
#Mann= 7 ,-1 , 0
       0      .1       0   79.64     .06       0  182.15      .1       0
   380.2    .045       0   448.8      .1       0  489.33     .12       0
  660.98      .1       0
#XS Ineff= 2 , 0
          212.46 1980.48
Permanent Ineff=
       F       F
Bank Sta=380.2,448.8
XS Rating Curve= 0 ,0
Exp/Cntr=0.3,0.1

Type RM Length L Ch R = 1 ,30573   ,309.4,300,296.6
XS GIS Cut Line= 3
      2407868.49      681857.509     2408240.614      681688.294
     2408599.567      681483.415
#Sta/Elev= 30
       0  2039.4      55 2010.14   139.6 1974.43   151.9    1967   169.8 1967.28
     187 1962.62   209.1 1959.87   245.3  1961.5   274.9 1959.51   318.9 1960.22
   334.9 1954.74     348 1954.47   387.3 1956.75   421.5 1955.64   429.7 1957.51
   452.4 1976.63   468.1 1986.51   503.4 2014.28   516.9 2042.68   522.8 2047.92
   531.6 2061.47   546.3 2078.22   558.6  2096.4   637.2 2146.99   701.4 2195.35
   719.3 2211.08     729 2225.94   738.2 2234.65   782.8 2261.72   822.1  2282.7
#Mann= 7 ,-1 , 0
       0      .1       0   96.66     .06       0  248.82      .1       0
   387.3    .045       0   429.7      .1       0   511.4     .12       0
  617.44      .1       0
#XS Ineff= 2 , 0
           253.1 1970.99
Permanent Ineff=
       F       F
Bank Sta=387.3,429.7
XS Rating Curve= 0 ,0
Exp/Cntr=0.3,0.1

Type RM Length L Ch R = 1 ,30273   ,262.4,244.2,238.5
XS GIS Cut Line= 3
      2408109.84      682182.651     2408426.682      681923.226
     2408743.525      681663.802
#Sta/Elev= 30
       0 2076.78    56.4 2038.41   114.9 2001.41   130.4 1992.86   145.4 1982.14
   176.7 1955.84   199.4  1955.4   220.6 1952.55   327.4 1956.45     332 1954.96
   338.7 1950.62   344.4 1949.88   395.6 1947.22   412.6 1947.57   421.2 1950.19
     429 1952.41   440.6  1951.5   498.4 1952.05   529.2 1977.28   593.1 2039.24
   597.4 2046.52   605.9 2065.29   614.4 2079.34   642.2 2104.71   682.7 2126.78
     694 2135.91   719.8  2146.8   767.9 2174.59     802 2196.93     819  2205.9
#Mann= 5 ,-1 , 0
       0      .1       0  122.16     .06       0  261.69      .1       0
   344.4    .045       0   421.2      .1       0
#XS Ineff= 2 , 0
          317.21 1971.55
Permanent Ineff=
       F       F
Bank Sta=344.4,421.2
XS Rating Curve= 0 ,0
Exp/Cntr=0.3,0.1

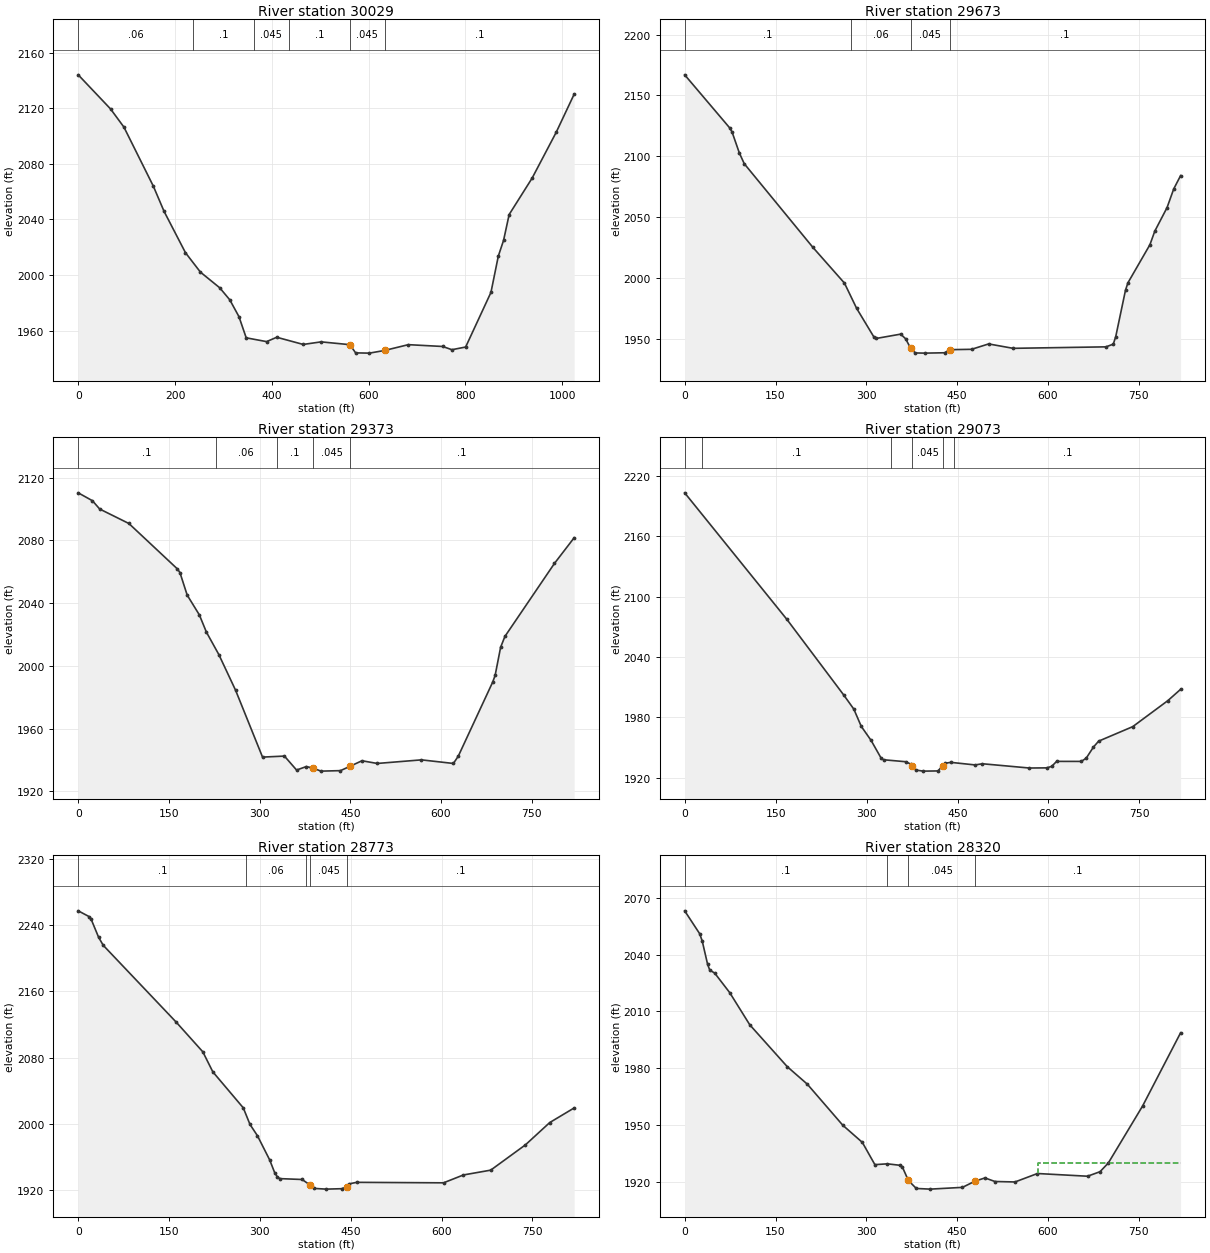
Type RM Length L Ch R = 1 ,30029   ,373.7,355.8,343.9
XS GIS Cut Line= 3
2408110.21560234682404.0642980122408530.98442559682206.355500846
     2408830.614      681733.505
#Sta/Elev= 30
       0    2144    66.9 2119.43    94.5 2106.36   155.3 2063.85   177.4 2045.78
   221.6 2016.06   252.5 2002.08   292.3 1990.84   313.2 1982.14   332.1 1970.07
   347.1 1954.82   389.2 1952.09   410.2 1955.22   464.9 1950.06     502 1951.91
   561.21949.897   573.2 1943.99   601.6 1943.81     633 1945.73   682.1  1949.9
   753.1 1948.59   772.1 1946.27   800.5  1948.2   852.8  1987.5     868 2013.58
   878.9 2024.98   890.4 2043.51   937.8 2069.67   987.6 2102.65  1024.7 2130.07
#Mann= 6 ,-1 , 0
       0     .06       0  237.42      .1       0   362.6    .045       0
   435.7      .1       0   561.2    .045       0     633      .1       0
#XS Ineff= 2 , 0
          280.29  1969.6
Permanent Ineff=
       F       F
Bank Sta=561.2,633
XS Rating Curve= 0 ,0
Exp/Cntr=0.3,0.1

Type RM Length L Ch R = 1 ,29673   ,302.8,300,302.9
XS GIS Cut Line= 3
     2408892.875      682588.428     2408947.118      682182.536
     2409001.362      681776.645
#Sta/Elev= 30
       0 2166.93    74.2 2123.36    78.2 2119.98    90.3 2102.61    98.4  2093.8
   211.4 2025.18   263.9 1995.57     284 1974.79   312.3 1951.42   316.3 1950.06
   356.7 1953.62   364.8 1949.83   373.3 1941.94   380.9 1938.14     397 1937.99
   429.3 1938.29   437.4 1940.83   473.7 1941.12     502 1945.56   542.3 1941.94
   695.7 1943.15   707.8 1945.39   711.8 1951.44     728 1989.82     732 1995.85
   768.3 2027.17   776.4 2038.38   796.6 2057.72   807.6 2073.05     819 2084.05
#Mann= 4 ,-1 , 0
       0      .1       0  275.03     .06       0   373.3    .045       0
   437.4      .1       0
Bank Sta=373.3,437.4
XS Rating Curve= 0 ,0
Exp/Cntr=0.3,0.1

Type RM Length L Ch R = 1 ,29373   ,297.9,300,302.4
XS GIS Cut Line= 3
     2409205.775      682594.259     2409245.746      682185.354
     2409315.456      681782.073
#Sta/Elev= 30
       0 2110.24    23.5 2105.21    35.5 2099.92    83.8 2090.69   164.1  2061.7
   168.2 2059.41   180.2 2045.05   200.3 2032.45     212 2021.44   232.5 2007.17
   260.3 1984.34   304.8 1941.78     341 1942.43   361.1 1933.53   377.2 1935.75
   388.4 1934.78   401.3 1932.84   433.7 1933.15   449.9    1936   469.2 1939.45
   494.5 1937.73   567.6 1940.02   620.4 1937.73   628.5 1942.38   685.3 1989.52
   689.4 1993.83   698.5 2011.77   705.6  2018.7   787.6 2065.28   820.1  2081.6
#Mann= 5 ,-1 , 0
       0      .1       0  227.21     .06       0  327.92      .1       0
   388.4    .045       0   449.9      .1       0
Bank Sta=388.4,449.9
XS Rating Curve= 0 ,0
Exp/Cntr=0.3,0.1

Type RM Length L Ch R = 1 ,29073   ,310.7,300,288.8
XS GIS Cut Line= 3
2409454.04204257 682656.19195745     2409534.824      682261.414
     2409614.816      681854.263
#Sta/Elev= 30
       0 2203.38   168.7 2077.32   262.6 2001.93     279 1988.08   291.2 1970.97
   307.5 1956.92   323.9  1939.4     328 1937.72   364.7 1935.76   372.9 1933.34
   375.5  1931.2     381 1927.49   393.3 1926.41   417.8  1926.6   425.5 1931.94
     430 1934.32   439.1 1935.12   478.9 1932.58   491.1 1933.74   568.5  1929.5
   597.1 1929.66   605.3 1931.15   613.4 1936.11   654.2 1936.08   662.3 1939.39
   674.2 1950.41   682.7 1956.25   738.9 1970.67   796.9 1996.59   817.9 2007.84
#Mann= 6 ,-1 , 0
       0      .1       0   28.55      .1       0  340.75     .06       0
   375.5    .045       0   425.5    .055       0  444.69      .1       0
Bank Sta=375.5,425.5
XS Rating Curve= 0 ,0
Exp/Cntr=0.3,0.1

Type RM Length L Ch R = 1 ,28773   ,454.8,453.6,453.8
XS GIS Cut Line= 3
     2409919.163      682639.778     2409830.172      682240.064
     2409741.181      681840.351
#Sta/Elev= 30
       0 2257.36    17.9 2250.43    21.4 2247.12    33.7  2225.4    41.3 2215.73
     162 2122.79   205.8 2087.07   222.3 2062.91   272.6 2019.41   283.7 1999.37
     296 1985.73   316.2 1956.53   324.6 1940.87   328.7 1936.27   332.9 1933.96
   369.8  1932.9   383.2 1926.04   390.2  1922.1   409.5 1921.27   435.3 1921.79
   443.5 1924.19   443.5 1924.22   447.6 1927.66   459.9 1929.47   603.3 1928.88
   636.1 1938.38   681.2 1944.19   738.5 1974.71   778.7 2001.68     819  2019.3
#Mann= 5 ,-1 , 0
       0      .1       0  277.63     .06       0  375.38      .1       0
   383.2    .045       0   443.5      .1       0
Bank Sta=383.2,443.5
XS Rating Curve= 0 ,0
Exp/Cntr=0.3,0.1

Type RM Length L Ch R = 1 ,28320   ,122.3,122.4,124.1
XS GIS Cut Line= 3
2410372.95195034 682526.925433742410270.28295034 682130.50543374
2410167.61295034 681734.08443374
#Sta/Elev= 30
       0  2063.1    24.8 2050.98      29 2047.11    37.9 2034.78    41.4 2031.79
    49.6 2030.18    74.4 2019.85   107.5 2002.86   169.4 1980.73   202.5 1971.49
   261.1 1949.78   293.4 1940.71   314.1 1928.95   334.7 1929.38   356.3 1928.58
   359.6 1927.64   369.4 1920.58   382.5 1916.36   405.5 1916.01   458.7 1916.94
   479.3  1920.2   495.9 1921.93   512.4 1920.04   545.5  1919.8   582.6 1924.26
   665.3 1922.83   685.9 1925.22   699.6 1929.82   756.2 1959.94     819 1998.66
#Mann= 4 ,-1 , 0
       0      .1       0   334.7     .06       0   369.4    .045       0
   479.3      .1       0
#XS Ineff= 2 , 0
                           583.2            1930
Permanent Ineff=
       F       F
Bank Sta=369.4,479.3
XS Rating Curve= 0 ,0
Exp/Cntr=0.5,0.3

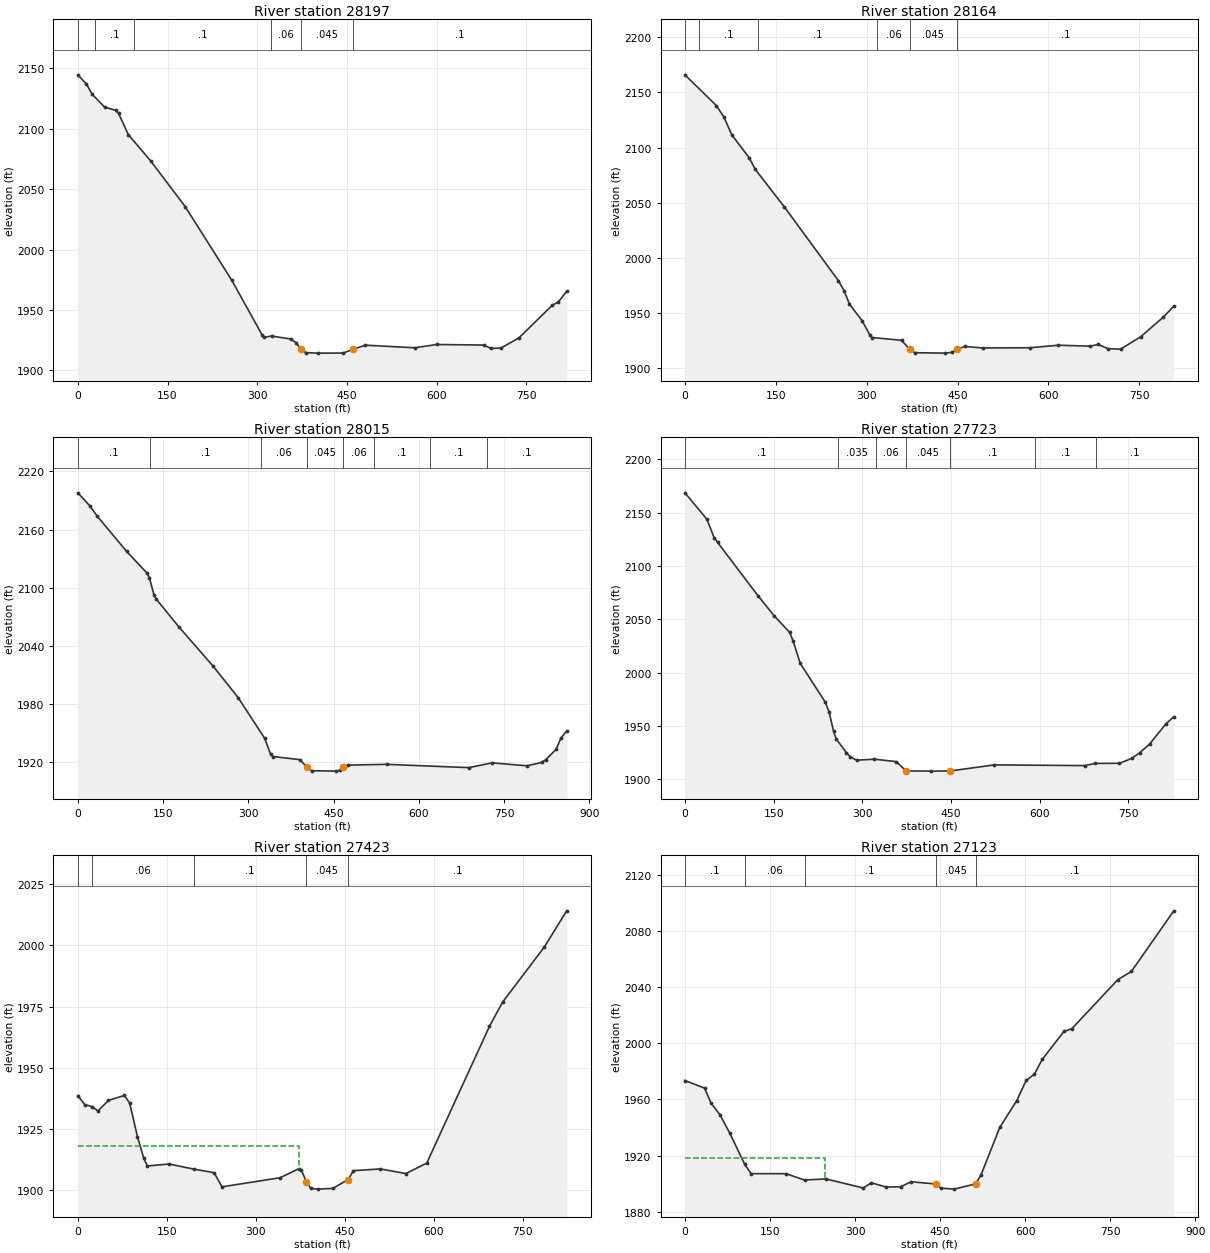
Type RM Length L Ch R = 1 ,28197   ,33.6,33.1,33.7
XS GIS Cut Line= 2
2410489.79303469682496.8538899092410288.07805431681704.275382549
#Sta/Elev= 30
       0 2144.54    14.4 2136.88    23.9 2128.47    44.8 2117.81    63.9 2115.07
    68.1 2112.64    84.6 2094.93   121.7 2073.43   179.5  2035.6   257.5 1974.63
   308.5 1929.16   311.6  1927.4     324  1928.5   356.2 1926.03   365.2 1922.94
   373.5 1917.37   381.8 1914.73   402.2 1914.35   443.7 1914.41   460.2 1917.45
   480.8 1920.93   563.8 1918.78   600.5  1921.5   678.9 1921.02   691.3  1918.2
   707.8 1918.56   737.8 1926.88   793.8 1954.02   803.6 1956.54   817.8 1965.51
#Mann= 6 ,-1 , 0
       0      .1       0    28.5      .1       0   94.46      .1       0
  322.44     .06       0   373.5    .045       0   460.2      .1       0
#XS Ineff= 2 , 0
             363    1919     478            1919
Permanent Ineff=
       F       F
Bank Sta=373.5,460.2
XS Rating Curve= 0 ,0
Exp/Cntr=0.5,0.3

Type RM Length L Ch R = 1 ,28164   ,151.3,149,145.5
XS GIS Cut Line= 2
2410526.91152848682485.0985725982410316.79350865681706.030846084
#Sta/Elev= 30
       0 2165.99      52 2138.03    64.4 2127.59    77.4 2111.59   105.9 2090.93
   116.1  2080.3   163.9 2046.46   253.2 1979.56     263 1970.11   271.6 1958.18
   292.3 1943.36   305.4 1930.14   308.9 1927.99   357.6 1925.44     371 1917.35
   379.3 1914.24     429 1913.85   441.4  1914.6     449 1917.44   462.4  1919.9
   491.2 1918.53   569.9 1918.72   615.4    1921   669.3 1920.19   681.7 1921.69
   698.3 1917.91     719 1917.44   752.2 1928.65   789.4 1946.36   806.9 1956.38
#Mann= 6 ,-1 , 0
       0      .1       0   22.59      .1       0  120.72      .1       0
  316.96     .06       0     371    .045       0     449      .1       0
Bank Sta=371,449
XS Rating Curve= 0 ,0
Exp/Cntr(USF)=0,0
Exp/Cntr=0.5,0.3

Type RM Length L Ch R = 1 ,28015   ,310.6,291.9,273.7
XS GIS Cut Line= 3
2410621.25179187682476.5300967662410598.48109131682148.577943218
     2410415.446      681649.371
#Sta/Elev= 30
       0 2197.93    21.7 2184.03    33.7  2174.1    85.8  2137.6   121.9 2115.07
   125.9 2110.27     134 2092.74     138 2088.38   178.1 2059.51   238.2 2019.16
   282.3 1986.66   328.7 1944.95   339.2 1928.45   343.3 1926.03   390.2 1922.89
     403 1915.35   411.5 1911.44   454.1    1911   460.8 1911.78   466.9 1915.23
   475.4 1917.21   543.6 1917.99   688.4  1914.6   728.9 1919.51   790.7 1916.51
   816.2 1919.96   823.1 1922.57   841.8 1933.44   850.3 1945.11   860.4 1952.44
#Mann= 8 ,-1 , 0
       0      .1       0  126.47      .1       0  322.25     .06       0
     403    .045       0   466.9     .06       0  521.09      .1       0
  620.55      .1       0  720.02      .1       0
Bank Sta=403,466.9
XS Rating Curve= 0 ,0
Exp/Cntr=0.3,0.1

Type RM Length L Ch R = 1 ,27723   ,308.5,300,290.7
XS GIS Cut Line= 3
     2411091.927      682131.262     2410785.021      681862.654
     2410445.763      681617.008
#Sta/Elev= 30
       0 2168.65      37    2144    49.4 2126.61    55.2 2122.18   123.8    2072
   151.3 2053.11   176.9 2037.97   182.8 2030.04   194.9 2008.94   237.4 1972.35
   243.5 1963.61   251.4 1945.15   255.7 1938.12   273.2 1924.99   279.9 1921.01
   290.2 1918.09   320.5 1918.99   357.7 1916.69   373.7 1908.04   415.6 1907.81
   448.4 1907.95   523.4 1913.67   675.7 1912.98   693.9 1915.04   734.8 1915.14
   755.3 1919.68   768.9 1924.94     786 1933.33   812.8 1951.74   826.7 1958.81
#Mann= 7 ,-1 , 0
       0      .1       0  258.32    .035       0  322.67     .06       0
   373.7    .045       0   448.4      .1       0  592.26      .1       0
  695.01      .1       0
Bank Sta=373.7,448.4
XS Rating Curve= 0 ,0
Exp/Cntr=0.3,0.1

Type RM Length L Ch R = 1 ,27423   ,288.8,300,327.2
XS GIS Cut Line= 3
     2411265.111      681769.253      2410891.64      681587.072
      2410520.67      681416.192
#Sta/Elev= 30
       0 1938.58    11.5  1934.9    24.5 1934.03    33.8 1932.27    51.6 1936.61
    78.4 1938.63    87.3 1935.52   100.5 1921.74   111.2 1912.84   117.2 1909.79
     154 1910.59     195 1908.51   229.6 1907.05     243 1901.25   340.9 1904.97
     372 1908.61   376.5 1908.23   385.4 1903.25   392.4 1900.63   404.4 1900.31
   429.7  1900.6   455.5 1904.23   464.6 1907.87   509.8 1908.57     553 1906.67
   588.1 1910.95   693.7 1966.84     716 1976.82   786.5 1999.41     824 2014.14
#Mann= 5 ,-1 , 0
       0      .1       0    24.5     .06       0     195      .1       0
   385.4    .045       0   455.5      .1       0
#XS Ineff= 2 , 0
             372    1918
Permanent Ineff=
       F       F
Bank Sta=385.4,455.5
XS Rating Curve= 0 ,0
Exp/Cntr=0.3,0.1

Type RM Length L Ch R = 1 ,27123   ,296.4,300,318.2
XS GIS Cut Line= 3
2411308.96804255681746.002382992     2411068.254      681359.303
     2410850.534      681015.717
#Sta/Elev= 30
       0 1973.51    34.5 1968.13    46.1 1957.39      62 1948.98    79.1 1936.01
   105.5 1913.69   116.7 1907.13     178 1907.12     211 1902.61   248.7 1903.35
   314.5 1896.94   328.8 1900.63   355.3 1897.56   380.6 1897.79   398.8 1901.38
   442.4 1899.76   451.3 1896.83   474.9 1896.11   512.8 1899.86   522.3 1906.29
   555.4 1940.16   585.4 1959.22   601.8 1973.57   616.3 1977.99   630.2 1988.54
   668.5 2008.48   682.5 2010.45   763.8  2045.5   787.5 2051.23   862.3 2094.46
#Mann= 5 ,-1 , 0
       0      .1       0   105.5     .06       0     211      .1       0
   442.4    .045       0   512.8      .1       0
#XS Ineff= 2 , 0
           246.4    1918
Permanent Ineff=
       F       F
Bank Sta=442.4,512.8
XS Rating Curve= 0 ,0
Exp/Cntr=0.3,0.1