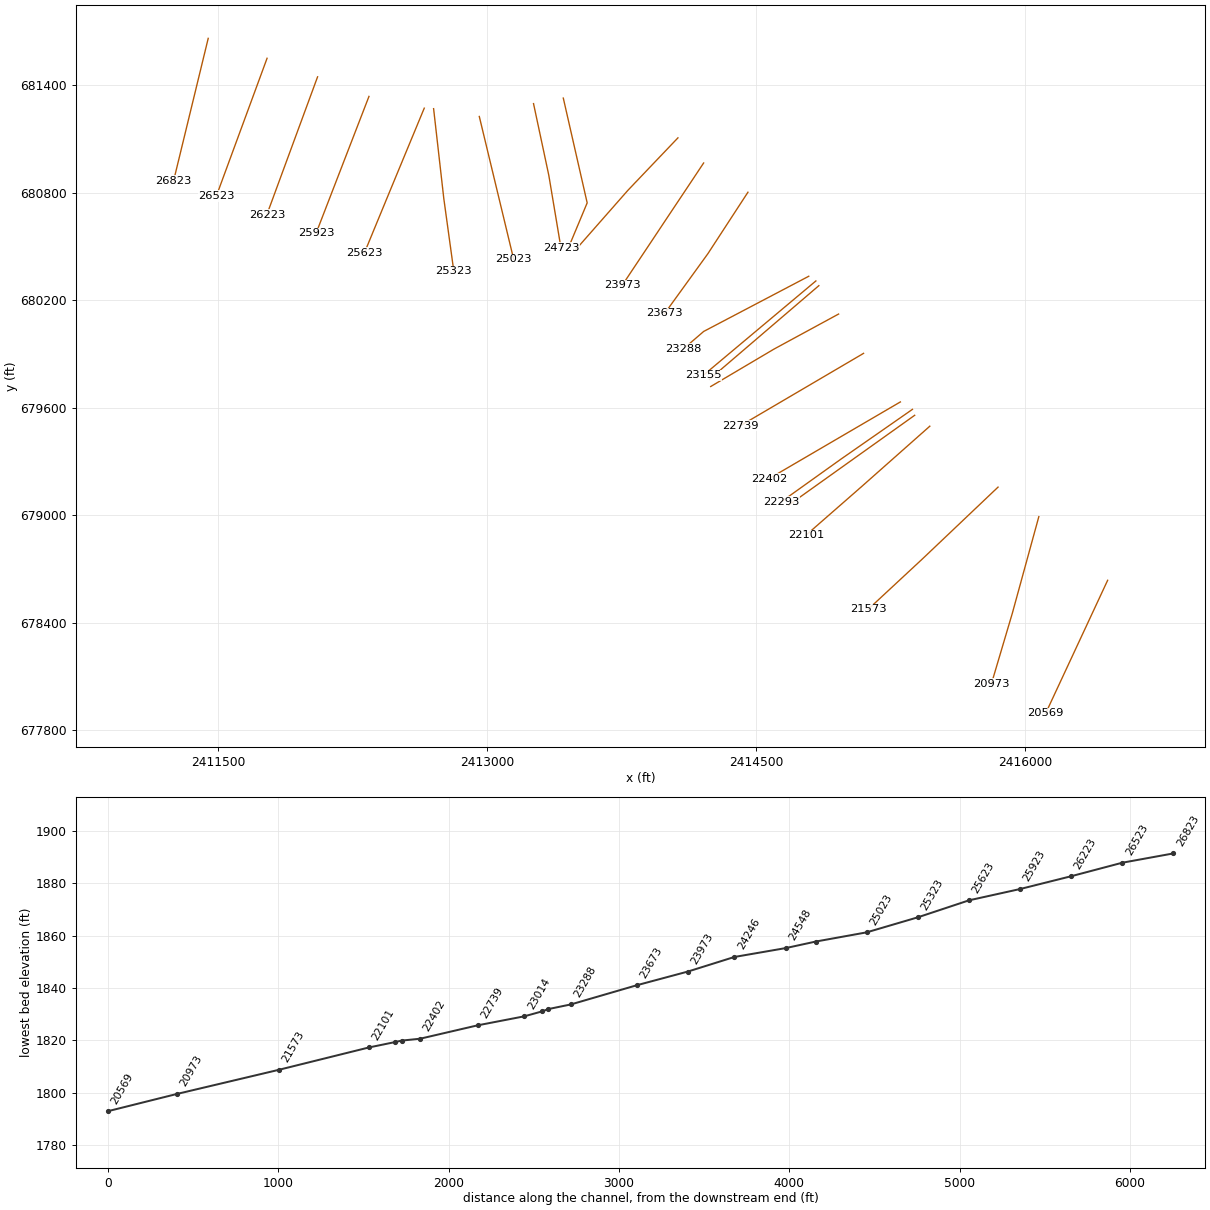
HEC-RAS study SENECACK.prj: SENECACK

--- SENECACK.g03 (geometry) --- (continued)

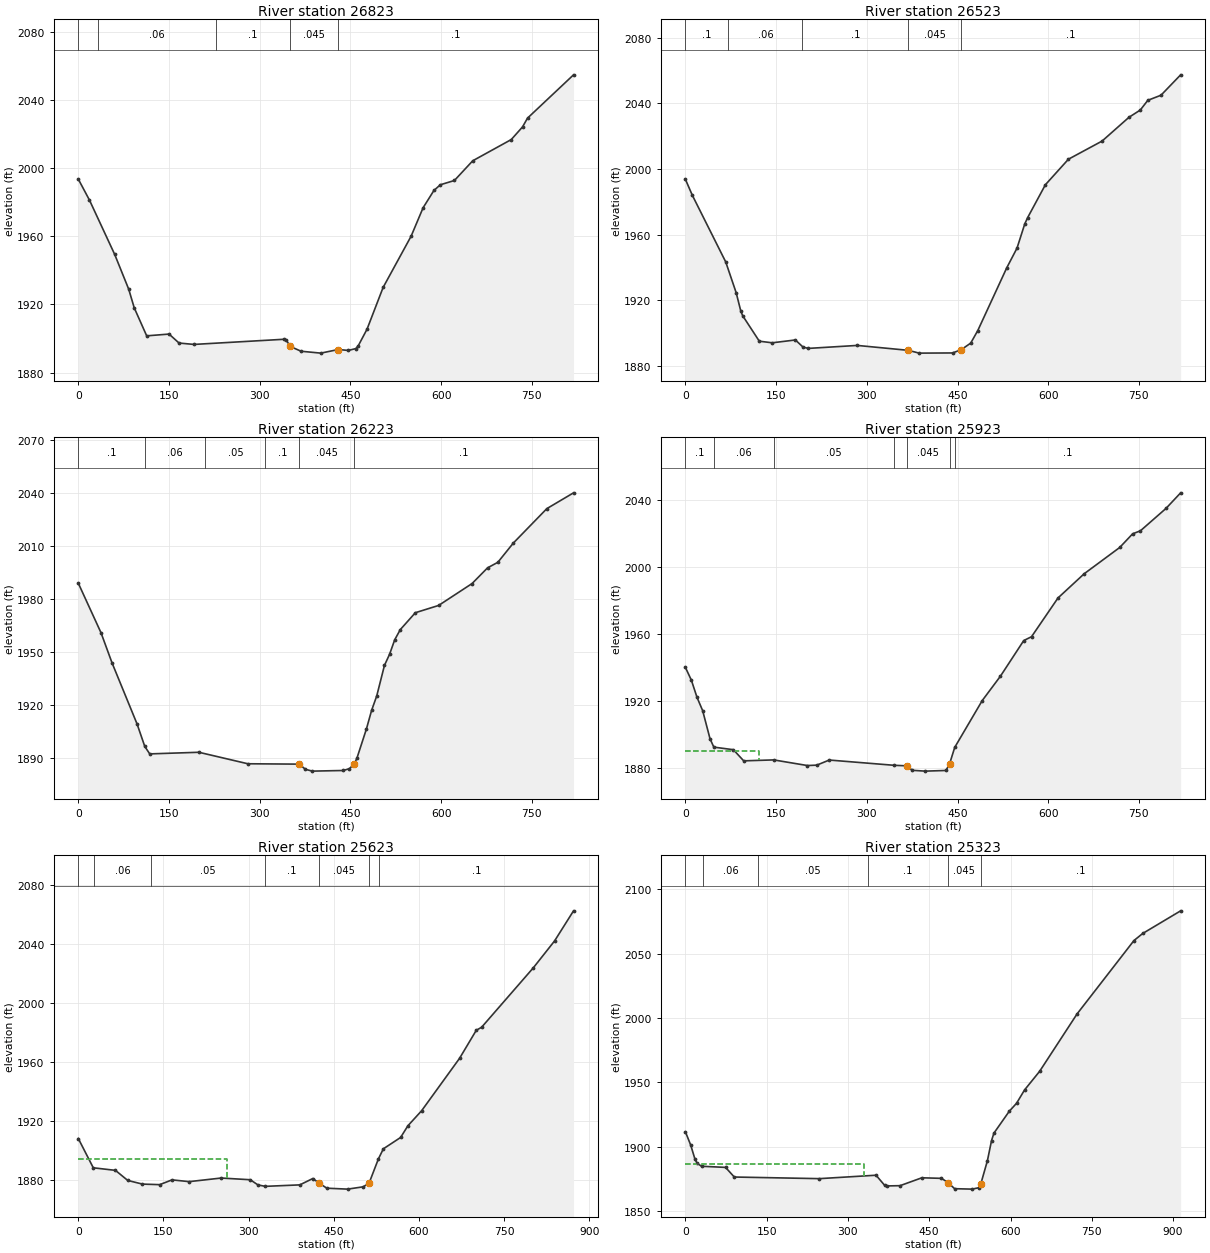
Type RM Length L Ch R = 1 ,26823   ,307,300,298.6
XS GIS Cut Line= 3
     2411445.513      681660.792     2411348.889      681262.855
     2411252.264      680864.918
#Sta/Elev= 30
       0 1993.58    18.4 1981.31    60.2 1949.37    83.4 1928.93    92.5 1918.03
   113.1 1901.58   150.1 1902.63   166.6 1897.36   191.3 1896.55   339.5 1899.56
   343.6 1899.19   350.8 1895.34   368.3 1892.55   401.1 1891.44     430 1893.56
   446.5 1893.02   458.9  1894.1     463 1895.78   477.5  1905.5   504.1 1930.02
   550.4  1960.1   570.2 1976.78   588.1 1986.94   598.8 1990.29     622 1992.79
   652.3 2004.36     716 2016.82   734.6 2024.22   742.9  2029.4     819 2054.82
#Mann= 5 ,-1 , 0
       0      .1       0   31.88     .06       0  227.65      .1       0
   350.8    .045       0     430      .1       0
Bank Sta=350.8,430
XS Rating Curve= 0 ,0
Exp/Cntr=0.3,0.1

Type RM Length L Ch R = 1 ,26523   ,300,300,300
XS GIS Cut Line= 3
     2411773.616      681549.624     2411632.272      681165.291
     2411490.928      680780.957
#Sta/Elev= 30
       0 1993.75    11.4 1984.06    66.7 1943.41    83.9 1924.73    91.6 1913.53
    94.7 1910.67   122.2 1895.16   143.6 1894.18   181.9 1895.91   194.4  1891.6
   203.2 1890.77   284.2 1892.58   368.9 1889.58   386.5 1887.89   441.9    1888
   456.2 1890.02   471.8 1893.98   483.5 1901.63   531.4 1939.85   548.4 1951.86
   561.2  1966.6     566 1970.45   595.3 1990.45   633.4    2006   689.1 2017.06
   733.5 2031.53   752.2 2035.94   764.7 2041.87   786.5 2044.98     819  2057.4
#Mann= 5 ,-1 , 0
       0      .1       0   71.23     .06       0  193.13      .1       0
   368.9    .045       0   456.2      .1       0
Bank Sta=368.9,456.2
XS Rating Curve= 0 ,0
Exp/Cntr=0.3,0.1

Type RM Length L Ch R = 1 ,26223   ,300.7,300,300
XS GIS Cut Line= 3
     2412055.179      681446.075     2411913.835      681061.742
      2411772.49      680677.408
#Sta/Elev= 30
       0 1989.17    37.5 1961.15    55.8 1944.03    97.2 1909.42   109.9 1896.75
   118.1 1892.49   199.4 1893.41   280.4  1886.9   365.7 1886.69   375.4 1883.77
     387 1882.73   438.1 1883.09   448.4 1884.14   456.3 1886.75   460.9 1890.19
   476.5 1906.64     485 1917.09   493.5 1925.29   506.3 1942.62   514.8 1948.95
   523.3 1957.15   532.5 1962.89   557.4 1972.46   595.8 1976.56   651.2 1988.98
   676.8 1997.87   693.8    2001   719.5 2011.94   774.8  2031.4     819 2040.36
#Mann= 6 ,-1 , 0
       0      .1       0  110.46     .06       0  209.94     .05       0
  309.43      .1       0   365.7    .045       0   456.3      .1       0
Bank Sta=365.7,456.3
XS Rating Curve= 0 ,0
Exp/Cntr=0.3,0.1

Type RM Length L Ch R = 1 ,25923   ,301,300,300
XS GIS Cut Line= 3
     2412341.649      681336.822     2412194.126      680954.818
     2412046.602      680572.815
#Sta/Elev= 30
       0 1939.94     9.9 1932.26    19.2    1922    28.5 1914.08    40.7 1897.22
      47 1892.21    79.3 1890.67    96.4 1883.99     146 1884.56   201.7 1881.19
   217.2 1881.42   237.9 1884.48   345.1 1881.33   366.5 1881.01   375.1 1878.33
   396.5 1877.84   430.9 1878.23   436.8 1882.12   445.4 1892.08   490.9 1920.11
   520.9 1934.66   559.5 1956.02   572.4 1958.34   616.2 1981.55   659.5 1996.04
   718.2 2011.76   739.6 2019.95   752.5 2021.76   794.7 2035.13     819 2044.49
#Mann= 7 ,-1 , 0
       0      .1       0      47     .06       0     146     .05       0
   345.1      .1       0   366.5    .045       0   436.8      .1       0
   445.4      .1       0
#XS Ineff= 2 , 0
           122.1    1890
Permanent Ineff=
       F       F
Bank Sta=366.5,436.8
XS Rating Curve= 0 ,0
Exp/Cntr=0.3,0.1

Type RM Length L Ch R = 1 ,25623   ,287.2,300,321.3
XS GIS Cut Line= 3
2412649.88276596681271.321787249     2412472.814      680843.817
     2412316.714      680465.237
#Sta/Elev= 30
       0 1907.92    26.4 1888.02    65.4 1886.28    87.1 1879.42     113 1876.94
   143.3 1876.56     165 1879.81   195.3 1878.61   251.6 1881.06   302.8  1879.9
   316.5 1876.36   329.5 1875.41   390.1 1876.41     413 1880.72   423.7 1877.72
   437.7 1874.15   474.2 1873.52   501.8 1875.09   512.2 1877.68   528.6 1894.13
   537.3 1900.94   567.6 1908.63   580.5  1916.6   604.6 1926.79   671.4  1962.4
   700.9  1981.5   710.3 1983.56   801.2 2023.89   838.8 2042.24   872.2  2062.7
#Mann= 7 ,-1 , 0
       0      .1       0   27.72     .06       0   128.1     .05       0
  328.86      .1       0   423.7    .045       0   512.2      .1       0
   529.6      .1       0
#XS Ineff= 2 , 0
          261.98 1894.25
Permanent Ineff=
       F       F
Bank Sta=423.7,512.2
XS Rating Curve= 0 ,0
Exp/Cntr=0.3,0.1

Type RM Length L Ch R = 1 ,25323   ,298.3,300,303.8
XS GIS Cut Line= 3
2412701.97610637681268.482765984     2412758.973      680766.065
     2412814.664      680361.483
#Sta/Elev= 30
       0 1911.55     9.7 1901.33    17.7 1890.23    21.7 1887.06    29.8 1884.81
    74.1 1883.92    90.2 1876.44   247.2 1875.18   351.8 1877.84   367.9 1869.89
     372 1869.53   396.1 1869.72   436.4 1875.85   472.6 1875.41   484.7 1872.15
   496.8 1867.38     529 1867.04   541.1 1868.09   545.2 1871.16   557.3 1889.02
     565 1904.78   569.4 1910.55   597.7 1927.53   611.2 1933.76   625.9 1944.07
   653.8 1958.58   722.8 2003.11   827.8 2060.11     844 2065.62     914  2083.2
#Mann= 6 ,-1 , 0
       0      .1       0   33.31     .06       0  134.44     .05       0
  336.69      .1       0   484.7    .045       0   545.2      .1       0
#XS Ineff= 2 , 0
           328.9 1886.73
Permanent Ineff=
       F       F
Bank Sta=484.7,545.2
XS Rating Curve= 0 ,0
Exp/Cntr=0.3,0.1

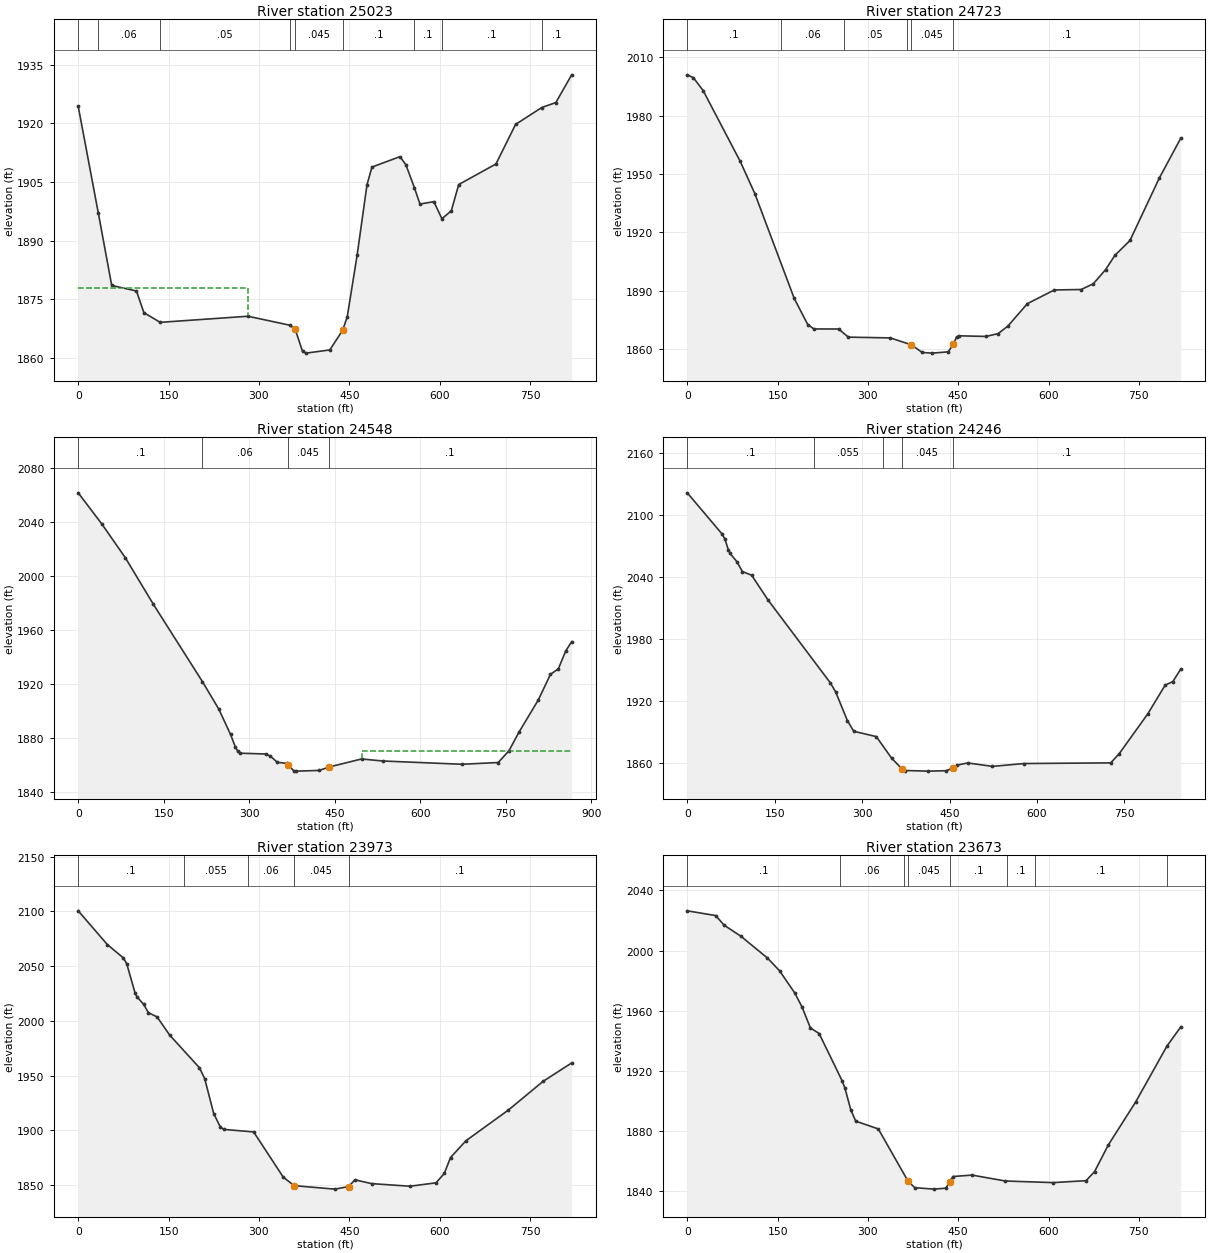
Type RM Length L Ch R = 1 ,25023   ,301.3,300,297.7
XS GIS Cut Line= 3
     2412956.687      681224.916     2413052.465      680826.774
     2413148.244      680428.632
#Sta/Elev= 30
       0 1924.33    33.2 1897.19    55.6 1878.59    96.7 1877.16     109 1871.64
     136 1869.16   281.8 1870.72   350.8 1868.44     360 1867.44   372.4 1861.72
   378.1  1861.3   417.6 1862.12   438.8 1867.12   446.4  1870.5   462.9  1886.3
   479.3 1904.31   487.5 1908.81     534 1911.48   543.9 1909.39   557.9 1903.57
   567.2 1899.37   590.3 1899.98   603.6 1895.62   619.2 1897.63   631.5 1904.35
   693.3  1909.6   725.9 1919.71   769.2 1924.01   792.7 1925.29     819 1932.37
#Mann= 9 ,-1 , 0
       0      .1       0    33.2     .06       0     136     .05       0
   350.8      .1       0     360    .045       0   438.8      .1       0
   557.9      .1       0   603.6      .1       0   769.2      .1       0
#XS Ineff= 2 , 0
           281.7    1878
Permanent Ineff=
       F       F
Bank Sta=360,438.8
XS Rating Curve= 0 ,0
Exp/Cntr=0.3,0.1

Type RM Length L Ch R = 1 ,24723   ,174.1,175.1,176.8
XS GIS Cut Line= 3
     2413259.054      681296.624     2413344.312      680896.203
     2413411.998      680491.743
#Sta/Elev= 30
       0 2001.05      10 1999.62    26.3 1992.97    87.7 1956.63   112.2  1939.9
   177.6 1885.94   200.1 1872.47   210.3 1870.22   251.2 1870.19   267.6    1866
   337.1 1865.61   371.6 1862.11   390.3 1858.11   406.6 1857.77   433.5 1858.44
   442.1 1862.48   447.2 1866.05   451.3 1866.69   495.9 1866.36   516.2 1867.81
   532.4 1871.68   564.8 1883.24   609.5 1890.29   654.1 1890.52   674.3 1893.47
   694.6 1900.71     710 1908.05   735.2 1915.78   783.8 1947.84   819.5 1968.41
#Mann= 6 ,-1 , 0
       0      .1       0  155.68     .06       0  260.06     .05       0
  364.44      .1       0   371.6    .045       0   442.1      .1       0
Bank Sta=371.6,442.1
XS Rating Curve= 0 ,0
Exp/Cntr=0.3,0.1

Type RM Length L Ch R = 1 ,24548   ,339.7,301.9,268.1
XS GIS Cut Line= 3
     2413424.984      681327.4312413558.11985108680742.923659517
     2413455.673      680497.301
#Sta/Elev= 30
       0 2061.82    41.6 2038.61    82.6 2013.68   131.8 1979.12     218 1921.64
   246.7 1901.25   267.2 1882.52   275.4 1873.45   279.5 1870.33   283.6  1868.6
   328.8 1868.01     337 1866.48   349.3 1861.85   365.7 1861.03   368.1 1860.13
     378 1855.53   382.1 1855.29   422.9  1855.8   439.5  1858.3     497 1864.31
   533.9 1862.82   673.2 1860.38   736.7 1861.68   755.5 1870.33   772.9 1884.03
     807 1908.05   828.4 1927.12   842.2 1931.18   855.2 1944.52   865.6 1951.35
#Mann= 4 ,-1 , 0
       0      .1       0     218     .06       0   368.1    .045       0
   439.5      .1       0
#XS Ineff= 2 , 0
                             497            1870
Permanent Ineff=
       F       F
Bank Sta=368.1,439.5
XS Rating Curve= 0 ,0
Exp/Cntr=0.3,0.1

Type RM Length L Ch R = 1 ,24246   ,264.1,273,277.6
XS GIS Cut Line= 3
     2414064.046      681105.6142413785.86476596680813.804787229
2413493.14861701680480.692808514
#Sta/Elev= 30
       0  2121.7    59.9 2081.64    64.6 2076.79    70.7 2065.97    73.6 2062.89
    84.9 2055.08    94.6 2045.37   110.4 2041.84   138.6 2017.75   245.4 1937.49
   254.6 1928.65   274.6 1900.96   285.6 1890.51   324.3 1885.37   350.8 1864.26
   367.8 1854.42     374 1852.49   413.1 1851.89   444.3 1852.28   455.6 1854.85
   462.4 1857.66   481.1 1859.83   523.6 1856.49   577.5 1859.25   726.5  1859.9
   741.2 1868.94   790.1 1907.44   819.9 1935.29     833 1938.68   846.6 1950.78
#Mann= 5 ,-1 , 0
       0      .1       0  216.63    .055       0  335.41      .1       0
   367.8    .045       0   455.6      .1       0
Bank Sta=367.8,455.6
XS Rating Curve= 0 ,0
Exp/Cntr=0.3,0.1

Type RM Length L Ch R = 1 ,23973   ,299.7,300,299.4
XS GIS Cut Line= 3
     2414207.334      680965.287     2413980.461      680624.379
     2413753.587      680283.471
#Sta/Elev= 30
       0  2100.6    48.3  2069.8      75 2057.55    80.5 2052.32    94.2  2025.8
    97.4 2022.14   108.6 2015.17   116.6 2007.51     131 2003.63   151.8 1987.07
   201.2 1957.22   209.9 1947.28   224.9 1915.37   235.8 1903.15   241.6  1900.9
   291.2 1898.57   340.4  1857.2   358.4  1849.5   425.7 1846.32   448.7 1848.64
   459.3 1854.84   486.8 1851.36   550.6 1848.97   593.9 1852.09   607.5 1860.62
   617.9 1875.21   643.6 1890.57     714  1918.6   771.6 1944.83     819 1961.61
#Mann= 5 ,-1 , 0
       0      .1       0  174.92    .055       0  282.38     .06       0
   358.4    .045       0   448.7      .1       0
Bank Sta=358.4,448.7
XS Rating Curve= 0 ,0
Exp/Cntr=0.3,0.1

Type RM Length L Ch R = 1 ,23673   ,404.6,385.9,372.3
XS GIS Cut Line= 3
     2414454.318      680802.327     2414230.923      680459.253
     2413990.659      680126.915
#Sta/Elev= 30
       0 2026.44    47.1 2023.29    61.4 2016.83    88.9 2009.56     133 1995.07
   153.2 1986.55   178.5 1971.72   190.3 1962.65   204.5 1948.46     219 1944.72
   257.1 1913.29   261.9  1908.3   271.4 1894.07   279.7 1886.38   317.3 1881.16
   366.9 1846.18     378 1842.04   409.8 1841.09   429.6 1841.75   435.6 1845.95
   441.3 1849.49   472.8 1850.44   528.3  1846.5   607.7 1845.43   662.3 1846.73
   676.4 1852.77   699.1 1870.45     745 1899.37   796.5  1936.3   819.5 1949.11
#Mann= 8 ,-1 , 0
       0      .1       0  253.06     .06       0  360.02      .1       0
   366.9    .045       0   435.6      .1       0  531.35      .1       0
  577.86      .1       0  796.86     .05       0
Bank Sta=366.9,435.6
XS Rating Curve= 0 ,0
Exp/Cntr=0.3,0.1

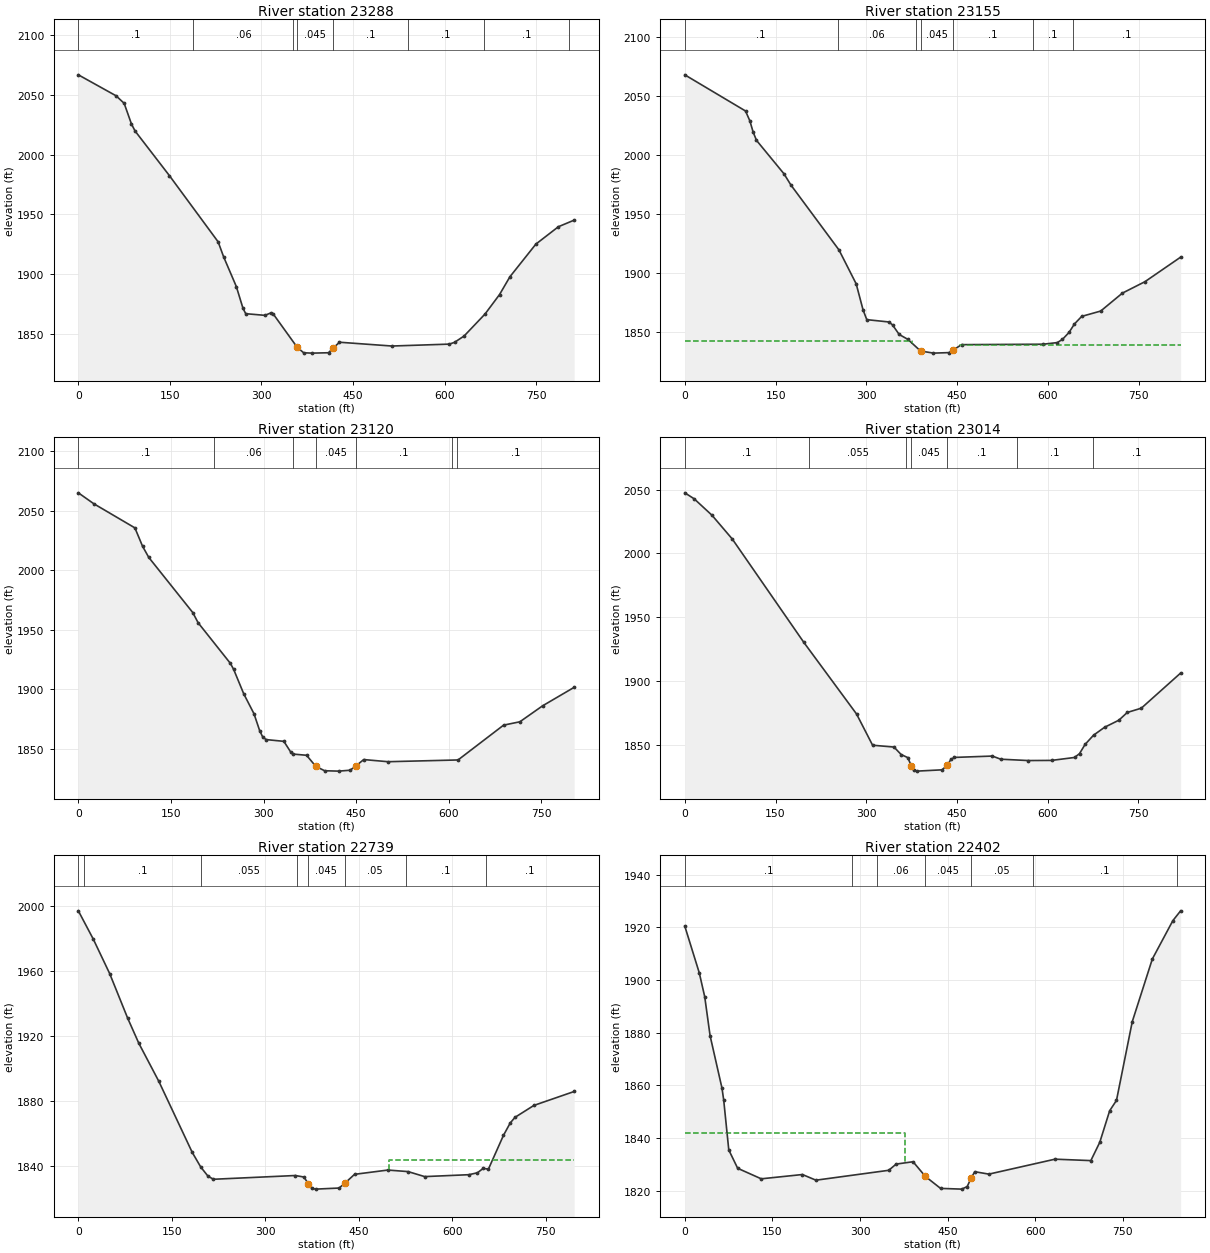
Type RM Length L Ch R = 1 ,23288   ,125.3,132.5,136.9
XS GIS Cut Line= 3
2414793.47056987680333.6048493532414207.58933553680025.700861493
2414093.67891169679927.542264941
#Sta/Elev= 30
       0 2066.99    61.8 2049.43    75.1 2043.09      87 2025.82    92.9 2019.94
   149.2 1982.52     229 1927.04   238.1 1914.35   258.8  1889.6   269.7 1871.37
   274.2 1866.83   305.8 1865.44   314.9  1867.4   319.4  1866.5   358.4 1838.75
   369.1 1834.07   383.2 1833.78   409.8  1834.1   416.7 1837.68   427.8 1842.91
   513.7 1839.73   607.7 1841.33   616.3 1842.83     632 1848.16   666.2 1866.55
     690 1882.88     707  1897.8   749.5 1925.14   786.4 1939.71   812.2 1945.22
#Mann= 8 ,-1 , 0
       0      .1       0  188.52     .06       0  352.28      .1       0
   358.4    .045       0   416.7      .1       0   539.8      .1       0
  664.58      .1       0     804     .05       0
Bank Sta=358.4,416.7
XS Rating Curve= 0 ,0
Exp/Cntr=0.5,0.3

Type RM Length L Ch R = 1 ,23155   ,34.8,35.1,37
XS GIS Cut Line= 3
2414833.07197164680307.3710840622414519.32397164680044.211084062
2414205.57697164679781.052084062
#Sta/Elev= 30
       0 2067.92   100.3 2037.26   107.5 2028.87   112.8 2019.52   118.4 2012.38
   163.8 1984.04   175.3 1974.49   254.7 1919.45   283.1 1890.73   294.4 1868.73
   300.6 1860.38   337.2 1858.41   343.1 1855.93   354.1 1847.82   368.5 1843.66
   389.4 1833.81   410.8    1832   436.4 1832.44   442.7 1834.44   457.2 1839.18
   592.1 1839.56   615.3 1840.94   623.8 1843.66   634.7 1849.57   643.7 1856.77
   655.6 1863.15     687 1867.67   722.8 1882.87   760.1 1892.57     819 1913.36
#Mann= 7 ,-1 , 0
       0      .1       0  252.41     .06       0     382      .1       0
   389.4    .045       0   442.7      .1       0  574.58      .1       0
  641.18      .1       0
#XS Ineff= 2 , 0
             376    1842     455            1839
Permanent Ineff=
       F       F
Bank Sta=389.4,442.7
XS Rating Curve= 0 ,0
Exp/Cntr=0.5,0.3

Type RM Length L Ch R = 1 ,23120   ,113.5,106.2,102
XS GIS Cut Line= 2
2414849.71718991680281.1291897682414239.93785279679758.765771608
#Sta/Elev= 30
       0 2064.93      25 2055.78    91.6 2035.48     104 2020.05   114.1 2010.65
   185.3 1964.36     194 1955.77   246.2 1921.69   251.5 1916.63   267.8 1896.14
   284.5 1879.29   293.6  1865.2   298.7 1859.68   304.1 1857.64   332.8 1856.18
   344.1 1847.03   347.8 1845.48   369.6 1844.46   384.6 1835.09   398.9 1831.47
   421.5 1831.15     440  1831.9   449.1 1835.35   462.1 1840.86   501.5 1839.06
   614.9 1840.53   688.6 1869.77     715  1872.6   751.8 1886.01   802.9 1901.54
#Mann= 7 ,-1 , 0
       0      .1       0  219.37     .06       0   347.8      .1       0
   384.6    .045       0   449.1      .1       0  604.66      .1       0
  613.58      .1       0
Bank Sta=384.6,449.1
XS Rating Curve= 0 ,0
Exp/Cntr(USF)=0,0
Exp/Cntr=0.5,0.3

Type RM Length L Ch R = 1 ,23014   ,272.9,274.5,274.1
XS GIS Cut Line= 3
2414959.82244821680122.8489151572414600.10844821679927.562915157
2414246.84044821679718.490915157
#Sta/Elev= 30
       0 2047.45    15.5 2042.76      45 2029.85    78.6 2011.17   196.9 1930.12
     284 1874.01   310.5 1849.55   345.9  1848.1   357.7 1842.25   368.8  1839.8
   374.4 1833.39   378.4 1830.14   383.5 1829.23   425.4 1830.25     434 1833.91
     440 1838.39   445.8 1839.98   508.5 1841.04   522.4 1838.58   567.7 1837.53
   606.4 1837.63   644.4 1839.94   652.6 1842.94   661.9 1850.22   675.8 1857.39
     694  1863.6   717.7 1869.17   731.6 1875.24   754.8 1878.58   819.8 1906.13
#Mann= 7 ,-1 , 0
       0      .1       0  205.55    .055       0   366.4     .06       0
   374.4    .045       0     434      .1       0  548.59      .1       0
  675.36      .1       0
Bank Sta=374.4,434
XS Rating Curve= 0 ,0
Exp/Cntr=0.3,0.1

Type RM Length L Ch R = 1 ,22739   ,336.7,336.9,337.3
XS GIS Cut Line= 2
2415098.94068184679903.4913696942414412.90338905679500.294013404
#Sta/Elev= 30
       0 1997.09      24 1979.66    50.3 1958.46    79.1 1931.08      97 1915.62
   129.2 1892.11   182.8 1848.39   196.4 1839.41   208.1 1833.75   216.8 1831.85
   348.3 1834.16   362.1 1833.22   368.8 1829.19   374.6 1826.29   380.7 1825.78
   418.5 1826.45   427.5 1829.35   443.3 1834.89   496.7 1837.52   529.2 1836.57
   555.8 1833.49   626.6 1834.66   640.5 1835.84   649.8 1838.58   658.1 1838.09
   682.3 1858.92   693.1  1866.5   700.8 1869.98   731.1 1877.31   795.7 1885.88
#Mann= 8 ,-1 , 0
       0      .1       0    9.51      .1       0   196.4    .055       0
  350.47     .06       0   368.8    .045       0   427.5     .05       0
  525.49      .1       0  654.48      .1       0
#XS Ineff= 2 , 0
                          499.16         1843.67
Permanent Ineff=
       F       F
Bank Sta=368.8,427.5
XS Rating Curve= 0 ,0
Exp/Cntr(USF)=0,0
Exp/Cntr=0.3,0.1

Type RM Length L Ch R = 1 ,22402   ,106.6,108.8,112.1
XS GIS Cut Line= 2
2415304.14824987679632.5613272742414571.28219844679204.112467016
#Sta/Elev= 30
       0 1920.42    24.8  1902.7    34.1 1893.66    43.3 1878.87    63.7 1858.95
    66.6 1854.48    75.3 1835.55    90.5 1828.59   130.9 1824.59   201.4 1826.22
   224.5 1824.07   349.1 1827.82   361.9 1830.18   390.8 1831.07     412 1825.47
   437.9 1820.96   474.2 1820.68   483.5 1821.66   490.1 1824.83   496.4 1827.29
   520.6 1826.37   633.8 1832.04   695.2  1831.5   710.5 1838.45   727.4  1850.4
   739.1 1854.35   766.1  1884.2   800.5 1907.98   835.6 1922.52   848.9 1926.24
#Mann= 7 ,-1 , 0
       0      .1       0  286.32    .055       0   328.3     .06       0
     412    .045       0   490.1     .05       0  595.33      .1       0
  843.29      .1       0
#XS Ineff= 2 , 0
          377.82 1841.82
Permanent Ineff=
       F       F
Bank Sta=412,490.1
XS Rating Curve= 0 ,0
Exp/Cntr=0.5,0.3

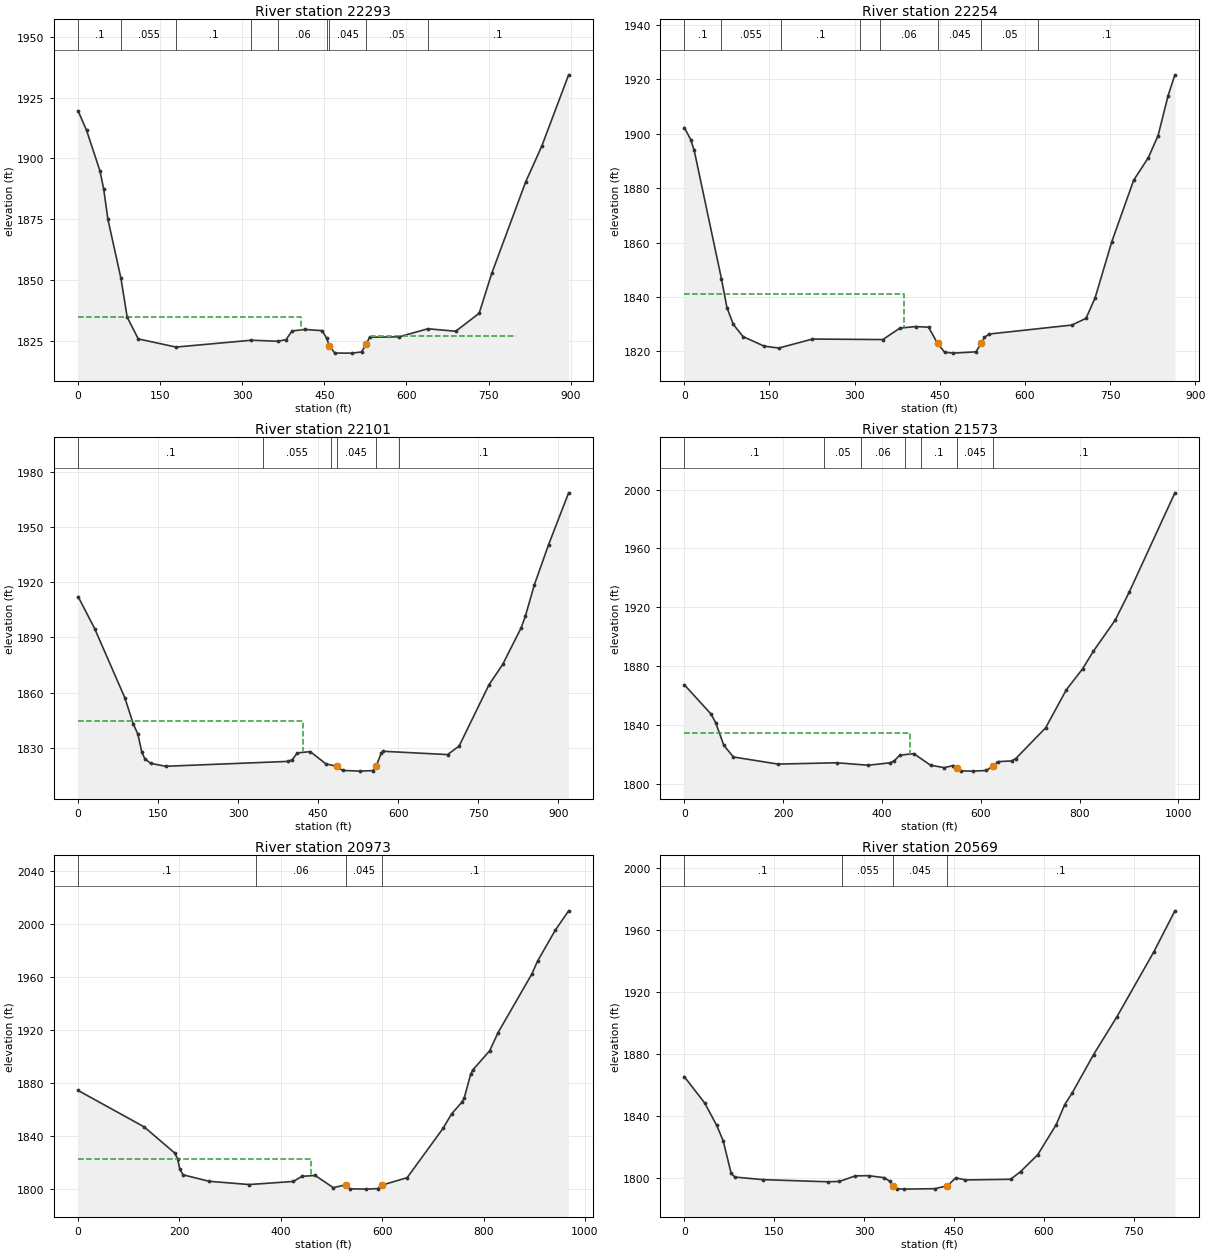
Type RM Length L Ch R = 1 ,22293   ,39.5,39.6,40.1
XS GIS Cut Line= 3
2415371.52962763679591.1781112552414972.07398218679312.845469377
2414638.90198218679074.755469377
#Sta/Elev= 30
       0 1919.61    15.6 1911.52      40 1894.89    46.7 1887.56    54.6 1874.92
    78.3 1850.75    89.8  1834.7     110  1825.8   178.9 1822.44   316.8 1825.26
   365.7 1824.83     380  1825.5     391 1829.08   414.5 1829.67   446.1  1829.2
   454.4 1825.98   459.2 1822.91   469.1 1819.98   500.7 1819.95     518 1820.44
   526.5 1823.61   532.7 1826.48   586.7 1826.65   639.2 1829.97   690.1 1828.95
   732.9 1836.32   755.9 1852.73   817.9 1890.35   847.4 1905.11   896.4  1934.4
#Mann= 9 ,-1 , 0
       0      .1       0    78.3    .055       0   178.9      .1       0
   316.8    .055       0   365.7     .06       0   454.4      .1       0
   459.2    .045       0   526.5     .05       0   639.2      .1       0
#XS Ineff= 3 ,-1
       0     408    1835     408     441    1826     536     800    1827
Permanent Ineff=
       F       F       F
Bank Sta=459.2,526.5
XS Rating Curve= 0 ,0
Exp/Cntr=0.5,0.3

Type RM Length L Ch R = 1 ,22254   ,149.4,152.7,156.9
XS GIS Cut Line= 2
2415383.86790224679558.0054611232414680.31860487679055.934484474
#Sta/Elev= 30
       0 1902.19    11.2 1897.79    17.4 1893.79    65.3 1846.75    75.1 1836.09
    86.2 1829.95   103.4 1825.46   140.7 1821.94   166.5 1821.25   225.7 1824.55
   349.7 1824.36   379.8 1828.56   407.4 1829.14   430.3 1828.91   446.1 1822.94
   458.4 1819.77   473.1 1819.38   513.5 1819.85   523.4 1822.97   528.7 1825.15
     537 1826.39   682.7 1829.69   707.7 1832.15   723.7 1839.67   753.2 1860.33
   791.6 1882.85   817.5 1891.15   834.7 1899.29   852.3 1913.93   864.3 1921.57
#Mann= 8 ,-1 , 0
       0      .1       0   64.63    .055       0   170.7      .1       0
  310.24    .055       0  344.18     .06       0   446.1    .045       0
   523.4     .05       0  623.74      .1       0
#XS Ineff= 2 , 0
          387.06  1841.1
Permanent Ineff=
       F       F
Bank Sta=446.1,523.4
XS Rating Curve= 0 ,0
Exp/Cntr(USF)=0,0
Exp/Cntr=0.5,0.3

Type RM Length L Ch R = 1 ,22101   ,526.5,527.7,528.9
XS GIS Cut Line= 3
2415468.29329508679497.2052323172415086.61583048679159.024313819
2414778.32483048678889.493313819
#Sta/Elev= 30
       0 1912.27    31.1 1894.83    87.6 1857.25   103.6 1842.89   112.1 1837.42
   119.6 1827.51     125 1824.18   135.9 1821.56   164.3 1819.97   393.8 1822.63
   401.6 1823.59   410.8 1827.23     435 1827.94   464.6 1821.27   484.4 1819.98
   495.8 1817.71   528.4 1817.33   552.5 1817.61   558.8 1820.19   568.2 1827.07
   572.3 1828.12   692.5 1826.33   714.1 1830.93   770.1 1864.25   795.8 1875.34
   830.3 1895.18   838.3 1901.54   855.1 1918.56   881.7 1940.36   919.4 1968.66
#Mann= 6 ,-1 , 0
       0      .1       0  347.01    .055       0  473.64      .1       0
   484.4    .045       0   558.8     .05       0  600.77      .1       0
#XS Ineff= 2 , 0
           421.2 1844.74
Permanent Ineff=
       F       F
Bank Sta=484.4,558.8
XS Rating Curve= 0 ,0
Exp/Cntr=0.3,0.1

Type RM Length L Ch R = 1 ,21573   ,582.6,600,621.2
XS GIS Cut Line= 3
2415848.68519869679157.399198685     2415425.675      678755.477
     2415125.762      678476.653
#Sta/Elev= 30
       0 1867.44    54.1 1847.54    63.4 1841.75    79.9 1826.35    99.3 1818.42
   189.5 1813.59   308.7 1814.48   372.4 1812.81   415.9 1814.44   424.7 1815.75
     436  1819.6   464.3 1820.72   498.3 1812.84   526.6 1811.15   543.7 1812.62
     552 1811.13   560.5 1808.99   583.5 1808.81   611.5 1809.24   625.6 1812.53
   634.1 1815.23   662.4 1815.74   670.9 1817.35   731.2 1838.16   773.2 1864.01
     806 1878.21   827.8 1890.15   871.9 1911.23   900.2 1930.12     993 1997.79
#Mann= 7 ,-1 , 0
       0      .1       0  283.46     .05       0  356.75     .06       0
  447.52    .055       0  479.91      .1       0     552    .045       0
   625.6      .1       0
#XS Ineff= 2 , 0
          455.85 1834.85
Permanent Ineff=
       F       F
Bank Sta=552,625.6
XS Rating Curve= 0 ,0
Exp/Cntr=0.3,0.1

Type RM Length L Ch R = 1 ,20973   ,409.8,404.8,398.7
XS GIS Cut Line= 3
2416076.00609577 678992.47965615     2415928.431      678454.214
     2415812.103      678061.554
#Sta/Elev= 30
       0 1874.24   130.2 1846.71   191.1 1826.74   196.6 1822.16   200.7 1814.48
   207.4 1810.36   258.8 1805.48   337.6 1803.03   424.7 1805.37   441.3 1809.23
   467.8 1809.89   503.5 1800.66   528.4 1802.88   536.7 1799.81   568.6 1799.56
   590.8 1799.94   599.1 1802.54   649.2 1808.24   719.9 1845.51   736.8 1856.52
   757.7 1865.57   761.8 1868.63   774.4 1886.39   778.5  1889.7   811.9 1904.22
   828.6 1918.06   895.3 1962.45   906.5 1972.18   941.2 1995.41   967.7 2010.17
#Mann= 4 ,-1 , 0
       0      .1       0  351.81     .06       0   528.4    .045       0
   599.1      .1       0
#XS Ineff= 2 , 0
          459.71 1822.39
Permanent Ineff=
       F       F
Bank Sta=528.4,599.1
XS Rating Curve= 0 ,0
Exp/Cntr=0.3,0.1

Type RM Length L Ch R = 1 ,20569   ,144.2,140.9,137.3
XS GIS Cut Line= 3
2416459.68593666678637.6674723462416286.84893666678266.429472346
2416114.01293666677895.190472346
#Sta/Elev= 30
       0 1865.39    33.9 1848.48      54 1834.05    64.8 1824.15    78.1 1803.25
    84.1 1800.76     131 1799.09   239.2 1797.72     259 1797.95   285.4 1801.51
   307.5 1801.66     334 1800.31     343 1798.01     349 1795.22     355 1793.25
   367.1 1792.98   417.8 1793.26   439.3 1795.14   453.1 1800.25   469.4  1798.9
   544.7 1799.32   561.4 1804.29   589.9  1815.1   620.8 1834.47     635 1847.38
   647.3 1854.76   683.2 1879.62   722.3 1904.04     784 1945.87     819 1972.18
#Mann= 4 ,-1 , 0
       0      .1       0  263.31    .055       0     349    .045       0
   439.3      .1       0
Bank Sta=349,439.3
XS Rating Curve= 0 ,0
Exp/Cntr=0.5,0.3