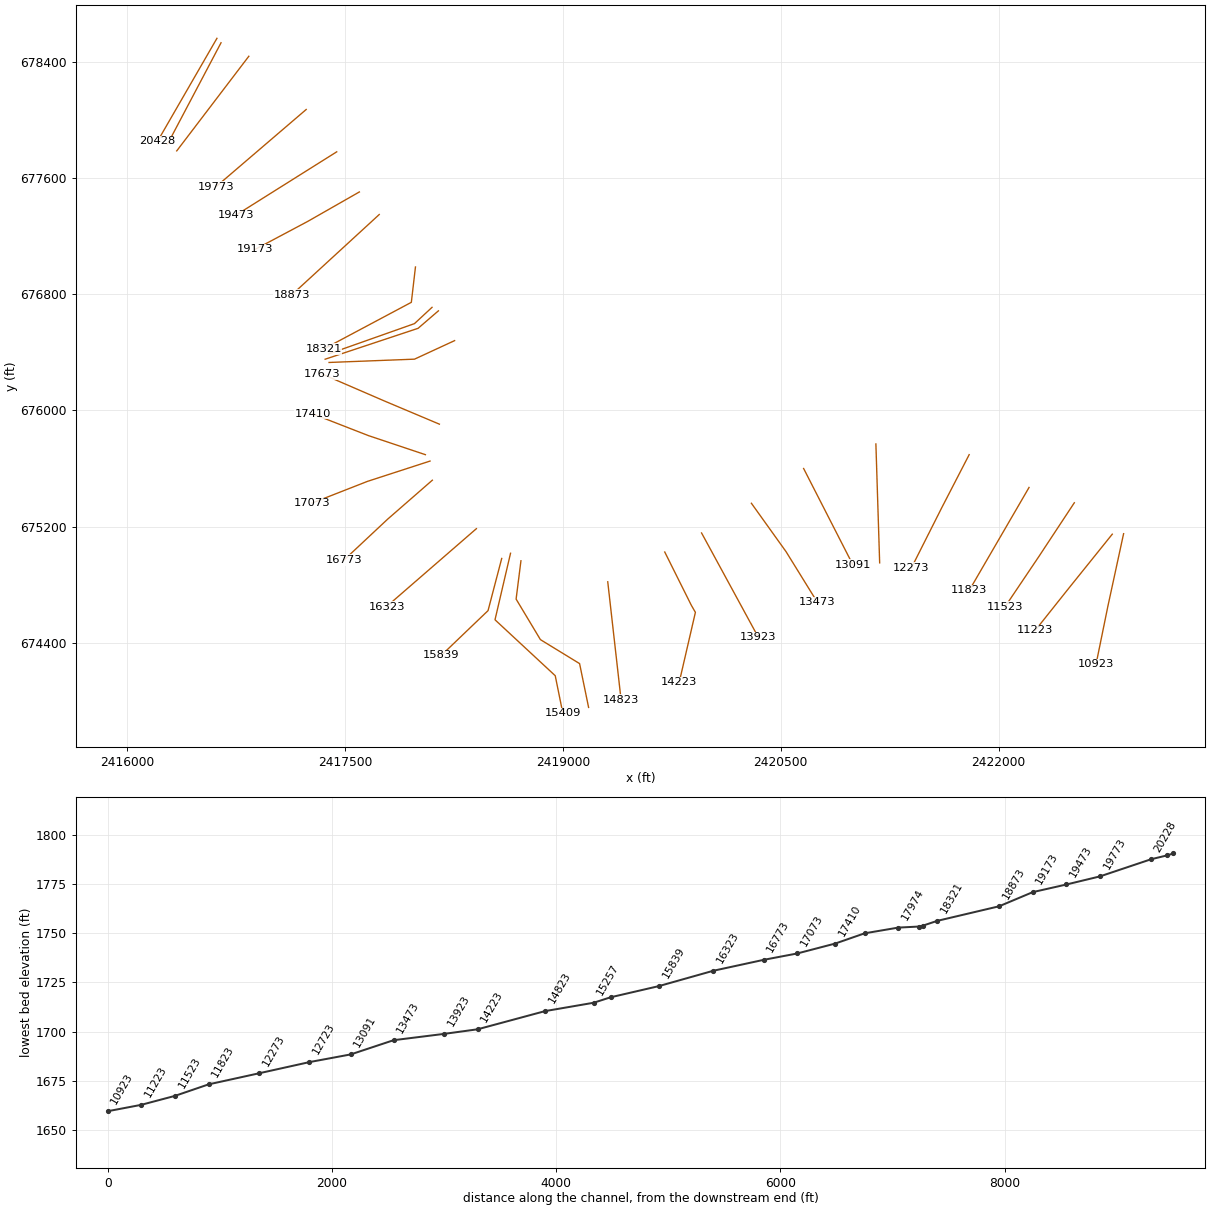
HEC-RAS study SENECACK.prj: SENECACK

--- SENECACK.g03 (geometry) --- (continued)

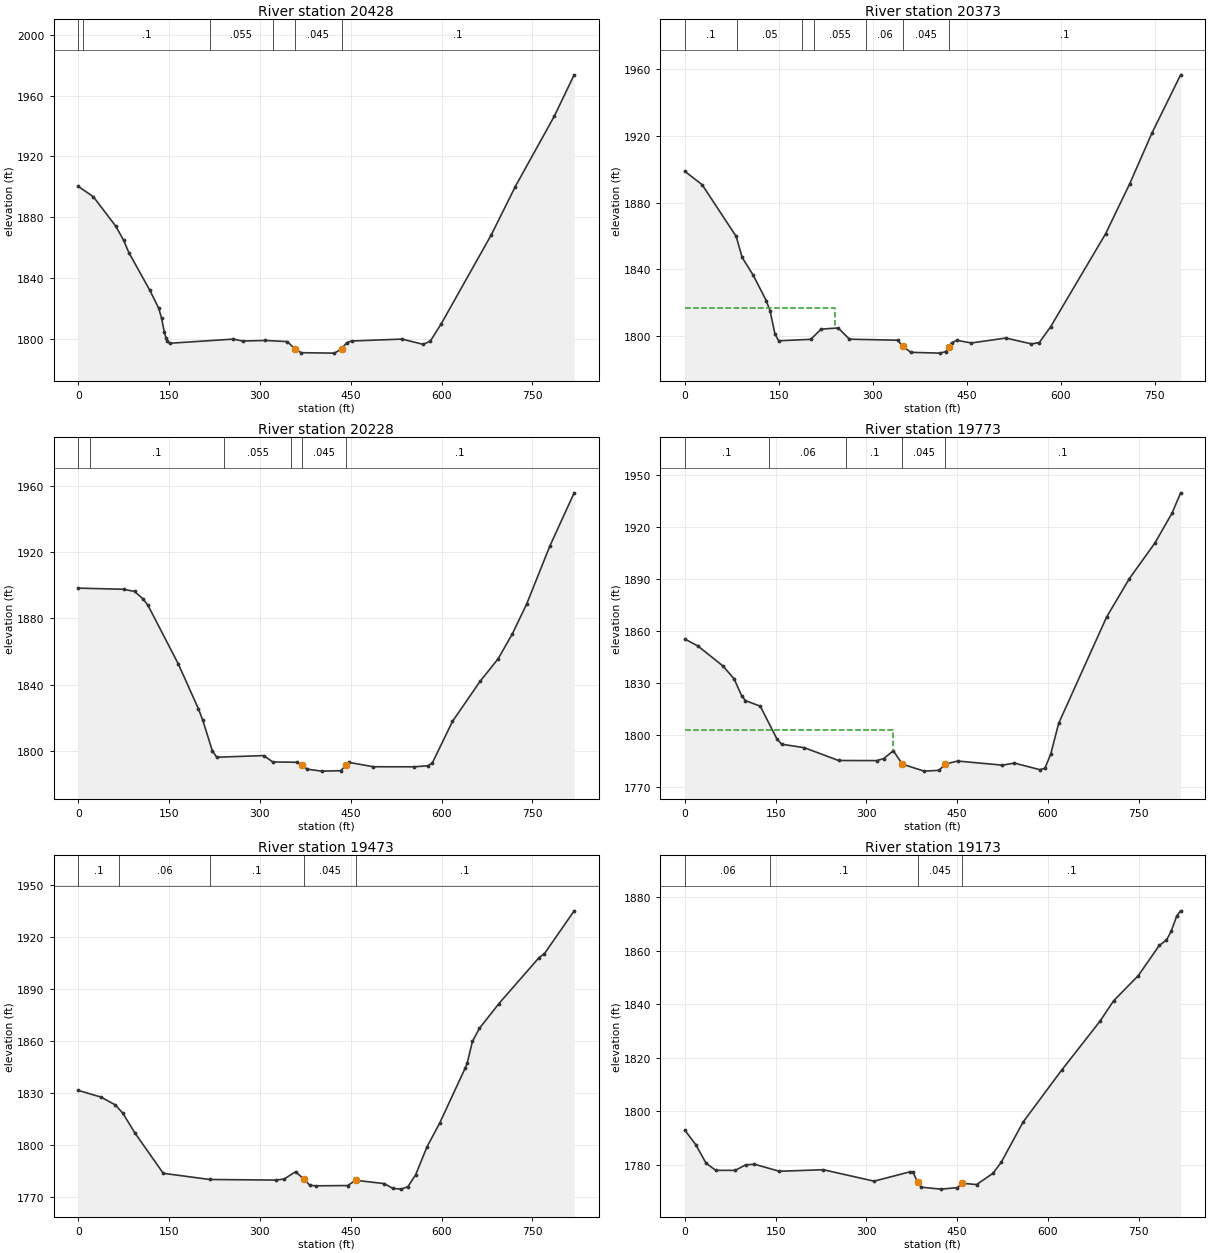
Type RM Length L Ch R = 1 ,20428   ,52.8,54.3,55.6
XS GIS Cut Line= 3
2416617.71665818678561.8868124672416413.06465818678207.193812467
2416208.41165818677852.499812467
#Sta/Elev= 30
       0 1900.28    24.9 1893.49      62 1874.03    74.7 1864.94    83.4 1856.81
     118 1832.05   132.8 1820.14   137.4 1813.74     142 1804.58   144.9 1800.45
   146.6 1798.57   150.8 1797.13   256.2 1799.87   271.3 1798.59   308.9 1798.98
   345.2  1798.2   358.1 1793.31   368.3 1790.92   423.1 1790.64   434.8 1793.45
   443.6 1797.59   451.4 1798.62   534.5 1799.87   569.6 1796.43   581.3  1798.5
   599.2 1809.77   682.3  1868.6   721.8 1900.22   786.3 1946.58     819  1973.7
#Mann= 6 ,-1 , 0
       0     .05       0    7.77      .1       0  216.94    .055       0
  321.52     .06       0   358.1    .045       0   434.8      .1       0
#XS Ineff= 2 , 0
             325    1797     454            1797
Permanent Ineff=
       F       F
Bank Sta=358.1,434.8
XS Rating Curve= 0 ,0
Exp/Cntr=0.5,0.3

Type RM Length L Ch R = 1 ,20373   ,152.2,145.5,140.2
XS GIS Cut Line= 2
2416645.98943728678531.4033414342416276.42620266677831.365291245
#Sta/Elev= 30
       0 1898.86    27.7  1890.8      82 1859.76    91.6  1847.1   109.4 1836.33
   130.1 1821.16     136 1815.22     144 1801.11   149.8 1797.08   201.1 1797.96
   217.7 1804.07   244.8 1804.79   262.9 1798.04   339.8 1797.43     348 1793.73
     361 1790.15   407.7 1789.67   416.7 1790.61   421.2 1793.23   426.1 1795.98
   434.8 1797.34   457.4 1795.77   512.5 1798.73   553.4 1795.22     566 1796.02
   584.1 1805.54   671.8 1861.34   710.3 1891.34   745.8 1921.81   791.6 1956.77
#Mann= 7 ,-1 , 0
       0      .1       0   83.55     .05       0  186.71     .06       0
   205.6    .055       0  289.87     .06       0     348    .045       0
   421.2      .1       0
#XS Ineff= 2 , 0
          239.84 1816.48
Permanent Ineff=
       F       F
Bank Sta=348,421.2
XS Rating Curve= 0 ,0
Exp/Cntr(USF)=0,0
Exp/Cntr=0.5,0.3

Type RM Length L Ch R = 1 ,20228   ,464.3,454.5,449.3
XS GIS Cut Line= 3
2416837.22202855678438.4189121332416589.06602855678112.674912133
2416340.91002855677786.930912133
#Sta/Elev= 30
       0 1898.35    74.8 1897.67    92.8 1896.35     107 1891.82   115.1  1887.9
   165.3 1852.38   198.4 1825.33   205.6  1818.4   221.2 1800.11   228.5 1796.08
   306.1 1797.06   321.2 1793.22   361.5 1793.02   369.6 1791.24   378.2 1788.85
   401.7 1787.66   433.1  1787.9   441.9 1791.09   446.9 1792.96   487.2 1790.31
   555.1 1790.27     578 1790.94   584.9 1792.73   617.9 1817.69   663.6 1841.98
   693.3 1855.55     717 1870.79   740.7 1888.88   778.8 1923.78     819 1956.01
#Mann= 6 ,-1 , 0
       0     .05       0   18.75      .1       0  240.66    .055       0
  351.62      .1       0   369.6    .045       0   441.9      .1       0
Bank Sta=369.6,441.9
XS Rating Curve= 0 ,0
Exp/Cntr=0.3,0.1

Type RM Length L Ch R = 1 ,19773   ,306.8,300,296.8
XS GIS Cut Line= 3
     2417232.347      678072.012     2416921.286      677805.682
     2416610.225      677539.353
#Sta/Elev= 30
       0  1855.3    21.8 1851.24    63.2 1839.66    81.4 1832.28      94 1822.47
   100.1 1819.73   124.7 1816.47   152.3 1797.47   160.1 1794.52   197.7 1792.47
   253.9 1785.11   316.8 1785.04   328.6  1786.2   344.4 1790.74   359.4 1782.99
   395.3 1778.96   419.9 1779.41   430.3 1783.06   450.7 1784.79   524.5 1782.42
   544.5 1783.61   586.3 1779.81   594.8 1780.57   604.5 1788.86   617.5 1806.55
   696.7 1867.97   734.1 1890.09   776.7 1910.86   804.8 1928.03     819 1939.77
#Mann= 5 ,-1 , 0
       0      .1       0  138.62     .06       0  267.07      .1       0
   359.4    .045       0   430.3      .1       0
#XS Ineff= 2 , 0
          343.94 1802.61
Permanent Ineff=
       F       F
Bank Sta=359.4,430.3
XS Rating Curve= 0 ,0
Exp/Cntr=0.3,0.1

Type RM Length L Ch R = 1 ,19473   ,301.9,300,296.4
XS GIS Cut Line= 3
     2417442.549      677780.526     2417095.821      677562.651
     2416749.092      677344.775
#Sta/Elev= 30
       0 1831.75    37.6 1827.89    61.2 1823.38    73.6 1818.56    93.9 1806.97
   140.3 1783.95   217.1 1780.38     326 1780.04   339.9 1780.62   358.8 1784.88
     373 1780.44   382.4 1777.06   391.9 1776.73   444.9 1776.88     458 1779.92
   505.3 1778.01   519.4 1775.25   533.6 1774.82   544.4 1776.25   557.2 1783.11
   576.1 1799.36     597    1813   639.3 1844.84   642.3 1847.48   650.9 1859.97
   662.5 1867.54   694.7 1881.83   761.1 1908.39   769.9 1910.64     819 1935.34
#Mann= 5 ,-1 , 0
       0      .1       0   67.98     .06       0  216.72      .1       0
     373    .045       0     458      .1       0
Bank Sta=373,458
XS Rating Curve= 0 ,0
Exp/Cntr=0.3,0.1

Type RM Length L Ch R = 1 ,19173   ,294.3,300,311.9
XS GIS Cut Line= 3
     2417598.401      677504.237     2417242.541      677301.171
     2416881.001      677108.953
#Sta/Elev= 30
       0    1793      18 1787.61      35 1780.69    51.1 1777.96    83.4 1777.96
   100.4 1780.01   115.1 1780.25   156.1 1777.62   228.7  1778.2   312.8 1773.92
   372.6 1777.45   377.2 1777.18   384.9 1773.42   390.7 1771.67   423.1 1770.94
   450.3 1771.49   458.6 1773.13     482 1772.64   508.9 1776.81   522.7 1780.94
     559 1796.05   622.4 1815.37   685.8 1833.67   708.5 1841.37   749.3 1850.79
   783.9 1862.06   795.8 1864.07   803.6 1867.36   812.7 1873.03   819.2 1875.01
#Mann= 4 ,-1 , 0
       0     .06       0  141.41      .1       0   384.9    .045       0
   458.6      .1       0
Bank Sta=384.9,458.6
XS Rating Curve= 0 ,0
Exp/Cntr=0.3,0.1

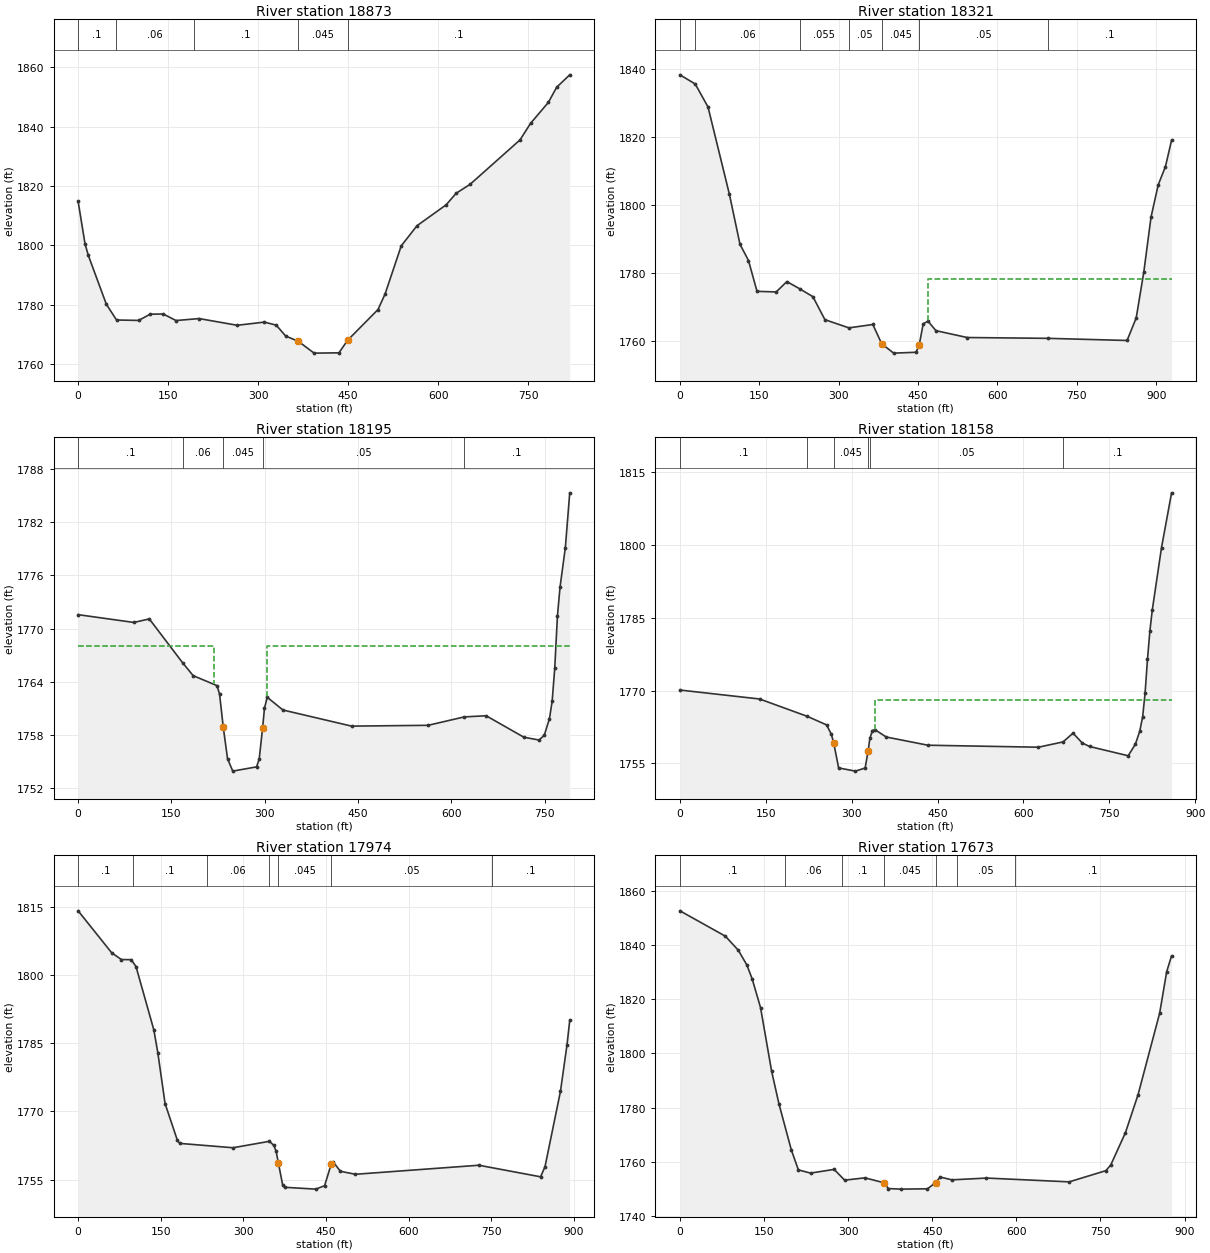
Type RM Length L Ch R = 1 ,18873   ,560.8,552.2,542.9
XS GIS Cut Line= 3
      2417735.23      677348.783     2417433.601      677071.817
     2417131.973      676794.851
#Sta/Elev= 30
       0 1814.86    11.5 1800.58    16.9 1796.71      47 1780.21      64  1774.9
   100.8 1774.76   120.1 1776.86   141.9 1776.92     163 1774.72   201.6 1775.38
     265 1773.12   310.3 1774.19   330.1 1773.16   345.8 1769.49   366.9 1767.72
   393.1 1763.74   434.5 1763.84     449 1768.08   499.6 1778.43   511.3 1783.63
   538.3 1799.88   564.6 1806.67   613.2 1813.71   629.7 1817.59   652.8 1820.57
   736.1 1835.56   753.9 1841.18   783.5 1848.23   797.2 1853.31     819 1857.49
#Mann= 5 ,-1 , 0
       0      .1       0   63.03     .06       0  192.71      .1       0
   366.9    .045       0     449      .1       0
Bank Sta=366.9,449
XS Rating Curve= 0 ,0
Exp/Cntr=0.3,0.1

Type RM Length L Ch R = 1 ,18321   ,131.3,126.4,123.4
XS GIS Cut Line= 3
2417984.60790187676987.5621859942417956.26289407676744.222273532
2417352.48319224676422.685644067
#Sta/Elev= 30
       0 1838.16    28.9 1835.46      53 1828.71    93.3 1803.11   113.4 1788.33
   129.5 1783.55   145.6 1774.48   181.9 1774.31     202 1777.35   226.2 1775.24
   251.2 1772.91   273.9 1766.15   319.2 1763.74   364.5 1764.73   381.2 1759.06
   403.8 1756.31   446.1 1756.56   452.1 1758.73   459.7 1764.95   468.8 1765.69
   483.7 1762.92   542.8  1760.9   695.4 1760.66   844.9 1760.03   862.2 1766.69
   876.6 1780.24   890.2 1796.35   903.8 1805.82   917.4 1811.17     929 1818.93
#Mann= 7 ,-1 , 0
       0      .1       0    28.9     .06       0   226.2    .055       0
   319.2     .05       0   381.2    .045       0   452.1     .05       0
   695.4      .1       0
#XS Ineff= 2 , 0
                           468.4            1778
Permanent Ineff=
       F       F
Bank Sta=381.2,452.1
XS Rating Curve= 0 ,0
Exp/Cntr=0.5,0.3

Type RM Length L Ch R = 1 ,18195   ,37.3,36.8,36.1
XS GIS Cut Line= 3
2418098.65235426 676709.640882442417977.82717018676597.605206344
 2417388.0156345676389.179003217
#Sta/Elev= 30
       0 1771.57    89.6 1770.69   114.4 1771.09     168 1766.14   184.9 1764.69
   223.2 1763.56   227.4 1762.59   233.31758.877   240.2 1755.31   248.6 1753.91
   286.8 1754.39   291.1 1755.27   296.6 1758.82   299.6 1761.03   304.1 1762.24
   329.2 1760.81   439.6 1758.99   562.6 1759.08   620.7 1760.03   655.9 1760.16
   716.5 1757.74   740.8 1757.42   749.3 1757.94   757.7 1759.84     762 1761.78
   766.2 1765.53   770.5  1771.4   774.7 1774.68   783.2 1779.12   790.3 1785.32
#Mann= 5 ,-1 , 0
       0      .1       0     168     .06       0   233.3    .045       0
   296.6     .05       0   620.7      .1       0
#XS Ineff= 2 , 0
             218    1768   304.1            1768
Permanent Ineff=
       F       F
Bank Sta=233.3,296.6
XS Rating Curve= 0 ,0
Exp/Cntr(USF)=0,0
Exp/Cntr=0.5,0.3

Type RM Length L Ch R = 1 ,18158   ,189.5,183.9,179.8
XS GIS Cut Line= 3
2418142.53965343676685.5737305962418002.67679286676565.254240378
2417362.76936592676352.611129318
#Sta/Elev= 30
       0  1770.1   139.1 1768.26   222.4 1764.69   256.1 1762.93   264.5    1761
   268.6  1759.2   277.2 1754.08   306.5 1753.42   323.5 1754.06   328.7  1757.6
   331.8 1760.16   336.2 1761.74   340.4 1761.97   360.3 1760.44   433.1 1758.75
   626.1 1758.34   669.2 1759.43   686.7 1761.23   702.9  1759.2   715.5 1758.49
     783 1756.58   795.6 1758.97   803.2 1761.63   808.3 1764.64   812.5 1769.45
   816.7 1776.41   820.9 1782.25   825.1 1786.58   841.2  1799.4   858.8 1810.67
#Mann= 6 ,-1 , 0
       0      .1       0   222.4     .06       0   268.6    .045       0
   328.7     .06       0   331.8     .05       0   669.2      .1       0
#XS Ineff= 2 , 0
                           340.4            1768
Permanent Ineff=
       F       F
Bank Sta=268.6,328.7
XS Rating Curve= 0 ,0
Exp/Cntr=0.5,0.3

Type RM Length L Ch R = 1 ,17974   ,321.8,300.6,280.4
XS GIS Cut Line= 3
2418254.11848846676480.5807475352417977.86327023676352.888921885
2417389.88377003676330.183943648
#Sta/Elev= 30
       0 1814.16      61 1804.92    78.6 1803.43    96.3 1803.41   105.1  1801.9
   137.5 1787.95   144.7 1782.95   157.9 1771.73     180 1763.73   184.4 1762.96
   281.3    1762   347.5 1763.42   355.5  1762.5   359.5 1761.28   363.8 1758.56
   371.5 1753.79   375.5 1753.29   431.6 1752.89   447.6 1753.64   459.6 1758.37
   459.6 1758.38   463.6 1758.83   476.2 1756.82   503.6 1756.16   727.8 1758.15
   839.9  1755.6   847.9 1757.84   875.9 1774.39   887.9 1784.72   892.8 1790.05
#Mann= 7 ,-1 , 0
       0      .1       0   99.51      .1       0  233.54     .06       0
  345.79      .1       0   363.8    .045       0   459.6     .05       0
  751.08      .1       0
Bank Sta=363.8,459.6
XS Rating Curve= 0 ,0
Exp/Cntr=0.3,0.1

Type RM Length L Ch R = 1 ,17673   ,257.6,263,263.8
XS GIS Cut Line= 3
     2418149.384      675905.313     2417772.061      676064.429
2417343.15729573676249.964385115
#Sta/Elev= 30
       0 1852.57      81 1843.22     104 1838.06   119.3 1832.61   128.8 1827.46
   143.7 1816.91   163.5 1793.41   176.5 1781.44   198.6 1764.44   211.2 1757.06
   232.9 1755.88     275 1757.25   293.7 1753.27   329.9 1754.13   363.2 1752.36
   371.9 1750.18   393.6 1749.97   441.4 1750.09     456 1752.35   464.1 1754.42
     485 1753.39   546.7 1754.05   694.2 1752.65   759.6 1756.78   768.3 1758.87
   794.5 1770.78     817 1784.78   855.5 1814.81   868.1 1830.17   876.8 1835.98
#Mann= 7 ,-1 , 0
       0      .1       0  187.56     .06       0  289.77      .1       0
   363.2    .045       0     456      .1       0  494.37     .05       0
  596.81      .1       0
Bank Sta=363.2,456
XS Rating Curve= 0 ,0
Exp/Cntr=0.3,0.1

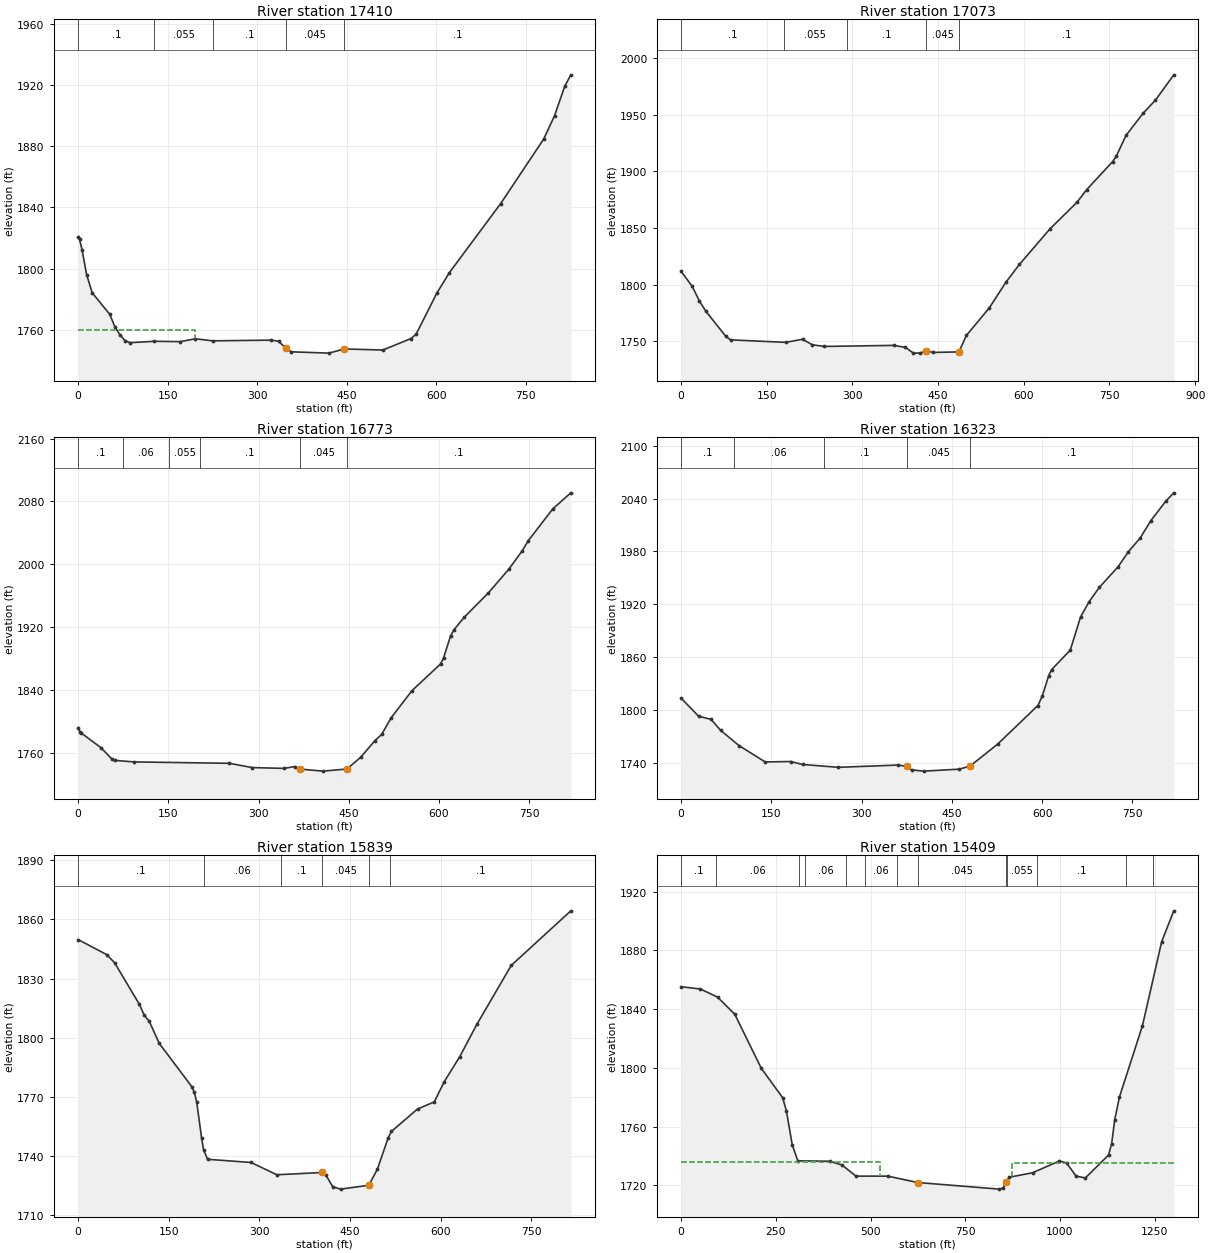
Type RM Length L Ch R = 1 ,17410   ,306.4,337,357.9
XS GIS Cut Line= 3
      2418052.95      675695.2832417659.20292341675827.166714904
     2417277.279      675976.119
#Sta/Elev= 30
       0 1820.85     2.3  1819.1     6.5 1812.28    14.1 1796.14    23.4 1784.27
    52.9 1770.13    61.4 1762.02    69.8 1756.83    78.3 1752.95    86.7 1751.59
   127.8 1752.48   171.1 1752.26   196.4 1754.12   225.5 1752.79   323.8 1753.24
   335.6  1752.5   348.2 1747.84   356.7 1745.61     420 1744.75   445.8 1747.48
   510.2 1746.77   557.4 1754.26     566 1757.09   600.7 1783.92   621.8 1797.41
   707.7 1842.53   779.9 1884.81   797.9 1899.95     815 1919.23   825.2 1926.71
#Mann= 5 ,-1 , 0
       0      .1       0   127.8    .055       0   225.5      .1       0
   348.2    .045       0   445.8      .1       0
#XS Ineff= 2 , 0
           196.4    1760
Permanent Ineff=
       F       F
Bank Sta=348.2,445.8
XS Rating Curve= 0 ,0
Exp/Cntr=0.3,0.1

Type RM Length L Ch R = 1 ,17073   ,285.7,300,312.9
XS GIS Cut Line= 3
2418085.06458299675651.302110651     2417653.394      675511.182
     2417272.814      675362.049
#Sta/Elev= 30
       0  1811.8    19.3 1798.65    31.9 1785.71    43.4 1776.59    78.1 1754.61
    86.5 1751.42   183.3 1749.22   212.7 1751.98   229.5 1747.11   250.6 1745.62
   372.5 1746.55   392.7 1744.76   406.2 1739.91   418.8 1739.73   428.9 1742.03
   440.3 1740.35   486.3  1740.8   499.6 1755.44   539.5 1779.59   568.4 1802.09
   592.2 1817.89   645.7 1849.24     693 1872.69   710.2 1883.96   755.5 1908.61
   761.7 1913.17   778.9 1931.68     809 1951.28   830.5  1962.8   862.6  1985.1
#Mann= 5 ,-1 , 0
       0      .1       0  179.23    .055       0  290.89      .1       0
   428.9    .045       0   486.3      .1       0
Bank Sta=428.9,486.3
XS Rating Curve= 0 ,0
Exp/Cntr=0.3,0.1

Type RM Length L Ch R = 1 ,16773   ,450,450,449.2
XS GIS Cut Line= 3
     2418100.893      675519.533     2417791.968      675250.245
     2417493.147      674970.333
#Sta/Elev= 30
       0  1791.8     2.8 1786.65     4.8 1785.18    37.5 1766.56    55.8 1752.14
    61.2 1750.13    92.7 1748.22   251.5 1746.44   289.4    1741   342.5 1739.97
   360.1  1742.3     369 1739.05   407.4 1736.48     447 1739.19   469.7 1754.07
   493.7 1775.44   504.7 1783.16   520.6  1804.6   555.1 1838.95   602.7 1873.02
   607.8 1881.02   619.5 1909.11   625.2 1916.73   641.7  1932.2   681.9 1963.23
   715.9 1993.39   738.5  2017.1   748.2 2029.59   789.4 2070.56   819.3 2090.91
#Mann= 6 ,-1 , 0
       0      .1       0   74.94     .06       0  151.53    .055       0
  202.43      .1       0     369    .045       0     447      .1       0
Bank Sta=369,447
XS Rating Curve= 0 ,0
Exp/Cntr=0.3,0.1

Type RM Length L Ch R = 1 ,16323   ,483,484.8,489.6
XS GIS Cut Line= 3
     2418404.288      675185.958      2418094.95      674917.629
     2417785.612        674649.3
#Sta/Elev= 30
       0 1813.63    29.1  1793.1    49.7 1789.63    65.7 1777.12    96.2 1759.88
   139.7 1741.31   182.1 1741.81   201.8 1738.45   261.3 1735.22   360.5 1737.79
   374.7 1736.33   383.3 1732.27   403.1 1730.91   462.7 1733.16   480.8 1736.88
   526.3 1761.65   593.1 1805.33   600.4 1816.15     611 1839.13   615.7 1845.88
   646.9 1868.15   663.9 1905.55   678.1 1922.94   695.1 1939.21   726.3 1962.57
   743.3 1979.52   763.2 1995.36   780.4 2014.56   805.7 2037.09     819 2046.51
#Mann= 5 ,-1 , 0
       0      .1       0   87.64     .06       0   236.8      .1       0
   374.7    .045       0   480.8      .1       0
Bank Sta=374.7,480.8
XS Rating Curve= 0 ,0
Exp/Cntr=0.3,0.1

Type RM Length L Ch R = 1 ,15839   ,235.4,429.9,488.2
XS GIS Cut Line= 3
2418578.42823629674980.6549030072418484.36796221674621.482197086
2418163.45236328674314.237494125
#Sta/Elev= 30
       0 1849.75    47.1 1842.15    60.2 1838.04   101.1 1817.03   109.3  1811.4
   117.6 1808.34   134.1 1797.13     188 1775.16     192 1772.42   196.2 1767.44
   204.4 1748.87   207.6 1743.15   214.2 1738.25   286.3 1736.63   328.9  1730.4
   403.91731.552   409.7 1730.49   421.3 1724.36   434.4 1723.11   481.21725.078
   495.4 1733.27   512.9 1748.87   518.5 1752.37   561.8 1763.76   589.5 1767.37
   606.1 1777.67   631.7 1790.32     660  1806.7   716.9 1836.63   815.6 1864.35
#Mann= 6 ,-1 , 0
       0      .1       0  208.73     .06       0  336.05      .1       0
   403.9    .045       0   481.2    .045       0   516.3      .1       0
Bank Sta=403.9,481.2
XS Rating Curve= 0 ,0
Exp/Cntr=0.5,0.3

Type RM Length L Ch R = 1 ,15409   ,236.8,152,180.5
XS GIS Cut Line= 4
2418639.20144195675016.4189085972418532.31480156674558.462059695
2418947.03393344674173.352836458  2418999.495913673914.062273389
#Sta/Elev= 30
       0 1855.31    50.9 1853.75      96 1848.26   141.5  1836.6   211.5 1799.78
   268.1 1779.67   278.1  1770.5   293.2 1747.76     308  1736.7   391.8 1736.43
   424.6  1733.9   461.6 1726.28   545.3 1726.29   624.91721.927     840 1717.43
     851 1718.36   857.51722.338   866.6 1725.53   928.1 1728.59   998.7 1736.62
  1017.9 1735.17  1042.8 1726.28  1067.3 1725.05  1128.5 1740.66  1136.7 1748.49
  1144.8 1764.75  1157.4 1780.28    1218 1828.74  1268.9 1886.12  1300.8 1907.02
#Mann= 13 ,-1 , 0
       0      .1       0   91.25     .06       0  311.57      .1       0
  326.17     .06       0   435.2      .1       0  486.45     .06       0
  569.34      .1       0   624.9    .045       0   857.5    .045       0
     860    .055       0  939.15      .1       0 1174.84     .06       0
 1245.23      .1       0
#XS Ineff= 2 , 0
             525    1736     874            1735
Permanent Ineff=
       F       F
Bank Sta=624.9,857.5
XS Rating Curve= 0 ,0
Exp/Cntr=0.5,0.3

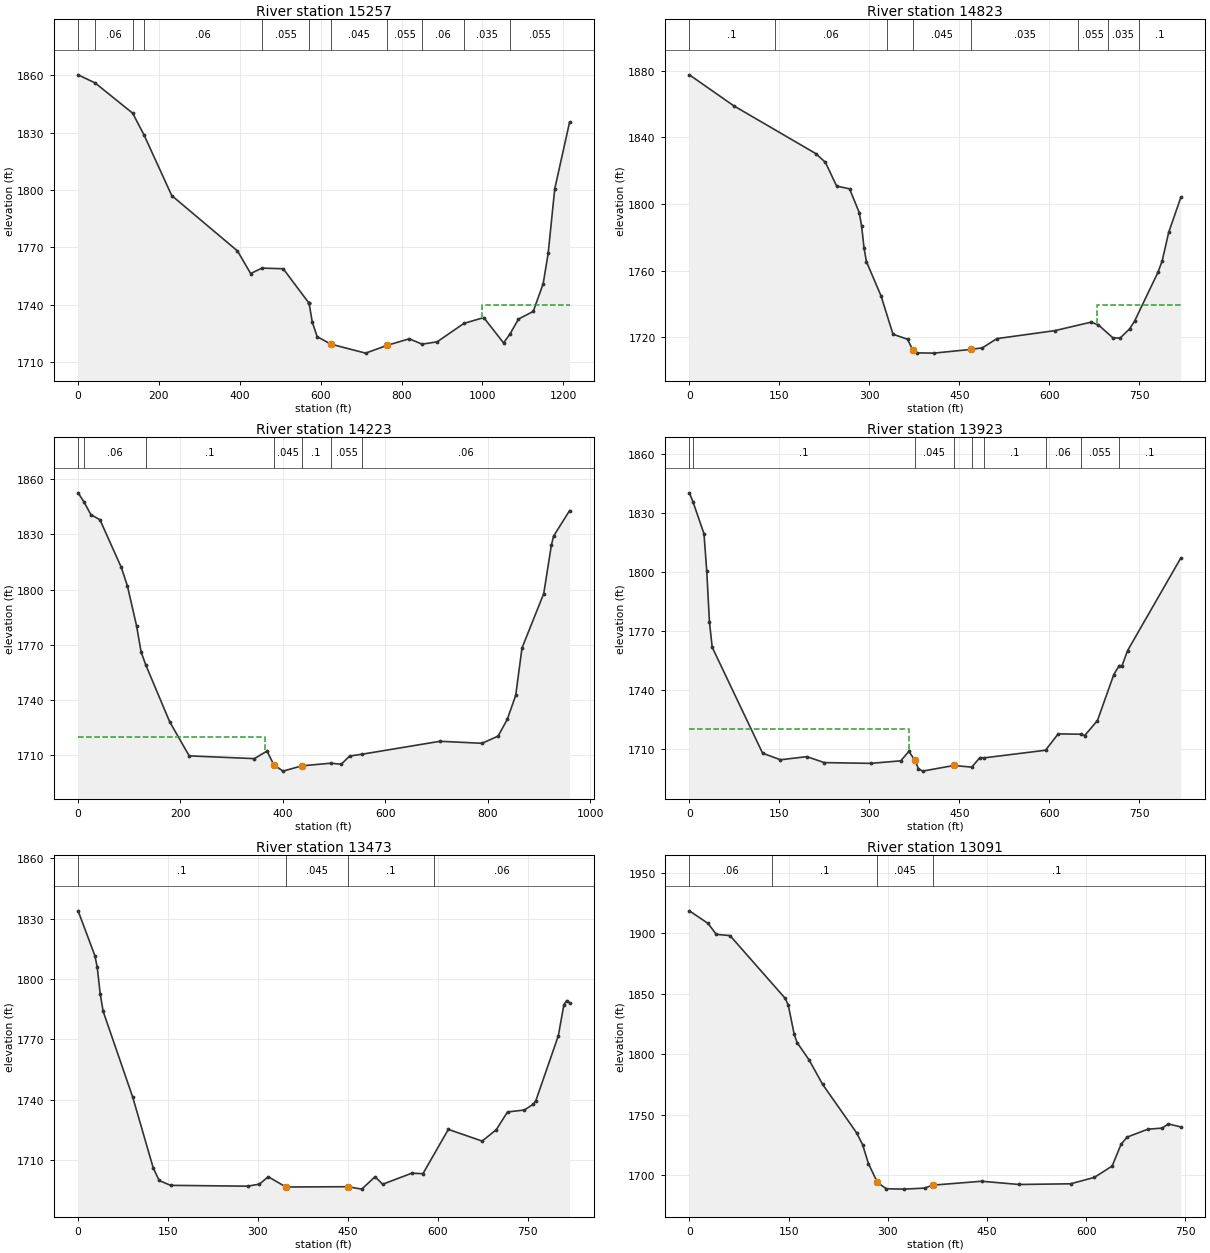
Type RM Length L Ch R = 1 ,15257   ,482.1,433.3,369.6
XS GIS Cut Line= 5
2418710.95193715 674964.700095232418677.60065109674700.921741837
 2418844.9859094674421.8762063862419114.67495999674256.743914196
2419176.70953336673955.083216749
#Sta/Elev= 30
       0 1860.33    42.1 1856.08   134.9 1840.26   163.4 1828.71   231.6 1797.12
   394.2 1768.13   426.8  1756.3   454.7 1759.15   507.3 1758.81   571.4 1740.71
   571.4 1740.67   571.4 1740.65   579.1 1730.93   591.3 1723.26   625.31719.321
   711.1 1714.64   764.41718.708   819.1 1722.15   850.7 1719.33   888.1 1720.57
   954.3 1730.21  1003.3 1733.25  1052.3 1719.99  1068.3 1724.68  1089.1 1732.46
  1125.7 1736.48  1150.3 1751.01  1162.6 1766.85  1178.9 1800.67  1215.5 1835.49
#Mann= 11 ,-1 , 0
       0      .1       0    42.1     .06       0   134.9      .1       0
   163.4     .06       0   454.7    .055       0   571.4    .045       0
   625.3    .045       0   764.4    .055       0   850.7     .06       0
   954.3    .035       0  1068.3    .055       0
#XS Ineff= 2 , 0
                           999.2            1740
Permanent Ineff=
       F       F
Bank Sta=625.3,764.4
XS Rating Curve= 0 ,0
Exp/Cntr=0.5,0.3

Type RM Length L Ch R = 1 ,14823   ,585.7,600,622
XS GIS Cut Line= 3
     2419308.561      674820.056     2419354.523      674413.143
     2419400.485      674006.231
#Sta/Elev= 30
       0  1877.6    73.6 1859.07   210.5  1830.3   226.6 1825.05   245.4 1810.75
   266.9  1809.1     283 1794.85     287 1786.72     291 1773.64     295 1765.36
   319.2 1744.93   339.3 1721.73   363.5 1718.72     372 1712.43   379.6 1710.53
   407.3 1710.38   469.6 1712.63   488.3 1713.57   512.4  1719.1     609 1723.89
   669.4    1729   681.5 1727.36   705.6 1719.62   717.7  1719.4   733.8 1725.05
   741.9  1729.6   780.7 1758.84   787.9 1765.79   798.7 1782.88     819    1804
#Mann= 8 ,-1 , 0
       0      .1       0  141.83     .06       0  329.38      .1       0
     372    .045       0   469.6    .035       0  647.38    .055       0
  697.46    .035       0   748.5      .1       0
#XS Ineff= 2 , 0
                          679.67          1739.2
Permanent Ineff=
       F       F
Bank Sta=372,469.6
XS Rating Curve= 0 ,0
Exp/Cntr=0.3,0.1

Type RM Length L Ch R = 1 ,14223   ,299,300,299.4
XS GIS Cut Line= 4
     2419701.065      675025.066     2419883.817       674658.75
  2419912.045454674609.682606537   2419800.82683674128.390147888
#Sta/Elev= 30
       0 1852.65    11.8 1847.54    24.8 1840.84    42.7 1837.96    84.4 1812.02
    96.3 1801.99   114.2 1780.22   123.1    1766   132.1 1759.02   178.8 1728.06
     217 1709.45   344.2 1707.96     369 1712.04   382.4 1704.58   400.3 1701.15
   436.81704.016   493.5 1705.46     514  1704.9   530.4 1709.36   555.1 1710.38
     707  1717.4   789.1  1716.3   820.4 1720.21   838.3  1729.3   854.8 1742.39
   867.1 1768.17   909.6 1797.84   924.5 1824.14   928.7 1829.03     960 1842.95
#Mann= 7 ,-1 , 0
       0      .1       0    11.8     .06       0   132.1      .1       0
   382.4    .045       0   436.8      .1       0   493.5    .055       0
   555.1     .06       0
#XS Ineff= 2 , 0
           364.5    1720
Permanent Ineff=
       F       F
Bank Sta=382.4,436.8
XS Rating Curve= 0 ,0
Exp/Cntr=0.3,0.1

Type RM Length L Ch R = 1 ,13923   ,444.6,450,451.9
XS GIS Cut Line= 3
     2419954.583      675156.239     2420150.262      674796.517
     2420345.942      674436.795
#Sta/Elev= 30
       0 1840.37     6.1 1835.69    24.3 1819.55    28.9 1800.53    33.4 1774.67
      38  1761.8     122 1707.92   151.8 1704.58   195.8 1706.17   224.7 1703.14
   302.1 1702.75   352.2 1704.04   365.8 1708.86   375.7 1704.32   381.6 1700.11
   388.6  1698.8   440.5 1701.67   470.5 1700.83   484.2 1705.71   490.7 1705.53
   593.5 1709.43   614.6 1717.75     652 1717.57   658.8  1716.9     680 1724.54
   707.3 1747.94   716.4 1752.51     721  1752.4   730.1 1760.05     819 1807.26
#Mann= 9 ,-1 , 0
       0     .06       0     6.1      .1       0   375.7    .045       0
   440.5      .1       0   470.5    .035       0   490.7      .1       0
   593.5     .06       0     652    .055       0   716.4      .1       0
#XS Ineff= 2 , 0
           365.8    1720
Permanent Ineff=
       F       F
Bank Sta=375.7,440.5
XS Rating Curve= 0 ,0
Exp/Cntr=0.3,0.1

Type RM Length L Ch R = 1 ,13473   ,393.1,382.1,387.6
XS GIS Cut Line= 3
     2420297.565      675360.804     2420536.623      675026.939
     2420751.999      674678.887
#Sta/Elev= 30
       0 1833.82      28 1811.51    31.9 1805.78    36.8 1792.73    41.7 1783.96
    91.1 1741.29   125.3 1706.15   135.2 1699.88   154.2 1697.47   282.8 1697.06
   302.5 1698.08   317.2 1701.76   346.7 1696.65     450 1696.79   473.2 1695.59
   495.4 1701.74   508.1 1698.01   556.5 1703.49   575.3 1703.27   617.7 1725.27
   674.1 1719.45   697.6 1725.09   716.4 1733.92   744.7  1734.9   758.8 1737.66
   763.5 1739.38   801.1  1771.7   810.5 1787.21   815.2 1789.26   819.9  1788.2
#Mann= 4 ,-1 , 0
       0      .1       0   346.7    .045       0     450      .1       0
  594.52     .06       0
Bank Sta=346.7,450
XS Rating Curve= 0 ,0
Exp/Cntr=0.3,0.1

Type RM Length L Ch R = 1 ,13091   ,393.3,367.9,360.6
XS GIS Cut Line= 2
2420657.24578717675600.0123128512420995.60222977674938.444131916
#Sta/Elev= 30
       0 1918.35    28.2 1907.94    40.6 1898.91    61.4 1897.87     145 1845.92
   149.5 1840.42   158.5 1816.21     163 1809.35     181 1795.12   201.4 1774.98
   252.9 1734.83   261.8 1725.22   270.8 1709.33   284.3 1693.89   284.3 1693.87
   297.8 1688.67   324.7 1688.36   355.7  1689.2   367.6 1691.63   441.9 1694.87
   498.4  1692.2   576.3 1692.76   612.3 1698.06   639.2 1707.43   652.7  1725.4
   661.8 1731.33   693.2  1737.9   714.8 1738.79   724.3 1742.24   743.1 1739.74
#Mann= 4 ,-1 , 0
       0     .06       0  125.34      .1       0   284.3    .045       0
   367.6      .1       0
Bank Sta=284.3,367.6
XS Rating Curve= 0 ,0
Exp/Cntr=0.3,0.1

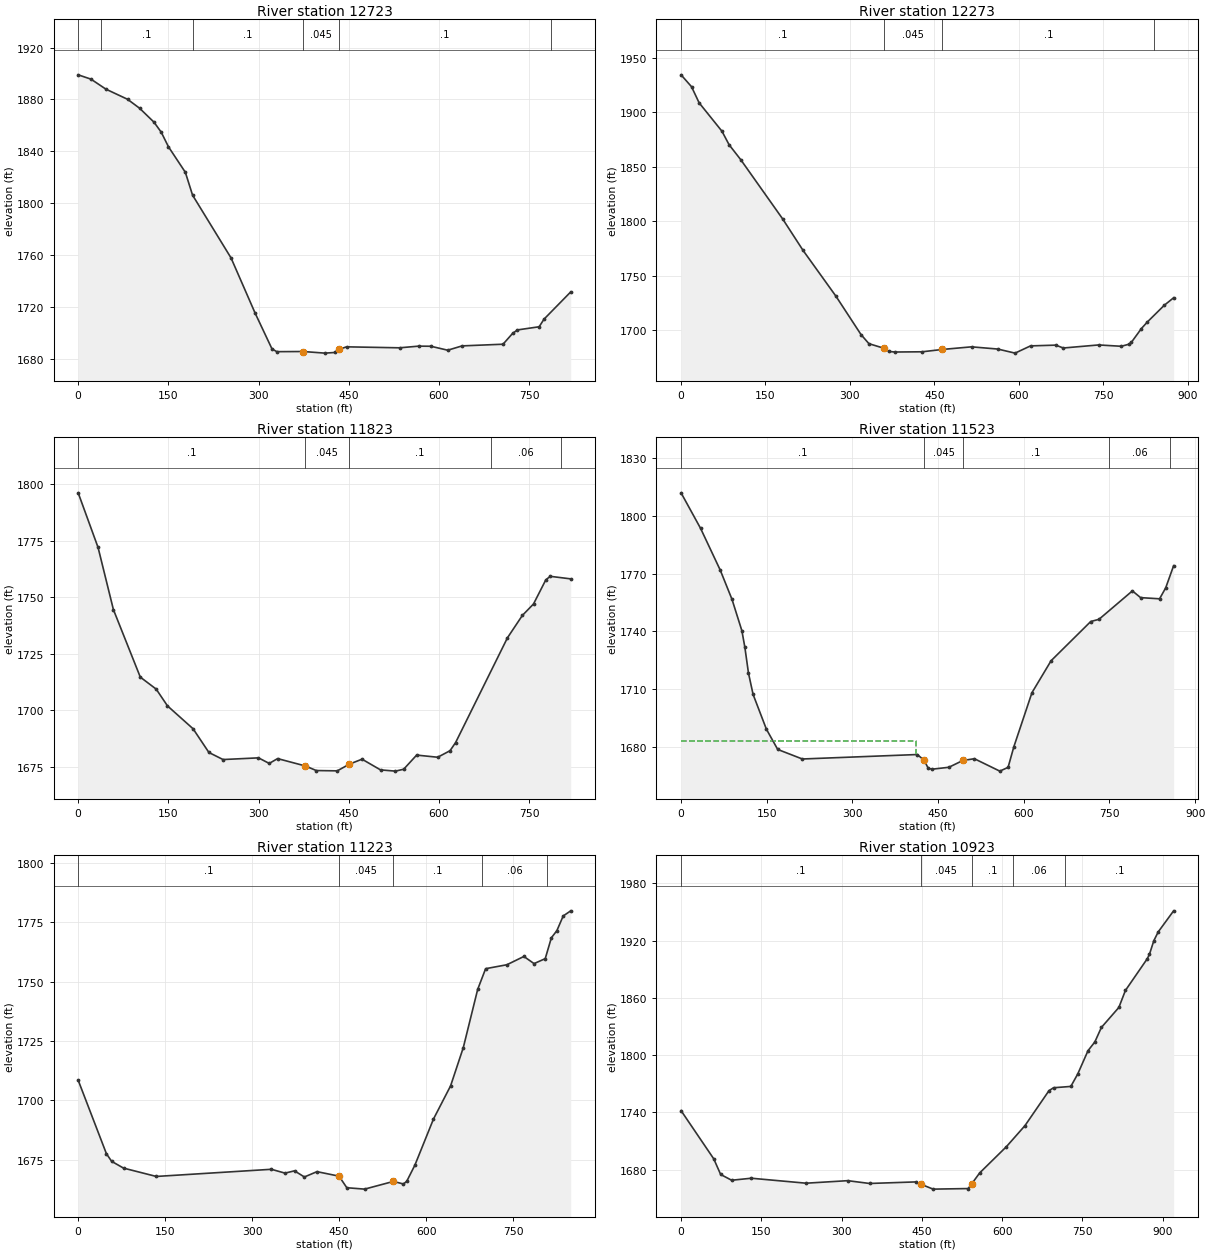
Type RM Length L Ch R = 1 ,12723   ,472.4,450,423.9
XS GIS Cut Line= 3
      2421154.82      675768.956     2421167.798      675359.662
     2421180.776      674950.368
#Sta/Elev= 30
       0 1899.02    21.3 1895.69    46.1 1887.98    82.1 1880.17   102.1 1873.27
   126.1  1862.5   138.1  1854.8   150.1 1843.56   178.2 1823.88   190.2 1806.25
   254.2 1757.83   294.2 1715.32   322.2 1687.76   330.2 1685.58   374.2 1685.69
   410.3 1684.45   426.3 1684.94   434.3 1687.45   446.3  1689.3   534.3 1688.55
   566.3 1689.84   586.4 1689.75   614.4  1686.7   638.4 1690.03   706.4 1691.32
   722.4 1699.69   730.4 1702.34   766.5 1704.78   774.5 1710.61     819 1731.66
#Mann= 6 ,-1 , 0
       0      .1       0   38.36      .1       0  190.78      .1       0
   374.2    .045       0   434.3      .1       0  786.27     .06       0
Bank Sta=374.2,434.3
XS Rating Curve= 0 ,0
Exp/Cntr=0.3,0.1

Type RM Length L Ch R = 1 ,12273   ,452.3,450,447.3
XS GIS Cut Line= 3
     2421797.117      675695.444     2421609.408      675332.212
2421399.38380192674915.864385071
#Sta/Elev= 30
       0 1934.41    18.6 1923.49    32.1  1908.7    72.7 1882.58    85.3 1870.22
   106.1 1856.43   180.3 1802.21   216.7 1773.17   275.3 1730.97   319.8 1695.76
   333.8 1687.43   360.8 1683.18   369.8 1680.27   379.8 1679.77   428.3 1679.98
   464.1 1682.11   516.1 1684.53   562.7  1682.5   593.5 1678.75   620.9  1685.4
   665.7 1686.09   679.2 1683.46   741.9 1686.27   782.2 1685.04   795.6 1686.91
   800.1 1688.65     818 1701.36   828.7 1707.46   858.8 1722.82   875.2  1729.6
#Mann= 4 ,-1 , 0
       0      .1       0   360.8    .045       0   464.1      .1       0
  840.82     .06       0
Bank Sta=360.8,464.1
XS Rating Curve= 0 ,0
Exp/Cntr=0.3,0.1

Type RM Length L Ch R = 1 ,11823   ,299.4,300,295.4
XS GIS Cut Line= 3
     2422209.317      675469.563     2422003.618      675115.475
     2421797.919      674761.387
#Sta/Elev= 30
       0 1796.17    33.1    1772    58.6 1744.52   103.3 1714.68   129.7 1709.38
   148.5 1701.96   191.1 1691.83   217.4 1681.35   240.9 1678.23   299.8 1678.98
   317.7 1676.52   331.6 1678.65   377.8 1675.39   395.9 1673.37   430.8 1673.23
   451.1 1676.22     472 1678.39   502.7 1673.66   527.6 1673.11   541.2 1673.95
   562.8  1680.2   597.8 1679.25   618.3 1682.14   627.6 1685.76   713.8 1732.08
   738.6 1741.97   757.1 1747.02   777.5 1757.67   784.9 1759.25     819 1758.12
#Mann= 5 ,-1 , 0
       0      .1       0   377.8    .045       0   451.1      .1       0
  685.73     .06       0  802.77      .1       0
Bank Sta=377.8,451.1
XS Rating Curve= 0 ,0
Exp/Cntr=0.3,0.1

Type RM Length L Ch R = 1 ,11523   ,300.9,300,299.4
XS GIS Cut Line= 3
2422520.98938507675364.150424241     2422275.299      674991.553
     2422042.948      674646.464
#Sta/Elev= 30
       0 1811.97    34.3 1793.42    68.6 1771.78    89.2 1756.56   106.5 1740.24
   111.7 1731.65     118 1718.27   126.1 1707.14   149.4 1689.06   169.2 1678.53
   212.3 1673.56   413.6 1675.88   425.5  1672.9   432.8 1668.68   440.1 1668.28
   468.8 1669.25   493.3 1672.78   513.5  1673.7     558 1667.25   572.5 1669.21
   582.6 1679.93   614.3 1708.05   647.8 1724.66   717.2 1745.05   731.6 1746.19
   790.1 1760.97   804.5 1757.47   837.7 1756.86   848.4 1762.54   862.3 1774.09
#Mann= 5 ,-1 , 0
       0      .1       0   425.5    .045       0   493.3      .1       0
  749.07     .06       0   856.8      .1       0
#XS Ineff= 2 , 0
           411.7 1682.73
Permanent Ineff=
       F       F
Bank Sta=425.5,493.3
XS Rating Curve= 0 ,0
Exp/Cntr=0.3,0.1

Type RM Length L Ch R = 1 ,11223   ,280.3,300,323.8
XS GIS Cut Line= 3
2422782.31329859675147.848418029     2422482.422       674775.05
2422251.36790835674484.775837399
#Sta/Elev= 30
       0 1708.51    48.7  1677.6    57.7 1674.39    78.2 1671.54   134.7 1668.03
   333.2 1671.04   356.7 1669.43   373.1 1670.39   390.1 1667.81   411.9 1670.05
   449.9 1668.15   463.3 1663.29     494  1662.7   543.8 1665.95   560.9 1664.86
   566.6 1665.97   580.7 1672.78   612.8 1692.19   642.3 1706.13   664.2 1722.21
     689 1746.68   702.7 1755.39   739.4 1757.05   768.7 1760.53   786.2 1757.53
   805.5 1759.61   816.1 1768.39   825.6 1771.39   836.5 1777.56   849.5 1779.72
#Mann= 5 ,-1 , 0
       0      .1       0   449.9    .045       0   543.8      .1       0
  696.62     .06       0  808.89      .1       0
Bank Sta=449.9,543.8
XS Rating Curve= 0 ,0
Exp/Cntr=0.3,0.1

Type RM Length L Ch R = 1 ,10923   ,447.2,450,451
XS GIS Cut Line= 3
2422860.30956721675151.204612171     2422752.153      674651.903
     2422670.284       674250.68
#Sta/Elev= 30
       0 1741.77    61.1 1691.18      74 1674.82    94.5 1668.76   131.3 1670.87
   233.6 1665.66   311.4 1668.31   352.3 1665.37   438.2    1667   447.7 1664.68
     471 1659.44   536.4 1660.03   543.4 1665.18   557.9 1676.38   607.9 1703.94
   642.6 1726.01   687.5  1762.7     696 1765.75   728.3 1767.14   741.2 1780.15
   760.4 1804.61   773.2  1813.8   785.4 1828.97   818.1 1849.99   830.3 1867.78
   871.2 1901.09   875.3 1905.84   883.4 1919.95   891.6 1929.19   920.4 1951.29
#Mann= 5 ,-1 , 0
       0      .1       0   447.7    .045       0   543.4      .1       0
  620.26     .06       0  717.91      .1       0
Bank Sta=447.7,543.4
XS Rating Curve= 0 ,0
Exp/Cntr=0.3,0.1