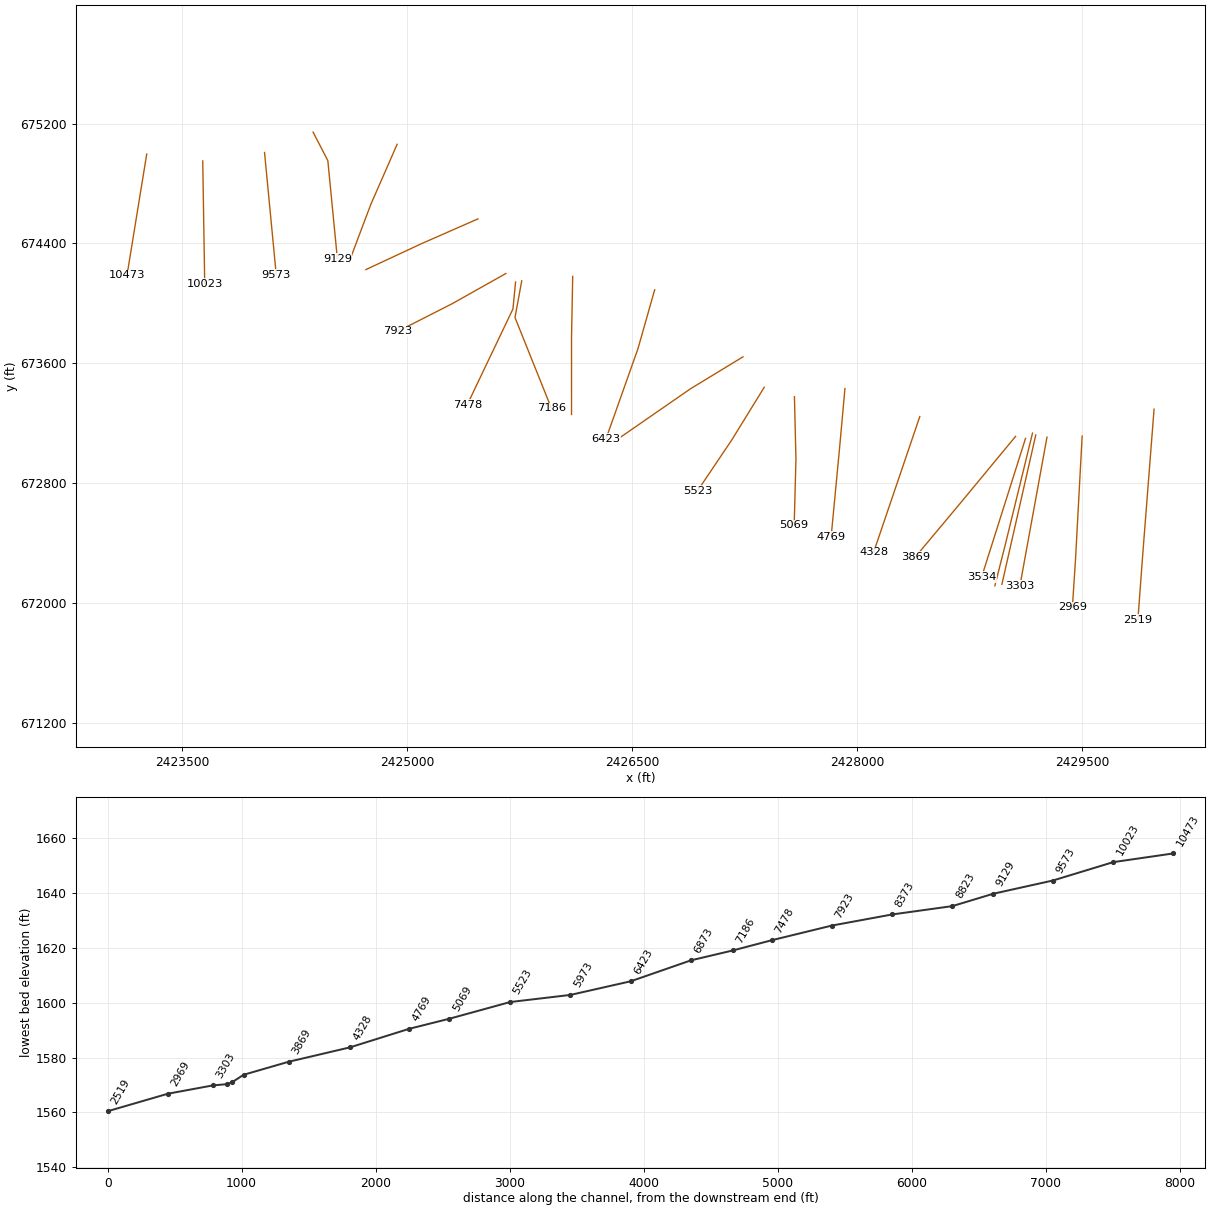
HEC-RAS study SENECACK.prj: SENECACK

--- SENECACK.g03 (geometry) --- (continued)

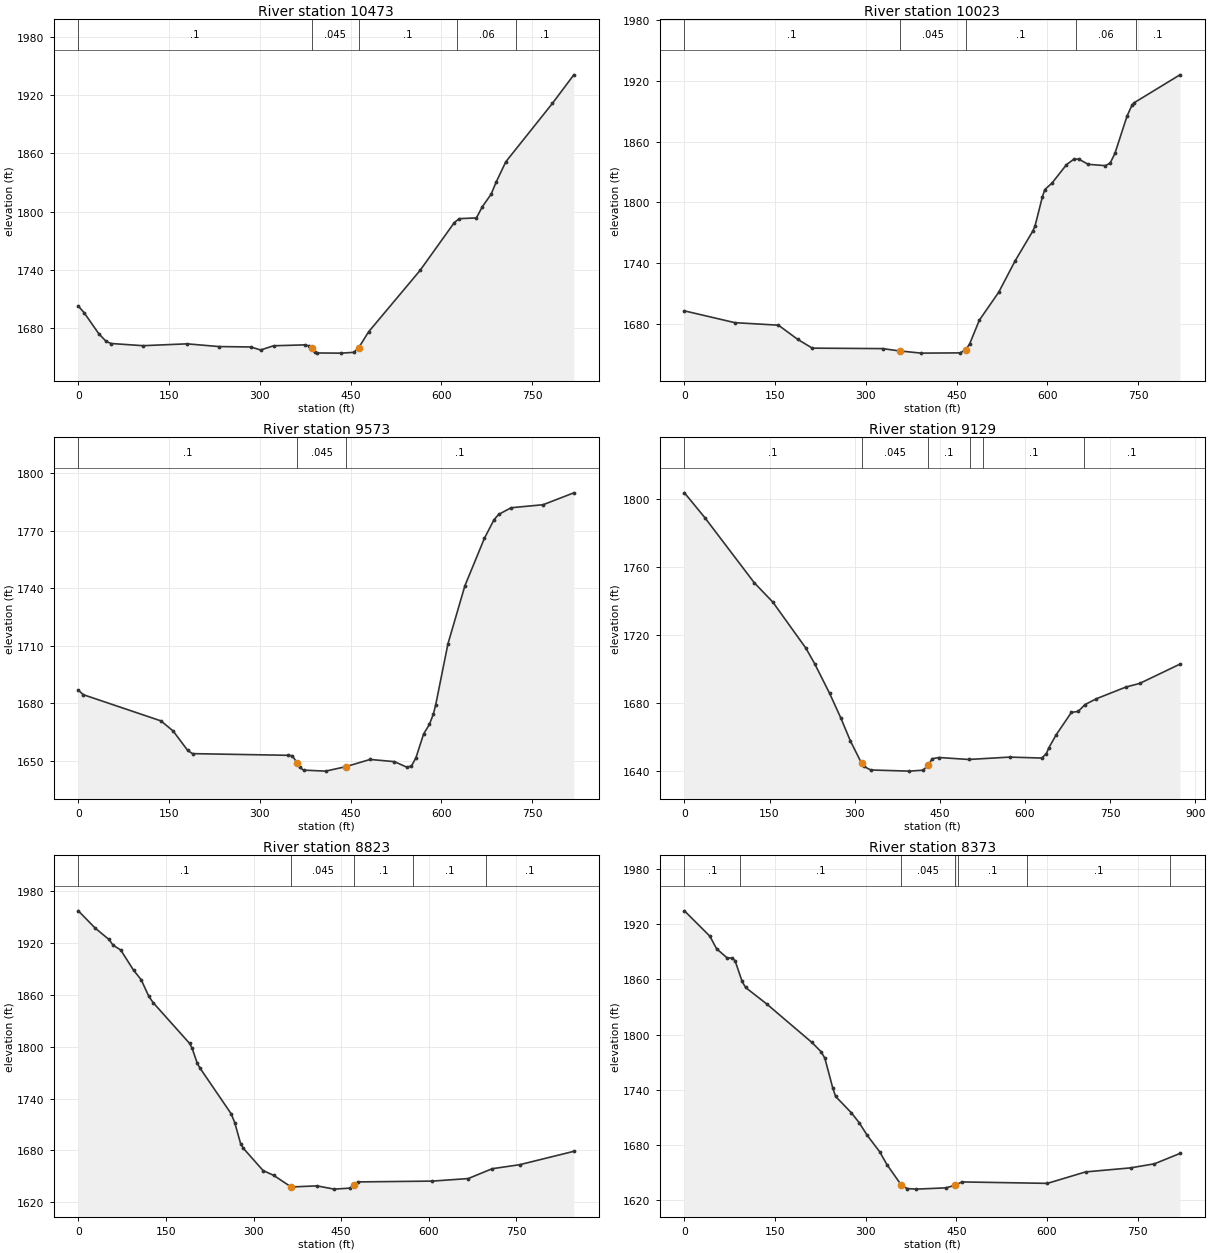
Type RM Length L Ch R = 1 ,10473   ,442.5,450,459.5
XS GIS Cut Line= 3
      2423263.59      674996.386     2423197.914      674592.187
     2423132.239      674187.988
#Sta/Elev= 30
       0 1702.89     9.6 1696.03    33.9 1674.38    46.1 1666.46    54.2 1664.34
   106.9  1662.1   179.9    1664   232.5 1661.19   285.2 1660.77   301.4 1657.67
   322.8 1662.02   374.3 1662.93     382 1661.84   385.5 1659.21   390.6 1655.21
   394.6  1654.6   434.3 1654.44   455.4 1655.24   463.5 1660.08   479.8 1676.37
   564.8  1739.5   621.5 1788.79   629.6  1792.8     658 1793.57   667.9 1805.23
   682.3 1817.93   690.4 1830.12   706.6 1851.35   783.6  1911.4     819 1940.78
#Mann= 5 ,-1 , 0
       0      .1       0   385.5    .045       0   463.5      .1       0
  625.74     .06       0  723.28      .1       0
Bank Sta=385.5,463.5
XS Rating Curve= 0 ,0
Exp/Cntr=0.3,0.1

Type RM Length L Ch R = 1 ,10023   ,445.1,450,456.1
XS GIS Cut Line= 3
     2423636.988      674950.298     2423643.602      674540.852
     2423650.216      674131.405
#Sta/Elev= 30
       0 1692.95    83.4  1681.3   155.4 1678.81   187.4 1664.74   211.4 1656.17
   327.4 1655.71   356.4 1653.37   391.5 1651.25   455.5  1651.5   465.2  1654.6
   471.5 1660.48   487.5 1683.81   519.5 1711.37   546.5 1742.19   575.5 1771.36
   579.5  1776.7   591.5 1805.11   595.6 1812.59   607.5 1818.97   631.5 1837.15
   643.5 1842.51   651.5 1842.67   667.5  1837.5   695.5  1836.2   703.5 1838.51
   711.5 1848.21   731.5 1884.97   739.5 1895.55   743.5 1898.31     819 1925.77
#Mann= 5 ,-1 , 0
       0      .1       0   356.4    .045       0   465.2      .1       0
  646.87     .06       0  745.84      .1       0
Bank Sta=356.4,465.2
XS Rating Curve= 0 ,0
Exp/Cntr=0.3,0.1

Type RM Length L Ch R = 1 ,9573    ,458.5,444.2,446.3
XS GIS Cut Line= 3
     2424048.942      675006.991     2424087.928       674599.35
     2424126.915      674191.711
#Sta/Elev= 30
       0  1686.8     8.1 1684.44   136.7 1670.74   156.8 1665.45   180.9 1655.31
   188.8 1653.67   346.5 1652.81   353.7  1652.6   361.7  1648.8   365.8 1646.58
   372.2 1645.08   408.8 1644.55   442.1 1646.88   482.3 1650.64   522.5  1649.5
   542.6 1646.66   550.6  1647.2     558 1651.48   570.7 1663.93   580.2 1668.88
   586.8 1674.24   590.8 1679.28   610.9 1710.91     639 1741.27   671.1 1765.91
   687.2 1775.75   694.9 1778.48   715.3 1781.93   768.3 1783.51     819 1789.71
#Mann= 3 ,-1 , 0
       0      .1       0   361.7    .045       0   442.1      .1       0
Bank Sta=361.7,442.1
XS Rating Curve= 0 ,0
Exp/Cntr=0.3,0.1

Type RM Length L Ch R = 1 ,9129    ,345.3,305.8,293.3
XS GIS Cut Line= 3
     2424372.664       675142.692424470.88061124674952.565626011
     2424534.649      674296.417
#Sta/Elev= 30
       0 1803.48    35.8 1788.95   123.1 1750.56   155.8 1739.19     214  1712.1
   229.4 1703.02   255.9 1685.45     276 1670.71   292.3 1657.62   312.1 1644.39
   316.1 1642.56   328.2 1640.42   396.5 1639.74   420.5 1640.29   429.7 1643.27
   436.7 1647.05   448.8 1647.75     501  1646.6   573.4    1648   629.6 1647.43
   637.7 1649.91   641.7 1653.15   654.9 1661.02   681.9 1674.28   693.9  1674.9
     706 1678.91   726.1 1682.35   778.3 1689.25   802.4 1691.35   873.2  1702.7
#Mann= 6 ,-1 , 0
       0      .1       0   312.1    .045       0   429.7      .1       0
  503.16      .1       0  525.73      .1       0  704.55      .1       0
Bank Sta=312.1,429.7
XS Rating Curve= 0 ,0
Exp/Cntr=0.3,0.1

Type RM Length L Ch R = 1 ,8823    ,488.9,450,418.5
XS GIS Cut Line= 3
2424932.88968084675061.492531928     2424758.091       674662.14
     2424612.531        674276.1
#Sta/Elev= 30
       0 1957.48      29 1937.39    52.2 1924.48    59.6 1917.68    72.7 1912.06
    94.5 1888.83   107.6 1877.73   120.7 1858.53   128.1  1851.2   190.6 1803.93
     195 1798.09   203.7 1780.92   208.1 1775.68   261.8 1722.41   267.8 1712.35
   277.9 1687.99   282.3 1682.73   316.4 1656.77   334.7 1651.11   364.5 1637.72
   408.9 1638.99   437.9 1635.22   465.1 1636.37   472.1 1640.21   478.3 1643.57
   606.1 1644.51   667.7 1647.46   708.7 1658.86   755.7  1663.5   848.5    1679
#Mann= 5 ,-1 , 0
       0      .1       0   364.5    .045       0   472.1      .1       0
  573.62      .1       0  697.54      .1       0
Bank Sta=364.5,472.1
XS Rating Curve= 0 ,0
Exp/Cntr=0.3,0.1

Type RM Length L Ch R = 1 ,8373    ,447.1,450,451.3
XS GIS Cut Line= 3
      2425471.43      674563.821     2425097.177      674399.476
2424724.56298581674225.610364079
#Sta/Elev= 30
       0 1934.62    42.1 1907.06    53.2  1893.4    70.6 1883.47    79.4 1883.25
    83.8 1880.41    95.3 1858.13   101.2 1851.31   136.2 1833.39   210.7 1791.71
   225.9 1781.65   232.3 1774.59   245.4 1742.19   250.1 1732.97     276  1715.3
   289.1 1704.43   302.2 1690.88     323 1672.85   335.1 1658.82     359 1636.44
   368.5 1632.77   383.7 1632.17   432.1 1633.53   447.1 1636.18   459.2    1640
   600.6 1638.44   663.8 1650.88   738.1 1655.26   777.8  1659.7   819.9 1670.94
#Mann= 7 ,-1 , 0
       0      .1       0    92.2      .1       0     359    .045       0
   447.1      .1       0  453.29      .1       0  566.86      .1       0
  803.54      .1       0
Bank Sta=359,447.1
XS Rating Curve= 0 ,0
Exp/Cntr=0.3,0.1

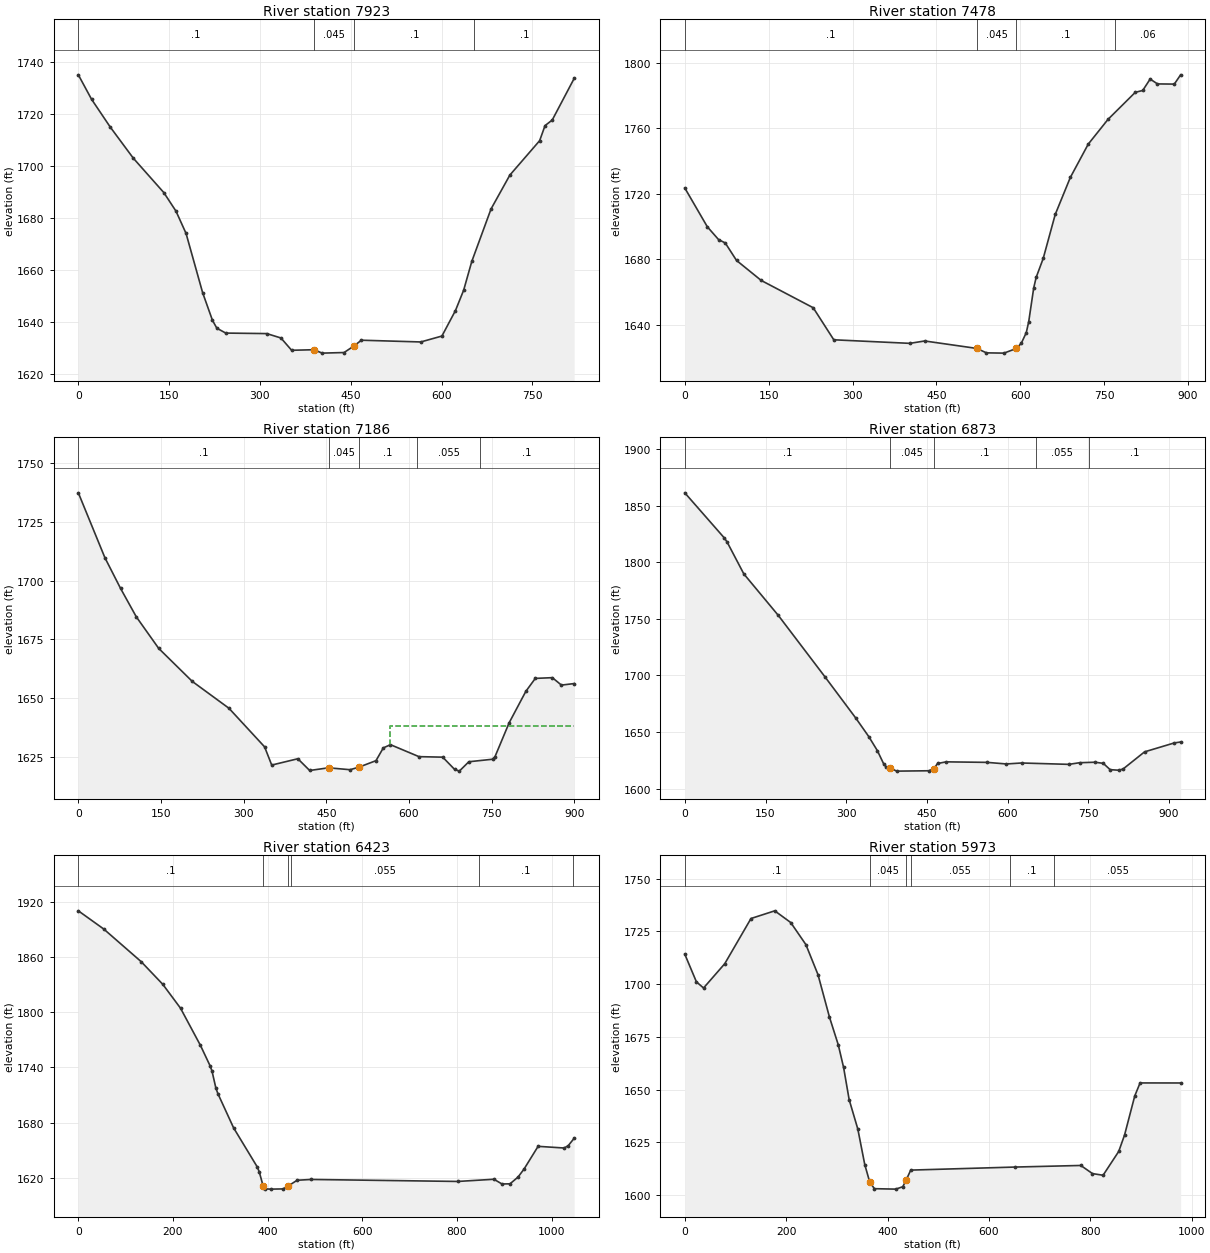
Type RM Length L Ch R = 1 ,7923    ,429.6,445.6,473.4
XS GIS Cut Line= 3
2425657.78284634674199.507475167     2425300.504      673998.484
     2424936.107      673812.895
#Sta/Elev= 30
       0 1734.98    21.8 1725.61    52.6 1714.96    90.8 1702.97   141.2 1689.76
   161.3 1682.63   177.9 1674.09   205.3 1651.33   221.5 1640.73   228.8 1637.68
   243.5 1635.82   311.2 1635.62   334.6 1633.94   352.3 1629.21     389 1629.43
   402.8 1628.12   438.9 1628.35   455.6 1630.93   467.5 1633.08   565.6 1632.41
   600.5 1634.68   622.9 1644.48   636.4 1652.29   649.8 1663.31   681.6 1683.47
   712.7 1696.48   761.9  1709.7   770.8 1715.48   782.7 1717.62   818.9 1733.59
#Mann= 4 ,-1 , 0
       0      .1       0     389    .045       0   455.6      .1       0
  654.06      .1       0
Bank Sta=389,455.6
XS Rating Curve= 0 ,0
Exp/Cntr=0.3,0.1

Type RM Length L Ch R = 1 ,7478    ,268.7,292,320.6
XS GIS Cut Line= 3
     2425722.476      674142.9592425704.85678492673962.968255423
2425400.91625299 673325.63698581
#Sta/Elev= 30
       0 1723.63    40.3 1699.94    60.4 1692.13    72.4 1690.06    92.5 1679.41
   136.7 1667.18   229.7 1650.52   266.5 1630.95   402.5 1628.78   429.1 1630.23
   522.2 1625.69   539.6 1622.98   570.9 1622.81   593.1 1625.65   601.9 1628.84
   610.8  1635.3   615.2 1642.06   624.1 1662.58   628.5 1669.05   641.1 1680.61
   662.6 1707.47   689.6 1730.06   721.6 1750.38     757 1765.52   805.8 1782.04
   819.1 1783.17   832.4 1790.14   845.5 1787.17   875.6 1787.06   886.9 1792.72
#Mann= 4 ,-1 , 0
       0      .1       0   522.2    .045       0   593.1      .1       0
  770.23     .06       0
Bank Sta=522.2,593.1
XS Rating Curve= 0 ,0
Exp/Cntr=0.3,0.1

Type RM Length L Ch R = 1 ,7186    ,320.4,312.4,293.4
XS GIS Cut Line= 3
2425763.47581087674150.323167849 2425718.5480969673906.062316846
2425960.83513237673301.488468072
#Sta/Elev= 30
       0 1737.24    48.2 1709.69    76.7 1696.62   105.2 1684.58   145.8 1671.19
   206.8 1657.15   273.3 1645.76     338 1629.36   350.9 1621.63   398.3 1624.32
   419.8 1619.33     454 1620.47   493.1 1619.66   509.4 1620.77   540.1  1623.5
   553.4 1628.93   566.4 1630.29   618.1 1625.21   661.2 1624.99   682.7 1619.81
   691.3 1619.06   708.6 1623.04   751.6 1624.11     756 1625.17   781.8 1639.62
     812 1652.93   829.2 1658.44   860.1 1658.75   876.6 1655.59   899.7 1656.24
#Mann= 5 ,-1 , 0
       0      .1       0     454    .045       0   509.4      .1       0
  615.08    .055       0  728.48      .1       0
#XS Ineff= 2 , 0
                          565.71         1638.18
Permanent Ineff=
       F       F
Bank Sta=454,509.4
XS Rating Curve= 0 ,0
Exp/Cntr=0.3,0.1

Type RM Length L Ch R = 1 ,6873    ,455.8,450,435.5
XS GIS Cut Line= 3
     2426103.268      674180.587     2426095.449      673771.906
2426095.52964806673259.211485485
#Sta/Elev= 30
       0 1861.42    73.7  1821.4    78.7 1817.87   109.7 1789.77   173.7 1753.14
   261.3 1698.29   317.8 1662.33   341.8 1646.06   357.8 1633.64   369.8 1621.71
   373.8 1619.39   381.8  1618.1   393.8 1615.46   453.8 1615.78   462.5 1617.41
   469.8 1622.21   485.8 1623.66   561.8  1623.2   597.8 1621.79   625.8 1622.65
   713.8 1621.44   733.8  1622.9   762.5 1623.33   777.8 1622.33   790.5 1616.75
   806.5 1616.26   814.5 1617.32   854.5  1632.5   909.8 1640.39   921.5 1641.21
#Mann= 5 ,-1 , 0
       0      .1       0   381.8    .045       0   462.5      .1       0
  652.38    .055       0  751.09      .1       0
Bank Sta=381.8,462.5
XS Rating Curve= 0 ,0
Exp/Cntr=0.3,0.1

Type RM Length L Ch R = 1 ,6423    ,473.9,450,430.3
XS GIS Cut Line= 3
     2426649.691      674090.553     2426537.942       673696.85
2426324.64526217673095.062786512
#Sta/Elev= 30
       0 1910.13    53.7 1890.36   132.7 1854.96   178.4 1830.32   215.9 1804.38
     258 1763.99   278.2 1741.99   282.4 1736.19   290.7 1717.45   294.9 1711.54
   328.1 1674.35     378 1631.99   382.2 1626.73   390.5 1611.27   394.7  1608.1
   406.3 1607.82   432.6 1608.05   442.8 1611.03   462.3 1617.45     492 1618.33
   801.8 1616.16   878.2 1618.54   895.1 1613.43   912.1 1613.57   929.1 1620.91
   941.8 1629.61   971.5  1654.3  1026.7 1652.48  1035.2 1655.05  1047.7 1663.05
#Mann= 6 ,-1 , 0
       0      .1       0   390.5    .045       0   442.8      .1       0
  449.37    .055       0  846.41      .1       0 1044.92     .06       0
Bank Sta=390.5,442.8
XS Rating Curve= 0 ,0
Exp/Cntr=0.3,0.1

Type RM Length L Ch R = 1 ,5973    ,442.8,450.5,467.6
XS GIS Cut Line= 3
     2427238.314      673643.571     2426888.577      673430.624
2426420.96735686673106.691837428
#Sta/Elev= 30
       0 1714.23    22.9 1701.12      37  1698.2    78.8 1709.71   130.6 1731.15
   177.5 1734.79     209 1729.24   238.9 1718.79   262.8 1704.54   285.4 1684.43
   302.9 1671.19   313.3 1660.55   324.3 1645.26   341.4 1631.31   355.1 1614.47
   364.8 1606.25   374.1 1603.05   416.3 1602.84   430.1 1603.98   436.5 1607.01
   445.8 1611.86   652.1 1613.31   781.4 1614.06   804.4  1610.2   825.3 1609.42
   856.2 1620.73   867.7 1628.51   887.8 1647.02   898.3 1653.19   978.3 1653.17
#Mann= 6 ,-1 , 0
       0      .1       0   364.8    .045       0   436.5      .1       0
  446.14    .055       0  641.45      .1       0  729.31    .055       0
Bank Sta=364.8,436.5
XS Rating Curve= 0 ,0
Exp/Cntr=0.3,0.1

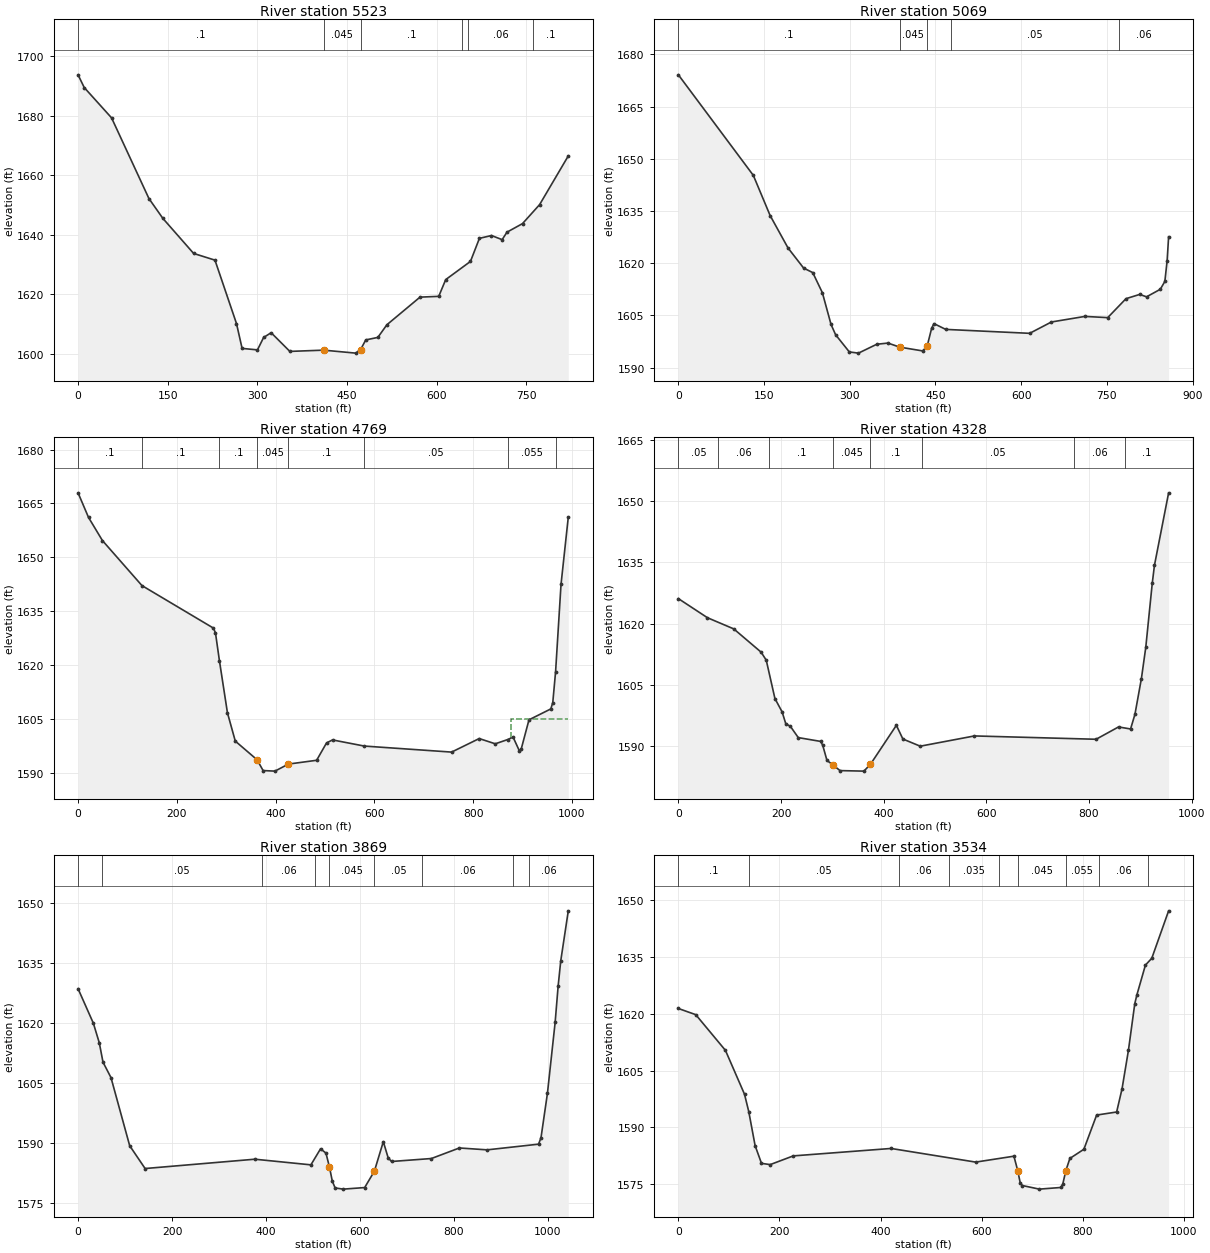
Type RM Length L Ch R = 1 ,5523    ,441.8,454,475.6
XS GIS Cut Line= 3
     2427380.139      673440.671     2427164.653      673090.646
     2426936.314      672751.045
#Sta/Elev= 30
       0 1693.77    10.3 1689.51    56.1  1679.3   118.6 1652.19   141.9 1645.53
   193.4 1633.74   229.1 1631.49   265.1 1610.18   274.5 1601.83   300.2 1601.33
   310.5  1605.5   323.1  1607.1   354.4 1600.82     411 1601.24   464.6 1600.24
   472.8 1601.45   481.4 1604.68   501.6 1605.52   516.8 1609.78   572.2 1619.06
   603.5 1619.32   615.2 1624.95   656.6 1631.06   671.6 1638.82   691.8 1639.76
   709.6 1638.38   717.7 1640.89   743.7 1643.77   772.3 1650.15   820.3 1666.52
#Mann= 6 ,-1 , 0
       0      .1       0     411    .045       0   472.8      .1       0
  642.54    .055       0  653.28     .06       0  760.98      .1       0
Bank Sta=411,472.8
XS Rating Curve= 0 ,0
Exp/Cntr=0.3,0.1

Type RM Length L Ch R = 1 ,5069    ,307.9,300,298.3
XS GIS Cut Line= 3
      2427581.39      673378.019     2427591.489      672962.206
2427579.71869978 672520.32197162
#Sta/Elev= 30
       0 1674.12   131.2 1645.22   160.6 1633.68   191.9 1624.37   219.2 1618.59
   235.2 1617.29     252 1611.52   267.2 1602.38   275.2 1599.43   299.2 1594.49
   315.2 1594.15   347.2  1596.7   366.8 1597.04   387.2 1595.88   427.3 1594.79
   435.3 1596.09   443.2 1601.27   447.3 1602.63   467.9 1600.97   614.8 1599.84
   652.9  1603.1   711.4  1604.7   751.4 1604.35   783.4  1609.8   807.4 1611.02
   819.4 1610.33   843.4 1612.49   851.4 1614.75   855.4  1620.7     858  1627.6
#Mann= 5 ,-1 , 0
       0      .1       0   387.2    .045       0   435.3      .1       0
  476.91     .05       0  771.92     .06       0
Bank Sta=387.2,435.3
XS Rating Curve= 0 ,0
Exp/Cntr=0.3,0.1

Type RM Length L Ch R = 1 ,4769    ,450.7,440.6,435.5
XS GIS Cut Line= 3
     2427918.133      673432.021     2427881.413      673025.651
2427825.98194324672443.595207987
#Sta/Elev= 30
       0 1667.97    21.2 1661.12    49.3 1654.69   129.4 1642.14   274.2 1630.29
   278.3 1628.93   286.3 1621.19   302.5 1606.71   318.4 1598.83   362.6 1593.62
   374.7 1590.63   398.7 1590.47   425.9 1592.43   483.1 1593.49   503.2 1598.33
   515.3 1599.16   579.6 1597.45   756.4 1595.77   812.3 1599.54   844.8 1598.08
     870 1599.26   880.9 1599.95   893.6 1596.12   897.3 1596.59   913.1 1604.76
   957.3 1607.79   961.3 1609.57     967  1618.2     978 1642.51   992.7 1661.23
#Mann= 8 ,-1 , 0
       0      .1       0   129.4      .1       0   286.3      .1       0
   362.6    .045       0   425.9      .1       0   579.6     .05       0
     870    .055       0     967      .1       0
#XS Ineff= 2 , 0
                           876.9            1605
Permanent Ineff=
       F       F
Bank Sta=362.6,425.9
XS Rating Curve= 0 ,0
Exp/Cntr=0.3,0.1

Type RM Length L Ch R = 1 ,4328    ,474.4,459.4,446.7
XS GIS Cut Line= 2
2428416.97950245673245.0250446972428109.62301214672340.773341341
#Sta/Elev= 30
       0 1626.12    56.7 1621.42   107.9 1618.68   161.1 1612.97   171.2 1610.99
   188.1 1601.56   202.1 1598.28   209.3 1595.35   218.2 1594.73   233.6 1591.96
   276.9 1591.03   281.1 1590.13   289.5 1586.35   302.2 1585.14   314.9 1583.85
   361.4 1583.72     374 1585.36   424.7 1594.98   437.4 1591.61   471.2 1589.85
   576.8 1592.37   813.8 1591.55   857.5 1594.58     881 1594.08   889.5 1597.69
   902.1 1606.48   910.6 1614.15   923.2 1629.86   927.5  1634.3   955.1 1652.12
#Mann= 8 ,-1 , 0
       0     .05       0    77.7     .06       0  176.72      .1       0
   302.2    .045       0     374      .1       0   473.8     .05       0
  770.87     .06       0   869.9      .1       0
Bank Sta=302.2,374
XS Rating Curve= 0 ,0
Exp/Cntr(USF)=0,0
Exp/Cntr=0.3,0.1

Type RM Length L Ch R = 1 ,3869    ,316.3,334.9,351.2
XS GIS Cut Line= 3
2429055.51358869673112.913427935     2428686.658      672666.544
2428388.77598581672310.374125279
#Sta/Elev= 30
       0 1628.56    32.6 1619.92    45.2 1615.03    53.1 1610.19    70.1 1606.33
   109.9  1589.3   142.7  1583.6   376.2 1585.93   495.6 1584.52   516.1 1588.53
   527.6 1587.46     535 1584.01   541.2 1580.41   547.2 1578.74   564.5 1578.45
     610 1578.84   630.7 1582.94   649.7 1590.32     660 1586.28   667.2 1585.36
     752  1586.1   811.6 1588.74   870.6 1588.27   980.1 1589.69   985.3 1591.29
     999  1602.4  1015.4 1620.13  1021.8 1629.24  1027.4 1635.58  1043.4 1648.03
#Mann= 9 ,-1 , 0
       0      .1       0   51.22     .05       0  391.66     .06       0
  505.14    .055       0     535    .045       0   630.7     .05       0
  732.64     .06       0  926.32    .035       0   960.4     .06       0
Bank Sta=535,630.7
XS Rating Curve= 0 ,0
Exp/Cntr=0.3,0.1

Type RM Length L Ch R = 1 ,3534    ,89,85.2,88
XS GIS Cut Line= 2
2429121.94140326673099.6454121762428829.47287317672175.119892069
#Sta/Elev= 30
       0 1621.38    34.4 1619.75    93.1 1610.33   130.8 1598.76   139.2 1594.19
   151.8 1585.19   164.4 1580.52   181.6 1580.19   227.3 1582.49   420.7 1584.45
   588.1 1580.85   663.7 1582.41   671.3 1578.58   676.2 1575.35   680.4 1574.67
     714 1573.72     756 1574.15   760.2 1574.98   766.5 1578.63   774.4 1581.82
   802.1 1584.24   827.3 1593.26   866.9 1594.07   877.6 1600.21   890.2 1610.33
   902.8 1622.68     907    1625   923.8 1632.83   936.4 1634.63   969.7 1647.15
#Mann= 9 ,-1 , 0
       0      .1       0  140.27     .05       0  436.31     .06       0
  534.99    .035       0  633.67    .055       0   671.3    .045       0
   766.5    .055       0  831.03     .06       0  929.71      .1       0
Bank Sta=671.3,766.5
XS Rating Curve= 0 ,0
Exp/Cntr(USF)=0,0
Exp/Cntr=0.5,0.3

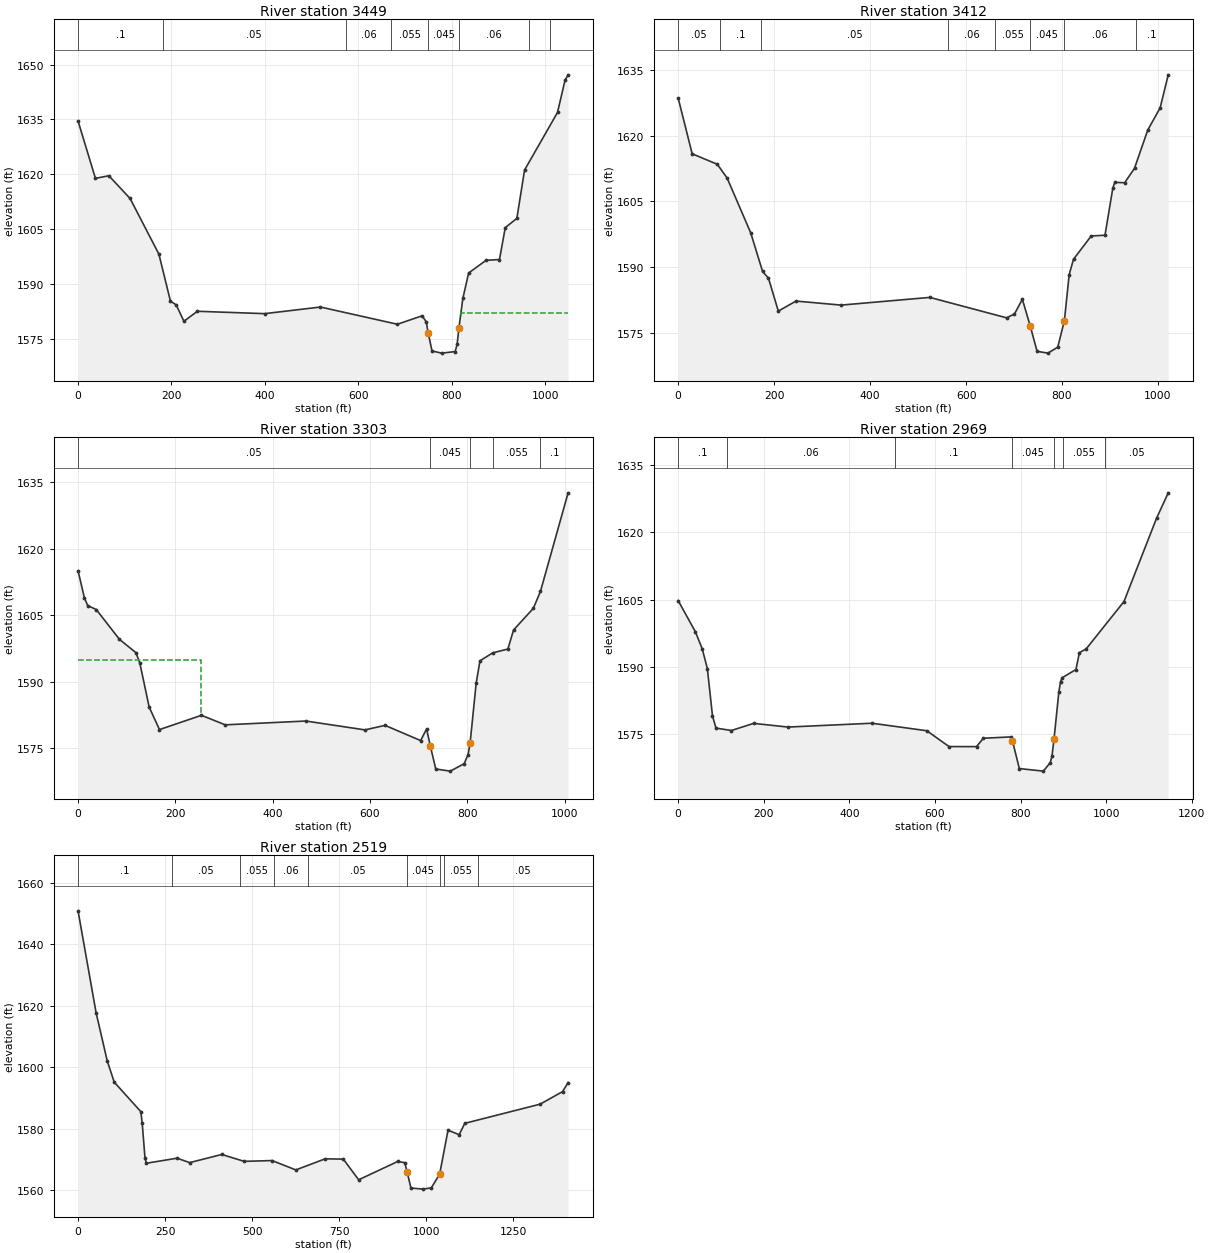
Type RM Length L Ch R = 1 ,3449    ,37,36.6,37.8
XS GIS Cut Line= 3
2429168.54588077673135.0320051772428987.04515263672391.167316155
2428917.53040144672116.519073846
#Sta/Elev= 30
       0 1634.56    37.2 1618.86      66 1619.57   111.3 1613.36   173.1 1598.12
   197.8 1585.25   210.1 1584.25   226.6 1579.75   255.4 1582.49   399.5 1581.84
   518.9 1583.65   683.6 1578.94   736.4 1581.25   745.4 1579.61   749.3 1576.67
   757.7 1571.63   778.4 1571.04   807.2 1571.46   811.4 1573.43   815.4 1578.02
   823.7    1586   836.1 1592.97   873.3 1596.42   902.1 1596.65   914.5 1605.38
   939.3  1607.9   955.8 1621.13  1026.3 1636.88  1042.4 1645.71    1049 1647.18
#Mann= 8 ,-1 , 0
       0      .1       0  181.43     .05       0     573     .06       0
   670.9    .055       0   749.3    .045       0   815.4     .06       0
  964.73      .1       0 1010.26      .1       0
#XS Ineff= 2 , 0
             740    1580     819            1582
Permanent Ineff=
       F       F
Bank Sta=749.3,815.4
XS Rating Curve= 0 ,0
Exp/Cntr=0.5,0.3

Type RM Length L Ch R = 1 ,3412    ,108.1,109.2,110.8
XS GIS Cut Line= 2
2429190.18406028673122.3929645162428964.33336204672126.375137054
#Sta/Elev= 30
       0 1628.57    29.2 1615.84    81.5 1613.45     102 1610.31   151.2 1597.78
   175.9 1588.97   188.2 1587.43   208.7 1579.91   245.6  1582.2   339.6 1581.28
   524.5 1583.04   684.5 1578.37   700.9 1579.26   717.3 1582.61   733.7  1576.5
     748 1570.72   770.6 1570.31   791.1 1571.68   804.9 1577.73   814.9 1588.27
   823.9 1591.76   860.8 1597.07   889.5 1597.24   905.9 1608.04     910 1609.32
   930.5 1609.23     951 1612.53   978.7 1621.28  1004.4 1626.33  1021.3 1633.88
#Mann= 8 ,-1 , 0
       0     .05       0   87.94      .1       0  172.01     .05       0
  563.09     .06       0  660.86    .055       0   733.7    .045       0
   804.9     .06       0  954.17      .1       0
Bank Sta=733.7,804.9
XS Rating Curve= 0 ,0
Exp/Cntr(USF)=0,0
Exp/Cntr=0.5,0.3

Type RM Length L Ch R = 1 ,3303    ,328.1,334.1,340.3
XS GIS Cut Line= 2
2429264.92601797673107.7695380122429084.57042441672116.626186052
#Sta/Elev= 30
       0 1615.02    13.1  1608.9    19.8 1607.18    37.5 1606.27    85.2 1599.54
   118.8 1596.57   126.9 1594.27   146.2 1584.27   167.4  1579.2   253.7 1582.42
   302.6 1580.27   468.4 1581.13   589.8 1579.13   631.1 1580.15   704.3 1576.72
   716.5 1579.35     724 1575.61   735.3 1570.31   765.2 1569.83   793.8 1571.51
   801.8 1573.58   805.9 1576.11   818.4 1589.64   826.2 1594.71   852.3  1596.5
   883.6 1597.37   895.3 1601.67     936 1606.56   950.6 1610.38  1007.4  1632.6
#Mann= 5 ,-1 , 0
       0     .05       0     724    .045       0   805.9      .1       0
   852.3    .055       0   950.6      .1       0
#XS Ineff= 2 , 0
           253.7    1595
Permanent Ineff=
       F       F
Bank Sta=724,805.9
XS Rating Curve= 0 ,0
Exp/Cntr(USF)=0,0
Exp/Cntr=0.3,0.1

Type RM Length L Ch R = 1 ,2969    ,451.1,450,450.1
XS GIS Cut Line= 3
     2429499.326 673114.96633014      2429454.92      672288.874
2429434.18773052671971.744375962
#Sta/Elev= 30
       0 1604.81    40.1 1597.88    56.2 1594.07    68.2 1589.65    80.2 1579.11
    88.4  1576.4   124.3 1575.86   176.3 1577.45   256.4 1576.63     453 1577.48
   580.9 1575.81     633 1572.28   697.1 1572.27   713.1 1574.14   777.2 1574.43
   781.2 1573.52   797.2 1567.38   853.3 1566.81   869.4 1568.69   873.4 1570.11
   878.2 1573.93   889.4 1584.34   893.4 1586.72   897.4 1587.63   929.5 1589.45
   937.5  1593.2   953.6 1594.07  1041.7  1604.6  1117.9 1623.18  1145.1 1628.82
#Mann= 7 ,-1 , 0
       0      .1       0  114.77     .06       0   506.9      .1       0
   781.2    .045       0   878.2     .06       0  898.95    .055       0
  996.87     .05       0
Bank Sta=781.2,878.2
XS Rating Curve= 0 ,0
Exp/Cntr=0.3,0.1

Type RM Length L Ch R = 1 ,2519    ,490.4,493.4,498.2
XS GIS Cut Line= 3
2429978.75546103673294.663716807     2429901.246      672299.192
     2429871.081      671890.805
#Sta/Elev= 30
       0 1650.91    51.9 1617.76      84 1602.05   104.1 1595.19   180.3 1585.63
   184.3 1581.97   192.4 1570.44   196.4 1568.84   284.6 1570.48   320.7 1569.04
   413.1 1571.69   477.2 1569.45   557.5 1569.71   625.7 1566.66   709.9 1570.27
   762.1 1570.18   806.2 1563.46   918.5 1569.41   938.6 1569.03   945.3  1566.1
   956.4 1560.78   990.8 1560.42  1014.8 1560.82  1038.9 1565.26    1063 1579.59
    1095 1578.12  1111.1 1581.81  1327.7 1588.05  1391.9 1592.11    1408 1595.05
#Mann= 9 ,-1 , 0
       0      .1       0  268.61     .05       0  464.26    .055       0
  562.09     .06       0  659.91     .05       0   945.3    .045       0
  1038.9     .05       0 1051.22    .055       0 1149.08     .05       0
Bank Sta=945.3,1038.9
XS Rating Curve= 0 ,0
Exp/Cntr=0.3,0.1