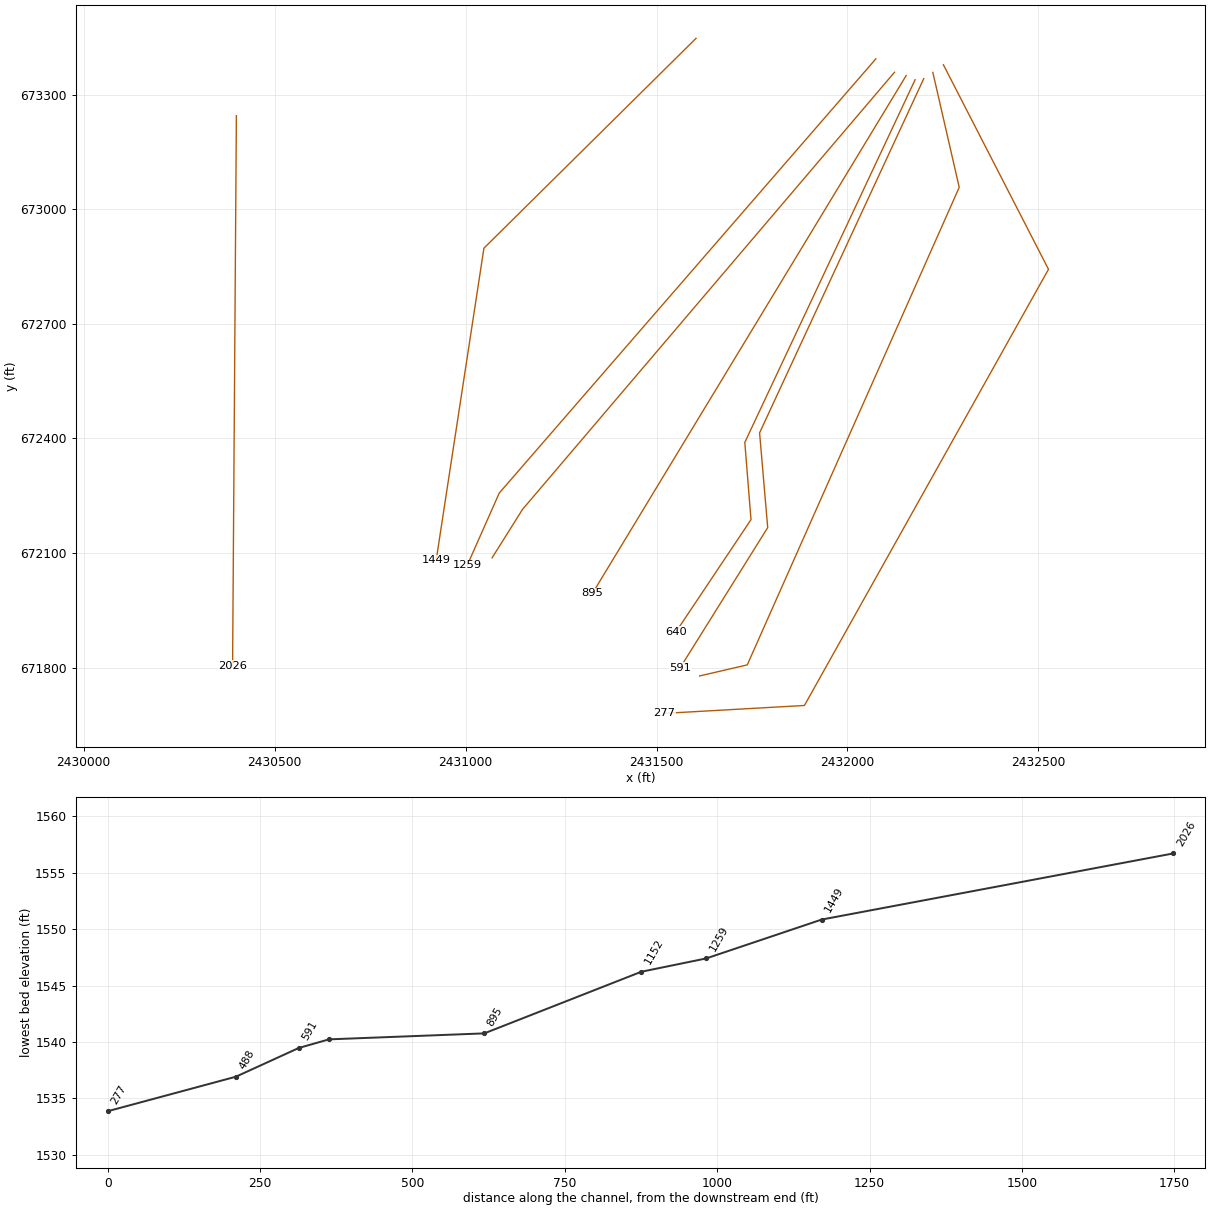
HEC-RAS study SENECACK.prj: SENECACK

--- SENECACK.g03 (geometry) --- (continued)

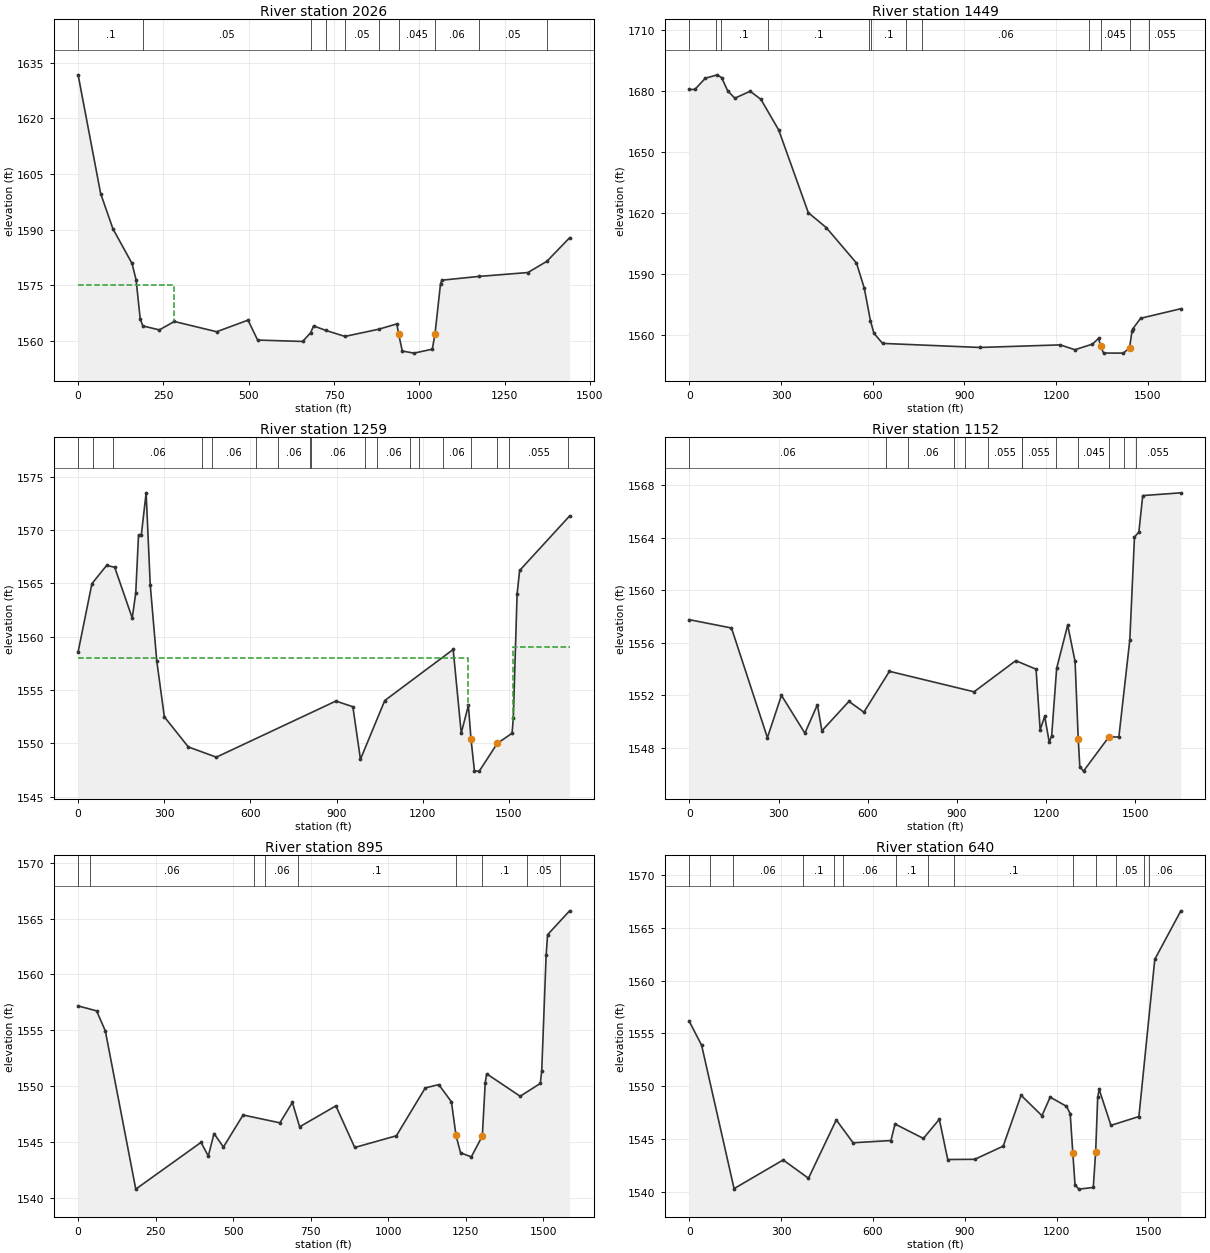
Type RM Length L Ch R = 1 ,2026    ,578.8,576.9,565.3
XS GIS Cut Line= 2
2430399.89593292673244.8525971682430389.99717317671804.583053234
#Sta/Elev= 30
       0 1631.75      66 1599.75     102 1590.24     158 1580.88     170 1576.43
     182 1565.89   189.8 1564.05     238 1562.97     282 1565.24     406 1562.48
     498 1565.61     526 1560.23     658 1559.86   681.5 1562.21     690 1564.05
   726.1 1562.83     782 1561.22   881.1 1563.16     934 1564.59   939.3 1561.89
     950 1557.27   984.4 1556.71    1038 1557.78    1046 1561.99    1062  1575.4
    1066 1576.38    1174 1577.39  1318.1 1578.44  1373.7 1581.47  1440.3 1587.82
#Mann= 10 ,-1 , 0
       0      .1       0   189.8     .05       0   681.5     .06       0
   726.1    .055       0     782     .05       0   881.1      .1       0
   939.3    .045       0    1046     .06       0    1174     .05       0
  1373.7     .05       0
#XS Ineff= 2 , 0
             282    1575
Permanent Ineff=
       F       F
Bank Sta=939.3,1046
XS Rating Curve= 0 ,0
Exp/Cntr(USF)=0,0
Exp/Cntr=0.3,0.1

Type RM Length L Ch R = 1 ,1449    ,215.7,189.8,175.2
XS GIS Cut Line= 3
2431603.42919732673447.551531561 2431048.0777472672898.118086726
2430923.02862107672080.992935467
#Sta/Elev= 30
       0 1680.62      18 1680.63    52.1 1686.14    91.5 1687.83   105.6 1686.44
   125.4 1679.95   148.8 1676.33   198.9 1679.75   234.1 1675.76   292.3 1660.68
   389.2 1619.98   447.8 1612.65   546.8 1595.19   572.3  1582.8   592.4 1566.82
   603.8 1560.63   632.2 1555.64   950.2 1553.64  1213.4 1554.91  1261.2 1552.52
  1318.7 1555.28  1338.9 1558.13  1345.3 1554.31    1355 1550.89  1419.8 1550.85
    1440 1553.38  1448.1 1561.62  1451.1 1562.88  1476.2 1567.99  1607.9 1572.71
#Mann= 12 ,-1 , 0
       0      .1       0   87.08    .055       0  103.36      .1       0
  255.65      .1       0  588.56     .05       0   592.8      .1       0
  709.86     .05       0  761.37     .06       0 1309.07      .1       0
  1345.3    .045       0    1440      .1       0 1504.14    .055       0
Bank Sta=1345.3,1440
XS Rating Curve= 0 ,0
Exp/Cntr=0.5,0.3

Type RM Length L Ch R = 1 ,1259    ,98.2,106.4,91.8
XS GIS Cut Line= 3
2432074.24317232673393.8199099382431088.22601279672256.949187533
2431004.31507281672067.685352841
#Sta/Elev= 30
       0 1558.58    48.1 1564.98    99.2 1566.69   127.4 1566.52   188.5 1561.76
   200.7  1564.1   210.4 1569.54   220.1 1569.53   236.9  1573.5   251.2 1564.88
   273.9 1557.74   300.4 1552.49   383.8 1549.67   481.5 1548.71   897.8 1553.97
     957 1553.44   983.4 1548.51  1068.1 1554.02  1306.4 1558.81  1334.4 1550.97
  1359.4 1553.56  1368.5  1550.4  1380.5 1547.41  1397.3  1547.4    1460    1550
  1511.5 1550.95  1515.9 1552.42    1529 1563.99  1537.9 1566.22  1711.9 1571.33
#Mann= 18 ,-1 , 0
       0     .06       0   53.38      .1       0  120.77     .06       0
  431.11      .1       0  466.21     .06       0  619.97     .05       0
   696.5     .06       0  808.84     .05       0  811.65     .06       0
   997.7     .05       0 1041.94     .06       0 1157.08    .055       0
 1186.57     .05       0 1272.23     .06       0  1368.5    .045       0
    1460     .06       0 1502.52    .055       0 1704.84    .035       0
#XS Ineff= 2 , 0
            1359    1558    1515            1559
Permanent Ineff=
       F       F
Bank Sta=1368.5,1460
XS Rating Curve= 0 ,0
Exp/Cntr=0.5,0.3

Type RM Length L Ch R = 1 ,1152    ,255.1,257.5,278.1
XS GIS Cut Line= 3
2432123.12576812673358.7634776432431149.13334848672214.164415451
2431069.51691529672087.428052414
#Sta/Elev= 30
       0 1557.75   141.6 1557.12   262.4 1548.77   309.7 1551.99   388.5 1549.11
   430.5 1551.28   445.7 1549.29   536.5 1551.53   586.9 1550.71   672.7 1553.82
   957.3 1552.26  1097.5 1554.63  1165.8 1553.98  1179.5 1549.37  1194.8 1550.39
  1210.3  1548.4  1218.3 1548.93    1235 1554.04  1272.1 1557.34    1297 1554.57
  1307.6 1548.67  1312.9 1546.56  1325.3 1546.22  1410.5 1548.82  1444.2 1548.82
    1481 1556.21  1496.7 1564.04  1511.5 1564.43  1524.4  1567.2  1652.6 1567.41
#Mann= 13 ,-1 , 0
       0     .06       0  660.59    .055       0   733.6     .06       0
  889.54      .1       0   925.4     .06       0 1004.01    .055       0
 1117.19     .06       0 1118.49    .055       0 1232.96     .06       0
  1307.6    .045       0  1410.5     .06       0 1461.91      .1       0
 1500.77    .055       0
Bank Sta=1307.6,1410.5
XS Rating Curve= 0 ,0
Exp/Cntr(USF)=0,0
Exp/Cntr=0.5,0.3

Type RM Length L Ch R = 1 ,895     ,255.4,254.8,252.8
XS GIS Cut Line= 2
2432153.60857147673349.9798533262431332.16918141671994.153519404
#Sta/Elev= 30
       0 1557.17    59.6 1556.73    87.8 1554.93     186 1540.76   396.5 1544.95
   419.9 1543.72   438.3 1545.74   468.7 1544.53   532.1  1547.4   650.9  1546.7
   691.1 1548.53   714.5 1546.34   831.5 1548.22   892.2 1544.49  1026.6 1545.54
  1119.8 1549.83  1163.4 1550.12  1204.2 1548.58  1218.8 1545.58  1233.6 1544.01
  1268.3 1543.65  1303.8 1545.52  1313.1 1550.27  1317.8 1551.09  1425.9 1549.08
  1490.9 1550.23  1495.4 1551.37  1509.6 1561.69  1514.2 1563.55  1585.3 1565.69
#Mann= 9 ,-1 , 0
       0     .05       0   37.68     .06       0   567.9     .05       0
  604.38     .06       0  709.86      .1       0  1218.8    .045       0
  1303.8      .1       0 1448.23     .05       0 1553.72      .1       0
Bank Sta=1218.8,1303.8
XS Rating Curve= 0 ,0
Exp/Cntr(USF)=0,0
Exp/Cntr=0.5,0.3

Type RM Length L Ch R = 1 ,640     ,48.2,49.4,50.9
XS GIS Cut Line= 4
2432177.07826833673339.1476855452431731.15402801 672389.52764341
2431747.40227968672187.3271781652431550.61789833671893.053286781
#Sta/Elev= 30
       0 1556.14    40.1 1553.88   146.1 1540.28   306.6    1543   389.2 1541.26
   480.1  1546.8     535 1544.63   658.7 1544.84     672 1546.41   764.8 1545.04
   816.8 1546.86   844.3 1543.04   932.7 1543.06  1025.5 1544.31  1083.9 1549.14
  1152.1  1547.2    1179 1548.96  1232.3 1548.09  1244.4  1547.4  1253.1 1543.62
  1260.3 1540.62  1272.9 1540.23  1319.9 1540.39  1327.7 1543.79  1334.3 1548.95
  1339.1 1549.69  1377.6 1546.28    1469 1547.12  1520.9 1562.04    1606 1566.64
#Mann= 14 ,-1 , 0
       0     .05       0   66.76      .1       0  142.02     .06       0
  371.66      .1       0   473.3     .05       0  503.55     .06       0
  676.56      .1       0   778.2     .06       0  865.08      .1       0
  1253.1    .045       0  1327.7      .1       0 1393.04     .05       0
  1485.7      .1       0 1500.61     .06       0
#XS Ineff= 2 , 0
            1216  1544.9    1344          1544.9
Permanent Ineff=
       F       F
Bank Sta=1253.1,1327.7
XS Rating Curve= 0 ,0
Exp/Cntr(USF)=0,0
Exp/Cntr=0.5,0.3

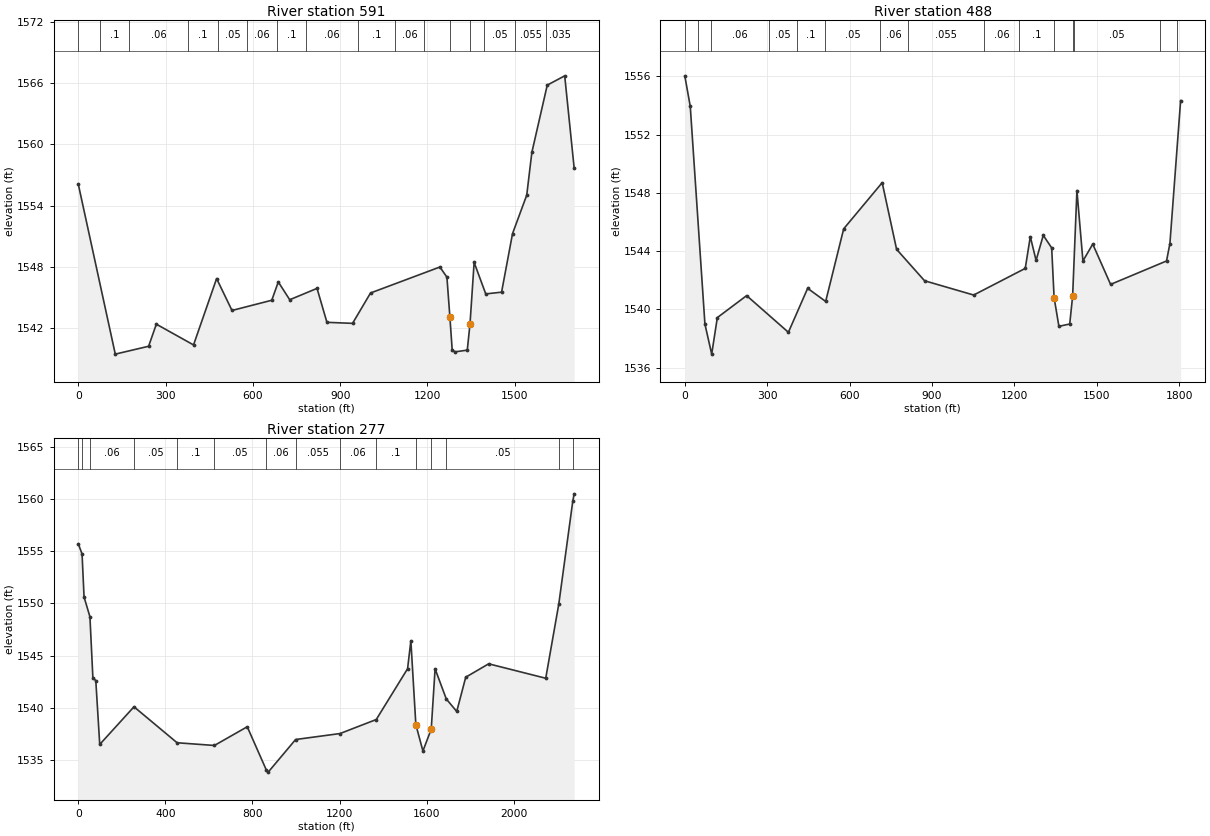
Type RM Length L Ch R = 1 ,591     ,98.4,103.3,108
XS GIS Cut Line= 4
2432199.77363594673342.1367963622431769.86096184672414.548288011
2431791.12367721672166.4874452652431561.75575209671799.327083932
#Sta/Elev= 30
       0 1556.07     127 1539.47   241.6 1540.24   268.1  1542.4     396 1540.37
   475.3 1546.86   528.2 1543.74   664.9 1544.74   687.3 1546.53   726.6 1544.79
   820.5  1545.9   854.5 1542.58   942.6 1542.48  1004.4 1545.45  1242.8 1547.99
  1266.9    1547  1277.1 1543.13    1285  1539.9    1294 1539.69  1336.9 1539.86
  1346.3 1542.42  1360.5 1548.44  1400.4 1545.36  1454.8 1545.53  1492.5 1551.26
  1541.3 1555.02  1558.9  1559.2  1611.8 1565.78  1671.8 1566.69  1704.3 1557.67
#Mann= 16 ,-1 , 0
       0     .05       0   73.36      .1       0  174.85     .06       0
  377.82      .1       0  479.31     .05       0  580.79     .06       0
  682.28      .1       0  783.77     .06       0  961.79      .1       0
 1089.44     .06       0 1187.93      .1       0  1277.1    .045       0
  1346.3      .1       0 1395.39     .05       0 1501.48    .055       0
 1607.57    .035       0
Bank Sta=1277.1,1346.3
XS Rating Curve= 0 ,0
Exp/Cntr=0.5,0.3

Type RM Length L Ch R = 1 ,488     ,213.7,210.4,207.3
XS GIS Cut Line= 4
2432223.48274018673358.315719067 2432292.5768145673057.422169595
2431737.59537881671807.0423084542431612.78027681671778.067374061
#Sta/Elev= 30
       0 1556.04    19.9 1553.94    73.3 1538.98    97.9 1536.92   118.4 1539.43
   225.1 1540.94   377.1 1538.42   447.2 1541.44   512.8 1540.54   578.4 1545.53
   718.5  1548.7     771 1544.12   872.8 1541.96  1051.6 1540.98  1239.3 1542.81
  1257.7 1544.99  1278.7 1543.36  1304.9 1545.08  1335.5 1544.22  1344.3 1540.81
  1361.8 1538.83  1401.2 1538.99  1411.8 1540.91  1427.4 1548.16  1449.3 1543.32
    1485 1544.48    1550 1541.71  1753.6 1543.32  1765.9 1544.52  1804.9 1554.34
#Mann= 15 ,-1 , 0
       0     .05       0   46.59      .1       0   97.05     .06       0
   307.1     .05       0  408.19      .1       0  509.22     .05       0
  711.27     .06       0   812.3    .055       0 1088.15     .06       0
 1216.41      .1       0  1344.3    .045       0  1411.8      .1       0
 1418.46     .05       0 1729.72    .035       0 1792.72     .06       0
Bank Sta=1344.3,1411.8
XS Rating Curve= 0 ,0
Exp/Cntr(USF)=0,0
Exp/Cntr=0.3,0.1

Type RM Length L Ch R = 1 ,277     ,,,
XS GIS Cut Line= 4
2432251.16173881673378.3155500812432526.31462073 672842.80295193
2431887.24986271671700.7705602952431520.37935348671680.060128322
#Sta/Elev= 30
       0 1555.69    17.1 1554.73    26.3 1550.61    53.3 1548.72    66.8  1542.9
    80.3 1542.61    98.3 1536.51   255.7 1540.11   453.8 1536.67   625.2 1536.41
   776.1  1538.2   863.2 1534.09   872.4 1533.86   998.4 1536.98  1202.4 1537.55
  1368.8 1538.89  1512.8 1543.75  1527.9 1546.43  1550.8  1538.4  1583.3 1535.88
  1621.5 1537.97  1639.2 1543.74  1690.6 1540.86  1738.7 1539.66    1780 1542.94
  1885.4 1544.22  2147.6 1542.84  2207.7 1549.95  2271.8 1559.77  2278.2 1560.48
#Mann= 15 ,-1 , 0
       0     .05       0    17.1      .1       0    53.3     .06       0
   255.7     .05       0   453.8      .1       0   625.2     .05       0
   863.2     .06       0   998.4    .055       0  1202.4     .06       0
  1368.8      .1       0  1550.8    .045       0  1621.5      .1       0
  1690.6     .05       0  2207.7    .035       0  2271.8     .06       0
Bank Sta=1550.8,1621.5
XS Rating Curve= 0 ,0
Exp/Cntr(USF)=0,0
Exp/Cntr=0.3,0.1
LCMann Table=0

Chan Stop Cuts=-1
Use User Specified Reach Order=0
Composite Channel Slope=5